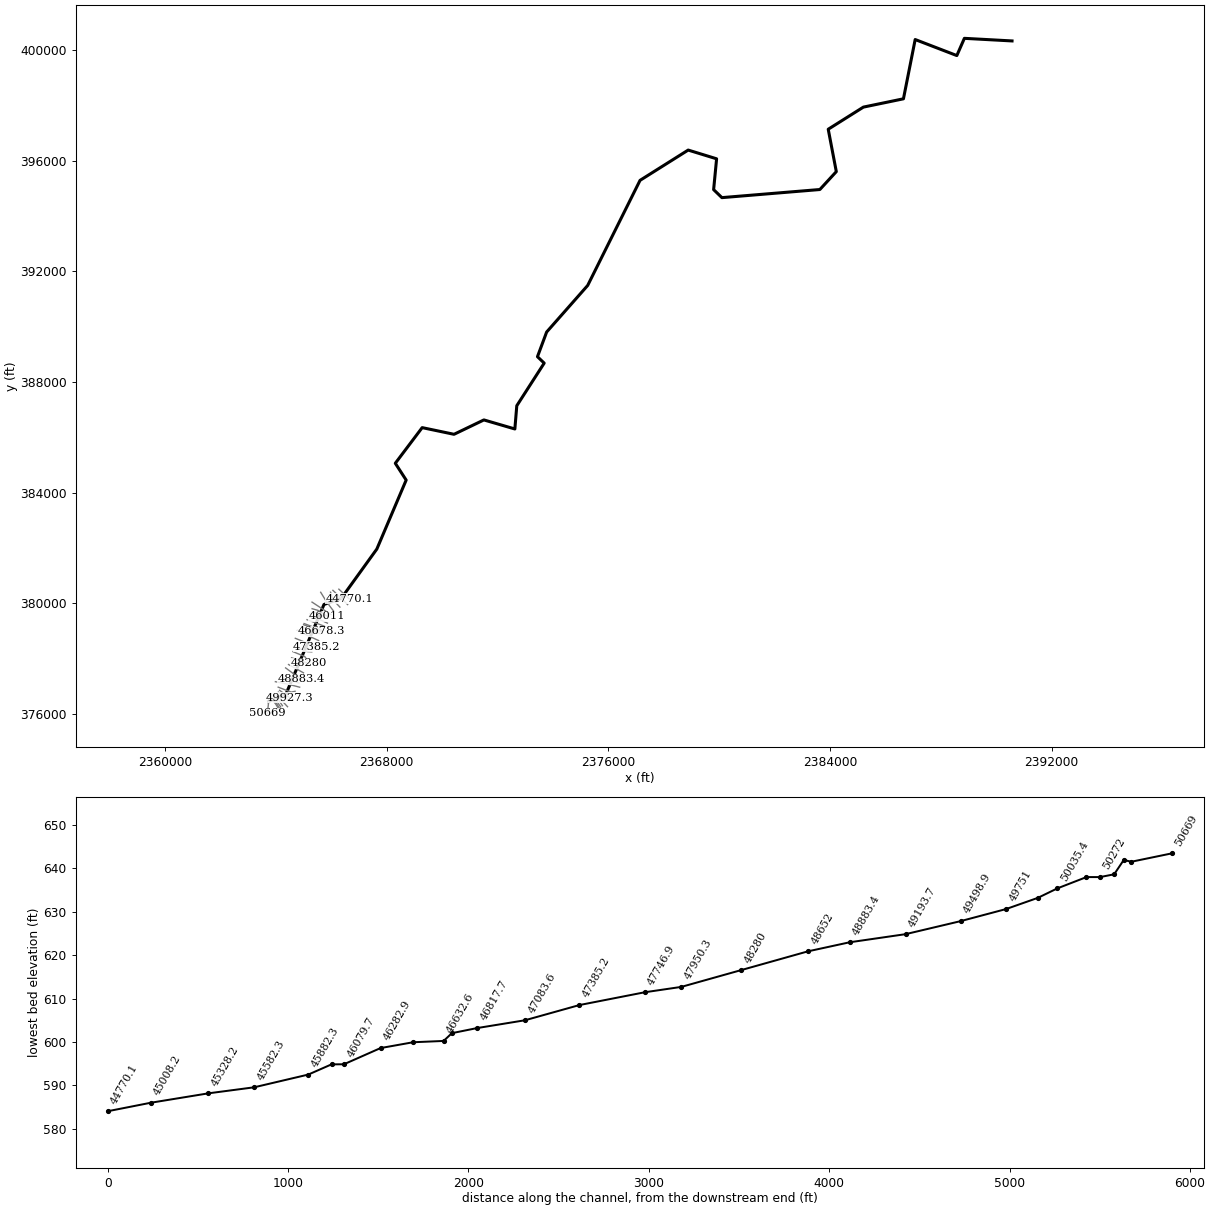
--- TILHANCECK.prj (project) ---

Proj Title=TILHANCECK
Current Plan=p01
Default Exp/Contr=0,0
English Units
Geom File=g01
Flow File=f01
Plan File=p01
BEGIN DESCRIPTION:
END DESCRIPTION:
DSS Export Rating Curves= 0
DSS Export Rating Curve Sorted= 0
DSS Export Volume Flow Curves= 0
DXF OffsetX= 0
DXF OffsetY= 0
DXF ScaleX= 0
DXF ScaleY= 0

--- TILHANCECK.p01 (plan) ---

Plan Title=Floodplain
Program Version=4.00
Geom File=g01
Flow File=f01
K Sum by GR=0
Std Step Tol=0.01
Critical Tol=0.01
Num of Std Step Trials=20
Max Error Tol=0.3
Flow Tol Ratio=0.001
Split Flow NTrial=30
Split Flow Tol=0.02
Split Flow Ratio=0.02
Log Output Level=0
Friction Slope Method=1
Unsteady Friction Slope Method=2
Unsteady Bridges Friction Slope Method=1
Global Log Level=0
CheckData=False
Run HTab=0
Run UNet=0
Run PostProcess=0
UNET Theta=0
UNET Theta Warmup=0
UNET ZTol=0
UNET ZSATol=0
UNET MxIter=0
UNET MaxInSteps=0
UNET DtIC=0
UNET DtMin=0
UNET MaxCRTS=0
UNET WFStab=0
UNET SFStab=0
UNET WFX=0
UNET SFX=0
UNET DSS MLevel=0
UNET DZMax Abort=0
UNET Convert EG Bridges=0
UNET Use Existing IB Tables=0
UNET Froude Limit=0
UNET Froude Power=0
Write IC File=0
Echo Input=False
Echo Output=False
Write Detailed=0

--- TILHANCECK.f01 (steady flow) ---

Flow Title=NFF Regression Equation
Program Version=4.00
Number of Profiles=1
Profile Names=P100yr
River Rch & RM=TILHANCECK,Main      ,50669
421.6794
River Rch & RM=TILHANCECK,Main      ,50035.4
598.6324
River Rch & RM=TILHANCECK,Main      ,49498.9
637.7650
River Rch & RM=TILHANCECK,Main      ,45882.3
697.0285
River Rch & RM=TILHANCECK,Main      ,45582.3
869.2987
River Rch & RM=TILHANCECK,Main      ,44387.1
877.6572
River Rch & RM=TILHANCECK,Main      ,43742.4
1103.202
River Rch & RM=TILHANCECK,Main      ,43427.7
1112.745
River Rch & RM=TILHANCECK,Main      ,39935
1231.282
River Rch & RM=TILHANCECK,Main      ,33339.5
1784.343
River Rch & RM=TILHANCECK,Main      ,33339.5
1333.025
River Rch & RM=TILHANCECK,Main      ,28490.1
1895.675
River Rch & RM=TILHANCECK,Main      ,26523.7
2100.523
River Rch & RM=TILHANCECK,Main      ,26297.3
3171.008
River Rch & RM=TILHANCECK,Main      ,23648.4
3243.297
River Rch & RM=TILHANCECK,Main      ,19954.4
3594.610
River Rch & RM=TILHANCECK,Main      ,407
3968.383
River Rch & RM=TILHANCECK,Main      ,157.1
3969.176
Boundary for River Rch & Prof#=TILHANCECK,Main      ,1
Up Type=0
Dn Type=3
Dn Slope=0.002427

--- TILHANCECK.g01 (geometry) ---

Geom Title=USGS 10m DEM
Program Version=4.10

River Reach=TILHANCECK      ,Main
Reach XY= 30
     2363733.851      376447.816     2364353.999      376702.544
     2365732.115       379954.76     2366358.851      380180.455
     2367640.102      381959.969     2368699.129       384454.76
     2368306.768      385062.399     2369277.254       386352.33
      2370426.56       386111.01      2371505.07      386630.952
      2372622.74      386303.719     2372692.185      387143.996
     2373681.768      388685.663     2373438.713      388918.302
      2373770.31      389810.663     2375251.213      391494.691
     2377141.837      395296.774     2378879.685       396392.26
     2379905.726      396076.288     2379798.087      394961.704
     2380096.699      394671.774     2383633.157      394965.177
     2384226.907      395612.746      2383935.24      397145.732
     2385204.337       397946.08     2386650.518      398246.427
     2387074.129      400390.524     2388577.601      399810.663
     2388850.171      400433.927     2390570.557      400339.945

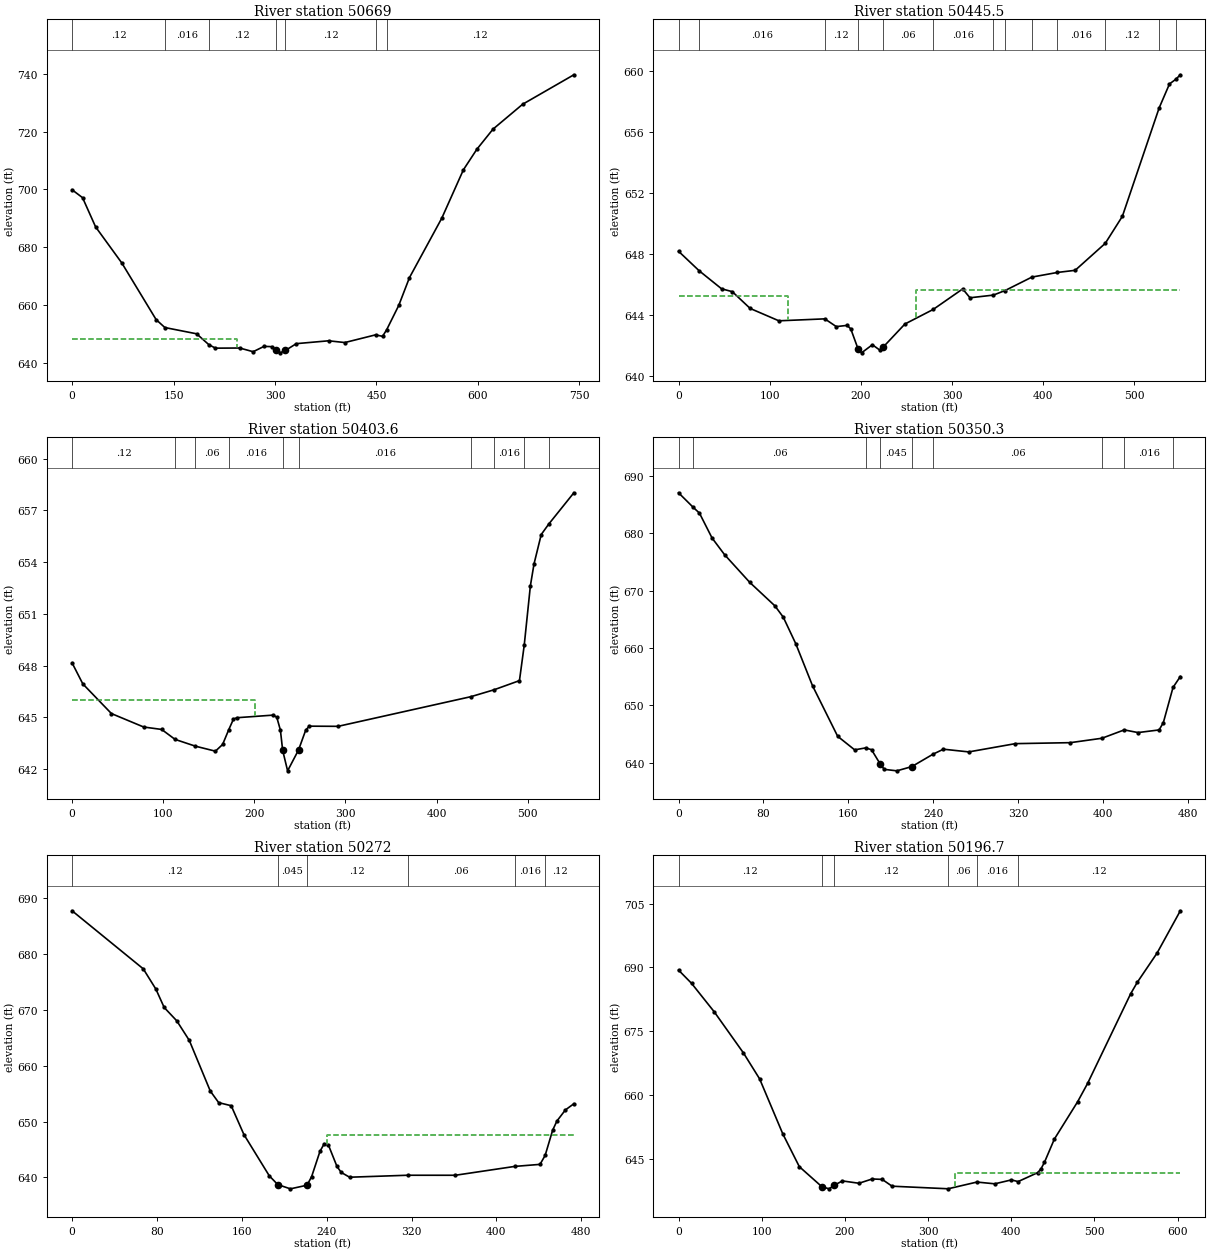
Type RM Length L Ch R = 1 ,50669   ,205.5,223.6,241.6
XS GIS Cut Line= 3
     2363817.559      376737.257     2363760.267      376645.243
     2363687.014      376016.089
#Sta/Elev= 30
       0  699.85    15.5  697.11    34.8     687    73.6  674.49   124.3   654.9
  137.19652.1655   184.1     650  202.27 646.223     212  645.03   247.8  645.08
   267.7   643.8   283.7  645.64   295.6  645.55  301.32  644.36   307.6  643.41
   315.5  644.25   331.5  646.59   379.3  647.58   403.2  646.97  448.66649.6351
     459  649.12  464.99651.3659   482.9   659.8   498.8  669.46   546.6  690.04
   578.5  706.76   598.4  713.87   622.3  720.84   666.1  729.45   741.8  739.65
#Mann= 7 ,-1 , 0
       0     .12       0  137.19    .016       0  202.27     .12       0
  301.32    .045       0   315.5     .12       0  448.66    .016       0
  464.99     .12       0
#XS Ineff= 2 , 0
          244.42  648.04
Permanent Ineff=
       F       F
Bank Sta=301.32,315.5
XS Rating Curve= 0 ,0
Exp/Cntr=0.3,0.1

Type RM Length L Ch R = 1 ,50445.5 ,41.9,41.9,41.9
XS GIS Cut Line= 4
     2363768.947      376544.549     2363900.892      376466.424
     2363985.961      376357.049     2364121.378      376136.563
#Sta/Elev= 30
       0  648.15   22.69646.8674    47.2  645.69      59   645.5    78.6   644.4
   110.1  643.59   160.5 643.718   173.1  643.21     185  643.29     189  643.06
   196.9  641.76   200.8  641.49   212.7  642.02   220.6  641.68   224.6  641.87
   248.4  643.38  279.36644.3321   311.8  645.68   319.8   645.1  345.43645.2749
  358.39645.5767  387.77646.4565   415.8646.7612   435.2   646.9  468.22648.6677
     487  650.44  527.38657.5497   538.7  659.12  545.62659.4238   550.6  659.72
#Mann= 13 ,-1 , 0
       0     .06       0   22.69    .016       0   160.5     .12       0
   196.9    .045       0   224.6     .06       0  279.36    .016       0
  345.43     .06       0  358.39    .016       0  387.77     .06       0
   415.8    .016       0  468.22     .12       0  527.38     .06       0
  545.62     .12       0
#XS Ineff= 2 , 0
          120.15   645.2  260.33          645.61
Permanent Ineff=
       F       F
Bank Sta=196.9,224.6
XS Rating Curve= 0 ,0
Exp/Cntr=0.3,0.1

Type RM Length L Ch R = 1 ,50403.6 ,54.8,53.3,51.9
XS GIS Cut Line= 4
     2363789.781      376582.743     2363921.725      376504.618
     2364006.795      376395.243     2364142.211      376174.757
#Sta/Elev= 30
       0  648.16    11.8  646.94    43.2  645.22    78.6  644.44    98.3   644.3
  113.02643.7228  135.33  643.33   157.3  643.04   165.2  643.43  171.99644.2935
   177.1   644.9     181  644.98   220.6  645.13   224.6  645.01   228.6  644.26
  231.07  643.09   236.5   641.9   248.5  643.11   256.3  644.25   260.2  644.49
   291.9  644.48  437.77646.2014  462.99646.5986   490.9  647.13  496.13649.1773
   502.9  652.63   506.9   653.9   514.8   655.6  522.87656.1938   550.6  658.02
#Mann= 10 ,-1 , 0
       0     .12       0  113.02    .016       0  135.33     .06       0
  171.99    .016       0  231.07    .045       0   248.5    .016       0
  437.77     .12       0  462.99    .016       0  496.13     .12       0
  522.87     .06       0
#XS Ineff= 2 , 0
          200.26  646.02
Permanent Ineff=
       F       F
Bank Sta=231.07,248.5
XS Rating Curve= 0 ,0
Exp/Cntr=0.3,0.1

Type RM Length L Ch R = 1 ,50350.3 ,78.3,78.3,78.3
XS GIS Cut Line= 3
     2363948.418         376660.      2363985.31      376514.601
     2364168.687      376248.759
#Sta/Elev= 30
       0  687.06   13.99684.4955    19.7  683.52    31.6  679.18    43.4  676.27
    67.1  671.45    90.8  667.36    98.7  665.39   110.5  660.76   126.3  653.43
     150  644.62     166  642.26  176.24642.5928   181.9  642.29   189.9  639.85
   193.9  638.86   205.8   638.6   219.9  639.34  240.08641.5223   249.7  642.37
   273.6   641.9   317.5  643.34   369.3  643.51   399.1 644.279  420.14 645.736
   433.1  645.27     453  645.73     457  647.01  466.12653.1372     473  655.04
#Mann= 9 ,-1 , 0
       0     .12       0   13.99     .06       0  176.24     .12       0
   189.9    .045       0   219.9     .12       0  240.08     .06       0
   399.1     .12       0  420.14    .016       0  466.12     .12       0
Bank Sta=189.9,219.9
XS Rating Curve= 0 ,0
Exp/Cntr=0.3,0.1

Type RM Length L Ch R = 1 ,50272   ,71.9,75.3,78.6
XS GIS Cut Line= 3
     2364011.352      376706.658     2364048.244      376561.259
     2364231.621      376295.417
#Sta/Elev= 30
       0  687.73    67.1  677.34      79  673.71    86.8  670.43    98.7  668.03
   110.5  664.53   130.3  655.46   138.2  653.39     150  652.84     162  647.67
   185.9  640.29   193.9  638.72   205.8  637.96   221.5  638.61   225.8  640.14
   233.7  644.68   237.7  646.04   241.7  645.77   249.7  641.97   253.7   640.9
   261.6  640.04   316.2640.3928   361.3  640.39  417.35641.9763   441.1  642.34
  445.93643.9406     453  648.45     457  650.09     465  652.08     473  653.19
#Mann= 6 ,-1 , 0
       0     .12       0   193.9    .045       0   221.5     .12       0
   316.2     .06       0  417.35    .016       0  445.93     .12       0
#XS Ineff= 2 , 0
                          240.05           647.6
Permanent Ineff=
       F       F
Bank Sta=193.9,221.5
XS Rating Curve= 0 ,0
Exp/Cntr=0.3,0.1

Type RM Length L Ch R = 1 ,50196.7 ,155.6,161.3,165.8
XS GIS Cut Line= 3
     2364033.647      376718.189     2364075.313      376625.741
     2364416.083       376257.44
#Sta/Elev= 30
       0  689.36    15.6  686.26    42.9  679.56      78   669.9    97.5  663.79
   125.3  650.89   145.2  643.17   172.3  638.46     181  637.96   187.3  638.82
     197  639.82   216.9  639.27   232.8  640.28   244.8  640.18   256.7  638.58
  324.11637.9758  358.69639.5522   380.2  639.14   400.1  640.06   408.2639.6646
   431.9  641.78   435.9  642.73   439.9  644.21   451.8  649.66   479.7  658.41
   491.7  662.72   543.4  683.76   551.4  686.47   575.3  693.38   603.2   703.3
#Mann= 6 ,-1 , 0
       0     .12       0   172.3    .045       0   187.3     .12       0
  324.11     .06       0  358.69    .016       0   408.2     .12       0
#XS Ineff= 2 , 0
                          332.48          641.63
Permanent Ineff=
       F       F
Bank Sta=172.3,187.3
XS Rating Curve= 0 ,0
Exp/Cntr=0.3,0.1

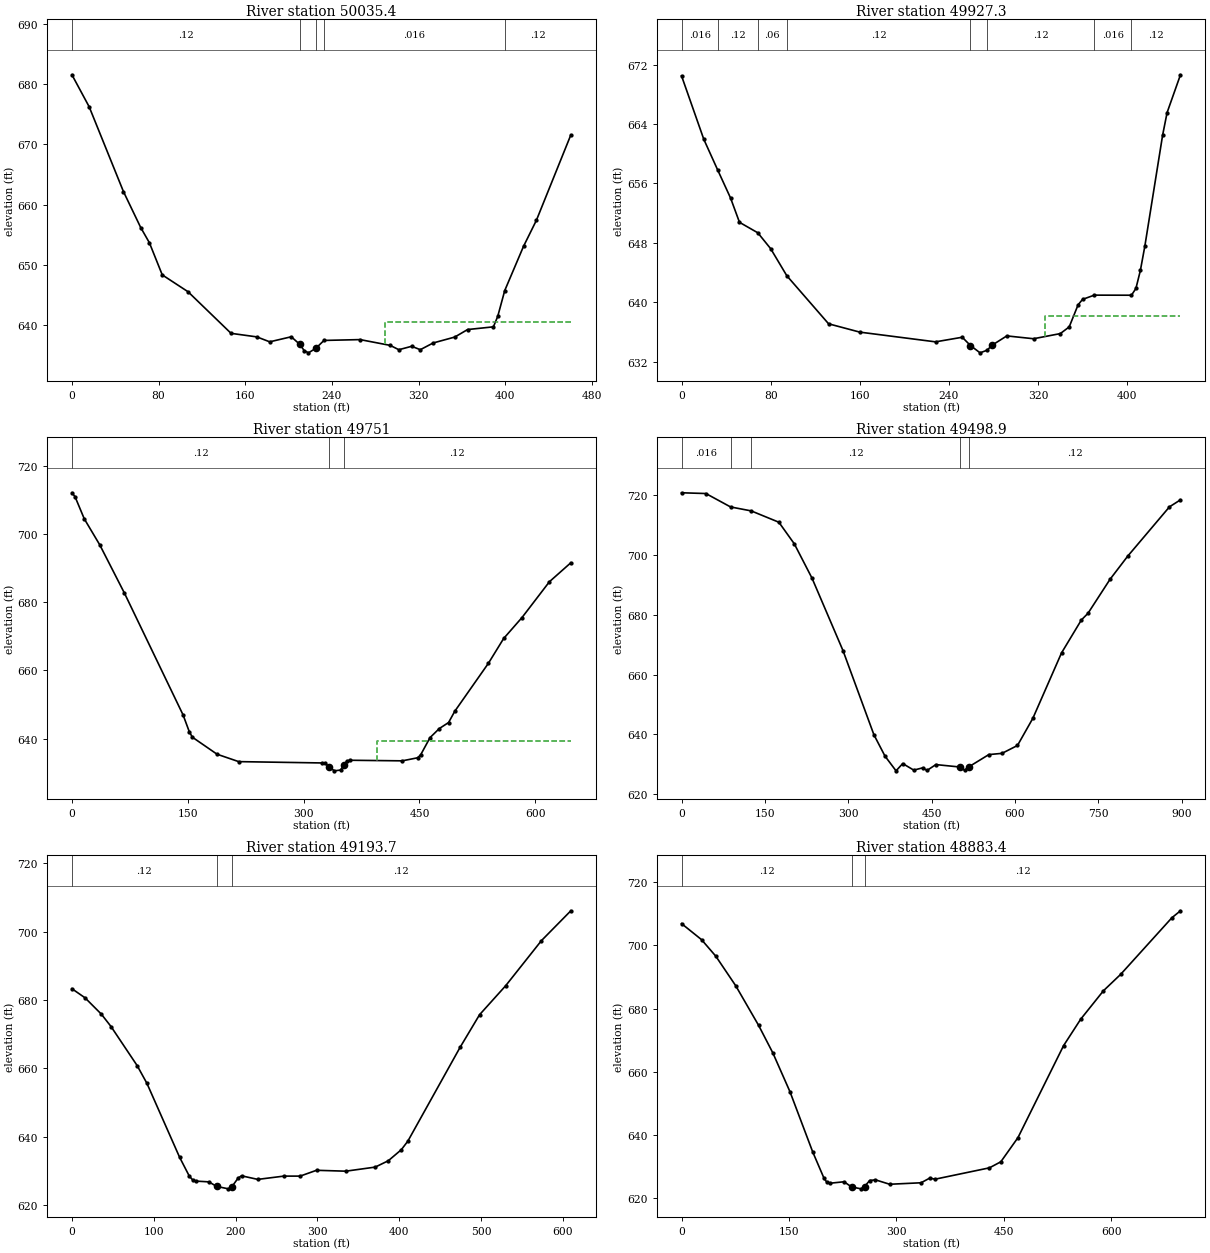
Type RM Length L Ch R = 1 ,50035.4 ,106.4,108.1,106.4
XS GIS Cut Line= 2
     2364083.126      376787.199     2364443.803      376500.741
#Sta/Elev= 30
       0  681.56    15.9  676.25    47.6  662.14    63.5  656.18    71.5  653.66
    83.4  648.31   107.2  645.51   146.9   638.6   170.7  638.01   182.6  637.19
   202.5  638.03   210.3  636.78   214.4  635.74   218.4  635.36   225.3  636.13
   232.7 637.422     266  637.56   293.8   636.6   301.8  635.88   313.7  636.45
   321.6  635.88   333.5     637   353.4  637.98   365.3  639.23   389.1  639.68
   393.1  641.41  399.57645.7073   416.9  653.05   428.8  657.38   460.6  671.57
#Mann= 5 ,-1 , 0
       0     .12       0   210.3    .045       0   225.3     .12       0
   232.7    .016       0  399.57     .12       0
#XS Ineff= 2 , 0
                          288.83          640.56
Permanent Ineff=
       F       F
Bank Sta=210.3,225.3
XS Rating Curve= 0 ,0
Exp/Cntr=0.3,0.1

Type RM Length L Ch R = 1 ,49927.3 ,169.2,176.4,181.3
XS GIS Cut Line= 2
     2364130.001      376851.002     2364490.678      376585.377
#Sta/Elev= 30
       0  670.48      20  661.93   32.42657.8129      44  654.03      52  650.76
   68.45649.3491      80  647.21   94.51643.5615     132  637.09     160  635.97
     228  634.66     252  635.28   259.4  634.16     268  633.18   274.4  633.54
  278.56  634.19     292  635.46     316  635.08     340  635.77     348  636.67
     356  639.65     360  640.38  370.55640.9515   403.9  640.94   407.9  641.85
   411.9  644.27   415.9  647.53   431.9  662.52   435.9  665.54   447.9  670.63
#Mann= 8 ,-1 , 0
       0    .016       0   32.42     .12       0   68.45     .06       0
   94.51     .12       0   259.4    .045       0   274.4     .12       0
  370.55    .016       0   403.9     .12       0
#XS Ineff= 2 , 0
                          326.06          638.09
Permanent Ineff=
       F       F
Bank Sta=259.4,278.56
XS Rating Curve= 0 ,0
Exp/Cntr=0.3,0.1

Type RM Length L Ch R = 1 ,49751   ,358.3,252,254.3
XS GIS Cut Line= 3
     2364079.219      376964.283     2364549.738      376784.542
     2364688.594      376815.845
#Sta/Elev= 30
       0  712.06       4  710.93      16  704.42      36  696.82      68  682.66
   143.9  646.99   151.9   642.1   155.9  640.46   187.9  635.47   215.9   633.3
   323.8  632.91   327.8  632.82  333.42  631.72   339.8   630.6   347.8  630.83
   351.8  632.17   355.8  633.45   359.8   633.7   427.7  633.53   447.7  634.43
   451.7  635.36   463.7  640.34   475.7  642.99   487.7  644.75   495.7  648.05
   539.3  662.12     559  669.37   582.8  675.52   618.3  686.01     646  691.56
#Mann= 3 ,-1 , 0
       0     .12       0  333.42    .045       0   351.8     .12       0
#XS Ineff= 2 , 0
                          394.48          639.26
Permanent Ineff=
       F       F
Bank Sta=333.42,351.8
XS Rating Curve= 0 ,0
Exp/Cntr=0.3,0.1

Type RM Length L Ch R = 1 ,49498.9 ,197.9,305.2,302.5
XS GIS Cut Line= 3
     2363977.873       377162.55      2364473.41      377062.376
     2364853.285      376963.438
#Sta/Elev= 30
       0  720.79    43.8  720.54   88.21716.0542  125.43714.7297   175.2  710.94
     203  703.71   234.9  692.22   290.6  668.03   346.3  639.87   366.2  632.75
   386.1  627.82   398.1  630.25     418  628.06   433.9  628.81   441.9  627.95
   457.8  629.91   501.6  629.09   509.5  627.99   517.5   629.2   553.1  633.25
   576.9  633.67   604.7   636.3   632.4  645.39     684  667.25   719.7  678.26
   731.6  680.48   771.2  691.83     803  699.57   878.3  716.09   898.1  718.43
#Mann= 5 ,-1 , 0
       0    .016       0   88.21     .06       0  125.43     .12       0
   501.6    .045       0   517.5     .12       0
Bank Sta=501.6,517.5
XS Rating Curve= 0 ,0
Exp/Cntr=0.3,0.1

Type RM Length L Ch R = 1 ,49193.7 ,318.1,310.4,303.3
XS GIS Cut Line= 2
      2364248.49      377296.314     2364830.522      377114.022
#Sta/Elev= 30
       0   683.3      16  680.65    35.9  675.89    47.8  672.25    79.7  660.85
    91.7  655.64   131.6  634.06   143.5  628.53   147.5  627.46   151.5  627.08
   167.4  626.86   176.9  625.53   191.3  624.82   195.3  625.37   203.3     628
   207.3  628.63   227.2  627.58   259.1  628.54     279  628.54     299  630.24
   334.8  629.98   370.7  631.17   386.7  633.02   402.6  636.24   410.6  638.74
   474.4  666.13   498.3   675.7   530.2  684.17     574  697.37   609.9  706.08
#Mann= 3 ,-1 , 0
       0     .12       0   176.9    .045       0   195.3     .12       0
Bank Sta=176.9,195.3
XS Rating Curve= 0 ,0
Exp/Cntr=0.3,0.1

Type RM Length L Ch R = 1 ,48883.4 ,223,231.3,234.9
XS GIS Cut Line= 2
     2364347.449      377660.897     2364907.105      377246.133
#Sta/Elev= 30
       0  706.92    27.9  701.84    47.8  696.61    75.6  687.26   107.5  674.74
   127.4  666.01   151.3  653.74   183.1  634.65     199  626.25     203  625.01
     207  624.72   226.9  625.19   237.4  623.54   250.8  622.95  255.49  623.69
   262.7  625.59   270.7   625.8   290.6   624.4   334.4  624.87   346.3  626.32
   354.3  626.02   429.9   629.6   445.8  631.52   469.7  639.16   533.4  668.29
   557.3  676.66   589.1  685.67     613  690.83   684.6  708.77   696.6  710.98
#Mann= 3 ,-1 , 0
       0     .12       0   237.4    .045       0  255.49     .12       0
Bank Sta=237.4,255.49
XS Rating Curve= 0 ,0
Exp/Cntr=0.3,0.1

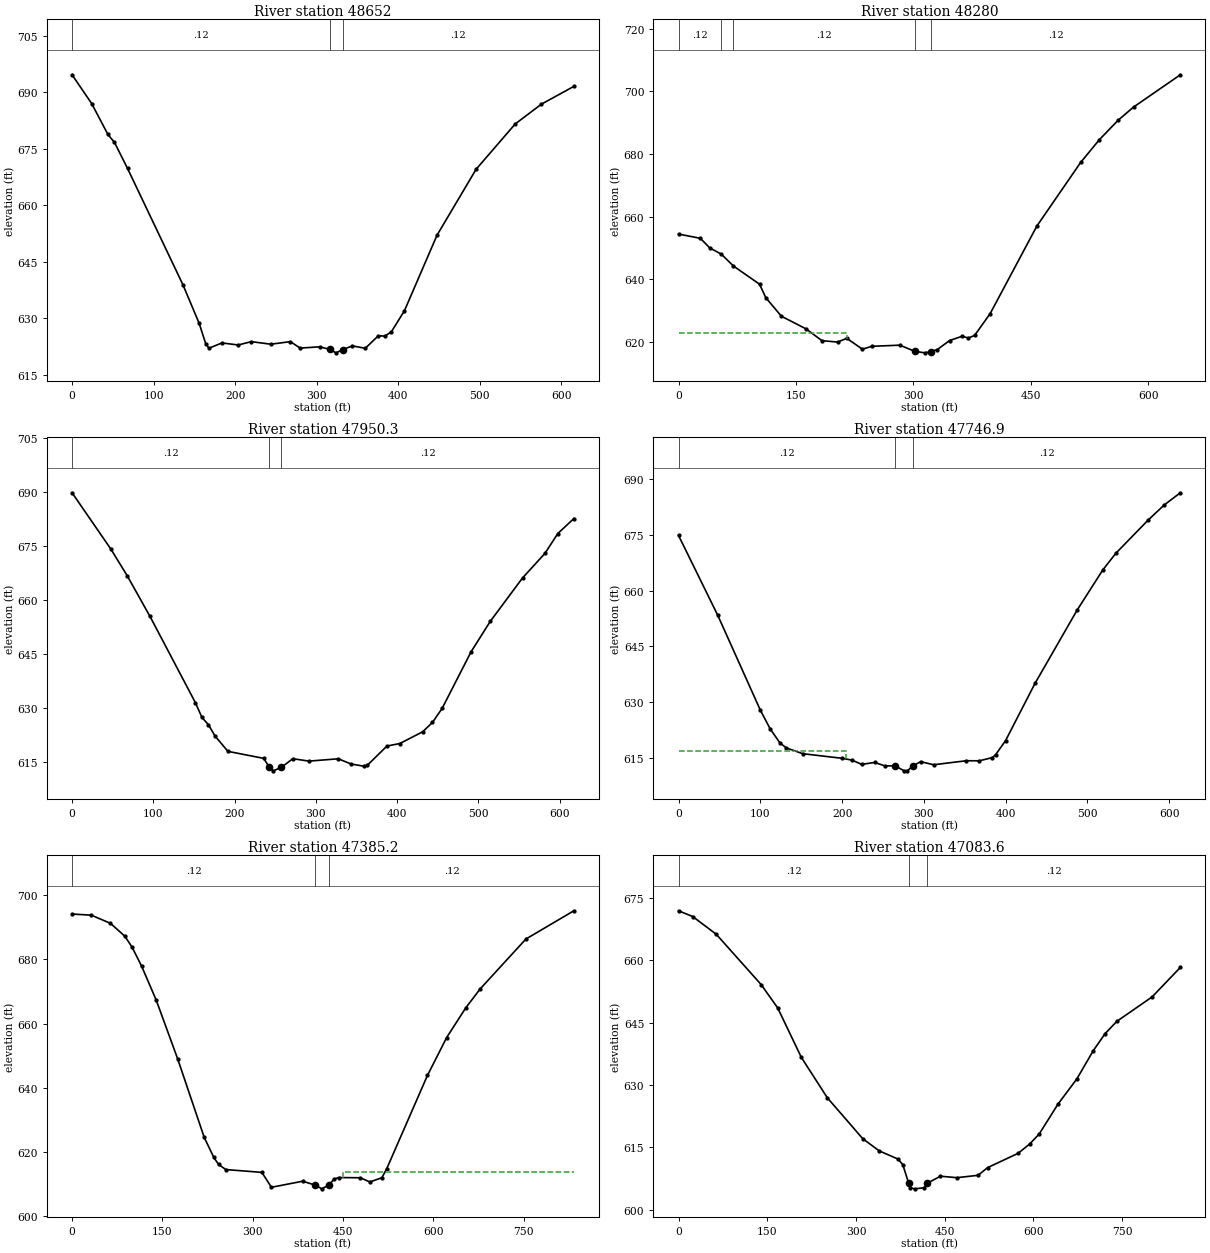
Type RM Length L Ch R = 1 ,48652   ,367,372,377.7
XS GIS Cut Line= 2
     2364452.917      377783.293     2364990.678      377483.814
#Sta/Elev= 30
       0  694.62      24     687      44  678.78      52  676.69      68  669.79
   135.9  638.96   155.9  628.68   163.9   623.3   167.9  622.09   183.9  623.49
   203.8  622.94   219.8  623.83   243.8  623.15   267.8  623.83   279.8  622.12
   303.8  622.46   315.8   621.8   323.8  620.86   331.8  621.68   343.7  622.71
   359.7  622.07   375.7  625.39   383.7  625.29   391.7  626.46   407.7  632.03
   447.7  652.08   495.6  669.56   543.6  681.58   575.6  686.81   615.5  691.54
#Mann= 3 ,-1 , 0
       0     .12       0   315.8    .045       0   331.8     .12       0
Bank Sta=315.8,331.8
XS Rating Curve= 0 ,0
Exp/Cntr=0.3,0.1

Type RM Length L Ch R = 1 ,48280   ,332.7,329.7,324.9
XS GIS Cut Line= 2
     2364562.292      378026.783     2365170.365      377823.658
#Sta/Elev= 30
       0  654.45    27.9  653.09    39.8  650.04   54.62648.0419   70.18644.2364
   103.5  638.44   111.5  634.13   131.4  628.21   163.3  624.12   183.2  620.41
   203.1  619.96     215  621.15   234.9  617.69   246.9   618.6   282.7  618.97
   301.7  617.02   314.6  616.52   322.5  616.94   330.5  617.55   346.4  620.46
   362.4  621.82   370.3  621.24   378.3  622.09   398.2  629.07   457.9  657.04
   513.7   677.3   537.6  684.56   561.5  690.76   581.4  695.01   641.1  705.31
#Mann= 5 ,-1 , 0
       0     .12       0   54.62     .06       0   70.18     .12       0
   301.7    .045       0   322.5     .12       0
#XS Ineff= 2 , 0
          215.66  622.81
Permanent Ineff=
       F       F
Bank Sta=301.7,322.5
XS Rating Curve= 0 ,0
Exp/Cntr=0.3,0.1

Type RM Length L Ch R = 1 ,47950.3 ,203.3,203.4,203.8
XS GIS Cut Line= 3
     2364611.772      378249.439     2365036.251      378073.658
     2365126.094      377943.449
#Sta/Elev= 30
       0   689.7    47.9  674.05    67.9  666.71    95.9  655.46   151.8  631.56
   159.8  627.49   167.8  625.47   175.8  622.37   191.8  618.08   235.7  616.14
   242.7  613.77   247.7  612.68   257.7  613.67   271.7  616.04   291.6  615.37
   327.6  616.02   343.6  614.56   359.6  613.95   363.6  614.25   387.5  619.54
   403.5  620.25   431.5   623.5   443.5  626.07   455.4  629.95   491.1  645.66
   514.8  654.11   554.4   666.1     582  672.91   597.9  678.42   617.6  682.56
#Mann= 3 ,-1 , 0
       0     .12       0   242.7    .045       0   257.7     .12       0
Bank Sta=242.7,257.7
XS Rating Curve= 0 ,0
Exp/Cntr=0.3,0.1

Type RM Length L Ch R = 1 ,47746.9 ,361,361.6,353.7
XS GIS Cut Line= 3
     2364709.428      378414.804     2365126.094      378250.741
     2365291.459      378240.324
#Sta/Elev= 30
       0  674.87      48  653.33     100   627.8     112  622.77     124  618.95
   131.9  617.61   151.9  616.06   199.9  614.82   211.9  614.34   223.9  613.19
   239.9   613.7   251.9   612.8     265  612.76   275.9  611.44   279.9  611.49
  286.57  612.74   295.9  613.92   311.9  613.08   351.8  614.16   367.8  614.14
   383.8  615.02   387.8  615.83   399.8  619.57   435.8  634.99   487.2  654.71
   518.8   665.6   534.6  670.05     574  678.98   593.8  683.08   613.5  686.37
#Mann= 3 ,-1 , 0
       0     .12       0     265    .045       0  286.57     .12       0
#XS Ineff= 2 , 0
          204.88  616.73
Permanent Ineff=
       F       F
Bank Sta=265,286.57
XS Rating Curve= 0 ,0
Exp/Cntr=0.3,0.1

Type RM Length L Ch R = 1 ,47385.2 ,304.1,301.7,299
XS GIS Cut Line= 3
     2364697.041      378732.094      2365077.92      378577.555
     2365474.156      378430.665
#Sta/Elev= 30
       0  694.16    31.9  693.82    63.8  691.26    87.8  687.23    99.8   683.8
   115.7  677.85   139.7  667.37   175.6  648.93   219.5  624.55   235.4  618.31
   243.4   616.1   255.4  614.51   315.3  613.63   331.2  608.98   383.1  610.88
   403.5  609.69     415   608.5     427  609.74     435   611.5   442.9  612.02
   478.8  611.95   494.8  610.64   514.7  611.97   522.7  614.76   590.4  643.86
   622.3  655.67   654.2  664.97   678.1  670.85   753.9  686.37   833.6  695.18
#Mann= 3 ,-1 , 0
       0     .12       0   403.5    .045       0     427     .12       0
#XS Ineff= 2 , 0
                          450.58           613.9
Permanent Ineff=
       F       F
Bank Sta=403.5,427
XS Rating Curve= 0 ,0
Exp/Cntr=0.3,0.1

Type RM Length L Ch R = 1 ,47083.6 ,263.1,265.9,263.7
XS GIS Cut Line= 3
      2364778.78       379026.98     2365134.263      378836.971
     2365538.619      378650.994
#Sta/Elev= 30
       0  671.96      24  670.57    63.8   666.3   139.7  654.18   167.6  648.57
   207.5  636.68   251.4  626.95   311.3  617.09   339.2  614.14   371.2  612.16
   379.1  610.81  388.72  606.49   391.1  605.29   399.1     605     415  605.26
  420.69  606.38   442.8  608.04   470.6  607.69   506.4  608.26   522.3   610.1
     574  613.55   593.8  615.83   609.7  618.22   641.5  625.42   673.3  631.47
   701.1  638.29     721  642.37   740.9  645.34   800.5  651.22   848.2  658.32
#Mann= 3 ,-1 , 0
       0     .12       0  388.72    .045       0  420.69     .12       0
Bank Sta=388.72,420.69
XS Rating Curve= 0 ,0
Exp/Cntr=0.3,0.1

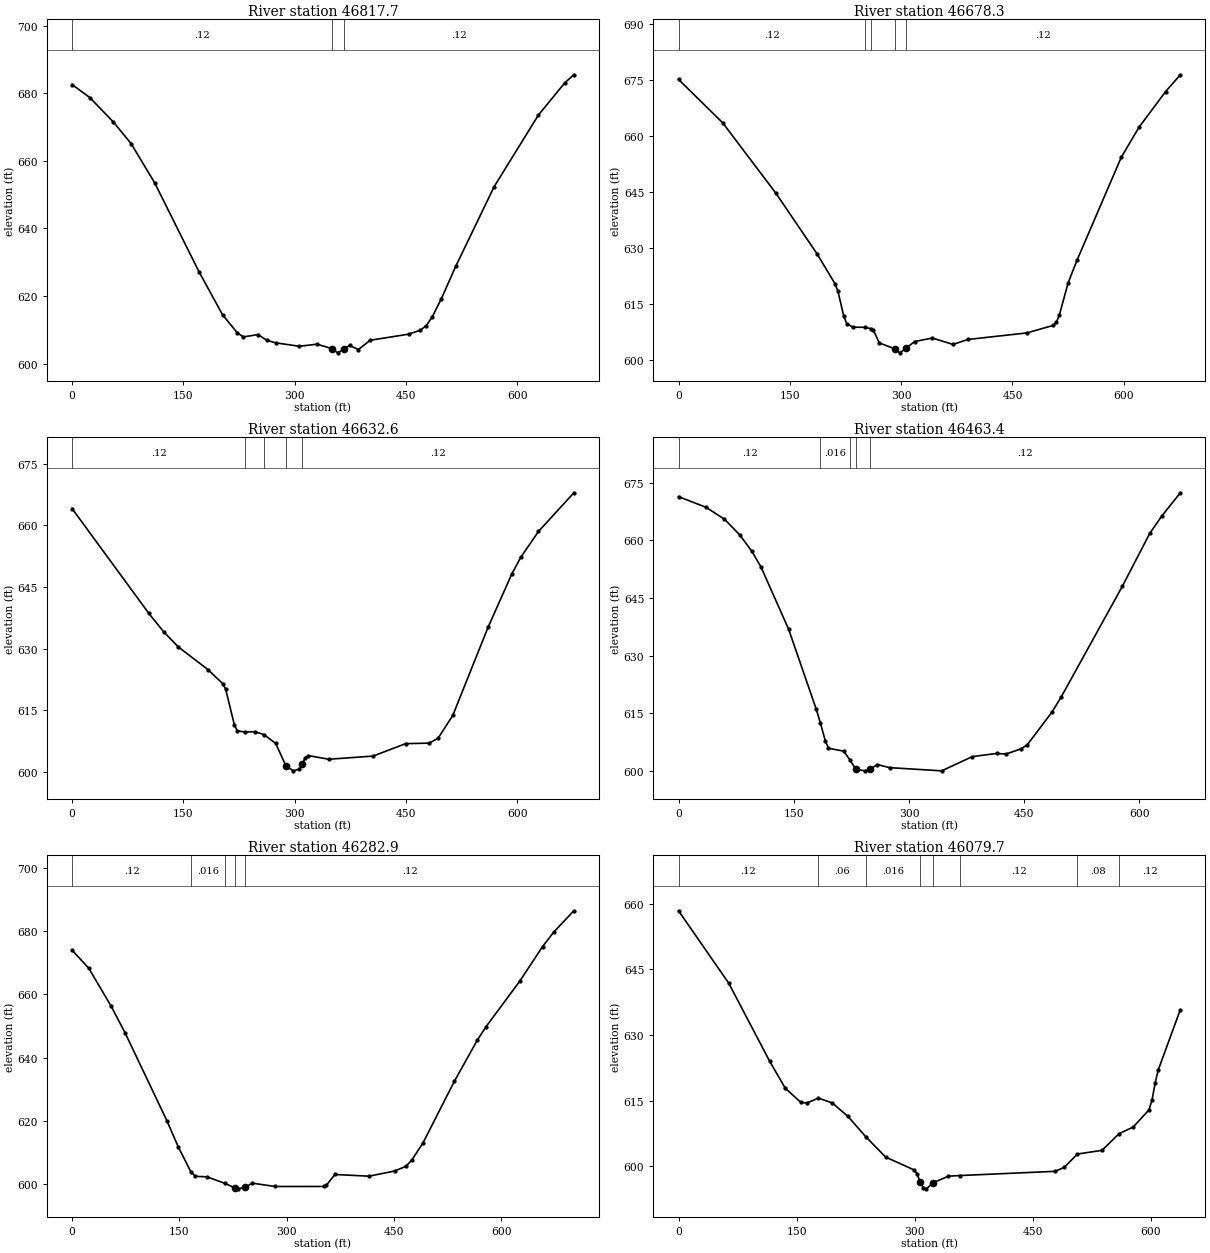
Type RM Length L Ch R = 1 ,46817.7 ,137.6,139.4,140.4
XS GIS Cut Line= 2
     2364964.636      379133.554     2365597.449      378895.272
#Sta/Elev= 30
       0  682.53    23.9   678.7    55.7  671.46    79.6  665.06   111.4  653.44
     171   627.2   202.9  614.42   222.7  609.11   230.7  607.91   250.6   608.6
   262.5   606.9   274.4  606.16   306.3  605.14   330.1  605.76     350  604.46
     358   603.2   365.9  604.26   373.9   605.4   385.8  604.17   401.7  606.92
   453.4  608.72   469.4   609.9   477.3  611.24   485.3  613.84   497.2     619
   517.1  628.82   568.8  652.36   628.5  673.54   664.2  683.11   676.2  685.43
#Mann= 3 ,-1 , 0
       0     .12       0     350    .045       0   365.9     .12       0
Bank Sta=350,365.9
XS Rating Curve= 0 ,0
Exp/Cntr=0.3,0.1

Type RM Length L Ch R = 1 ,46678.3 ,45.7,45.7,45.7
XS GIS Cut Line= 2
     2364994.844      379223.137     2365627.657      378984.856
#Sta/Elev= 30
       0  675.12    59.7  663.48   131.3  644.67     187   628.4   210.8   620.5
   214.8  618.52   222.7  611.77   226.7  609.87   234.7  608.88  251.01608.8567
  259.54608.4778   262.5  608.13   270.5  604.68   291.4  603.11   298.3  602.03
   306.4  603.24   318.2  605.06   342.1  605.98   369.9  604.28   389.8   605.6
   469.4  607.35   505.2  609.38   509.1  610.18   513.1  612.08     525  620.73
     537   626.8   596.6   654.3   620.5  662.33   656.3  671.85   676.2  676.36
#Mann= 5 ,-1 , 0
       0     .12       0  251.01    .016       0  259.54     .12       0
   291.4    .045       0   306.4     .12       0
Bank Sta=291.4,306.4
XS Rating Curve= 0 ,0
Exp/Cntr=0.3,0.1

Type RM Length L Ch R = 1 ,46632.6 ,169.3,169.2,169.3
XS GIS Cut Line= 2
     2365015.157      379264.283     2365647.969      379026.002
#Sta/Elev= 30
       0  664.12   103.4  638.59   123.3  634.14   143.2  630.41     183  624.92
   202.9  621.49   206.8  620.23   218.8  611.38   222.7  609.99  232.81609.6944
   246.6  609.77  258.56609.0732   274.4  606.91   288.3  601.41   298.3  600.24
   306.3  600.67   310.2  601.86   314.2  603.46   318.2  603.96     346  603.06
   405.7  603.84   449.5  606.86   481.3  606.99   493.2  608.17   513.1  613.76
   560.8   635.3   592.7  648.22   604.6  652.24   628.5  658.53   676.2  667.96
#Mann= 5 ,-1 , 0
       0     .12       0  232.81    .016       0  258.56     .12       0
   288.3    .045       0   310.2     .12       0
Bank Sta=288.3,310.2
XS Rating Curve= 0 ,0
Exp/Cntr=0.3,0.1

Type RM Length L Ch R = 1 ,46463.4 ,182,180.5,178.9
XS GIS Cut Line= 2
     2365119.931      379405.081     2365731.436      379175.327
#Sta/Elev= 30
       0  671.41    35.8  668.62    59.8  665.53    79.7  661.43    95.6  657.12
   107.6  652.96   143.4   636.8   179.2  616.04  184.72612.3576   191.2  607.67
   195.2  605.83   215.1  605.07  223.17602.7343     231  600.33     243  599.94
   249.4  600.38   258.9  601.58   274.8  600.77   342.6  599.94   382.4  603.65
   414.2  604.47   426.2  604.31   446.1  605.69   454.1  606.76     486  615.22
   497.9  619.11   577.6  647.99   613.4  661.82   629.3  666.41   653.2  672.41
#Mann= 5 ,-1 , 0
       0     .12       0  184.72    .016       0  223.17     .12       0
     231    .045       0   249.4     .12       0
Bank Sta=231,249.4
XS Rating Curve= 0 ,0
Exp/Cntr=0.3,0.1

Type RM Length L Ch R = 1 ,46282.9 ,207.7,203.1,198.5
XS GIS Cut Line= 3
     2365208.907      379501.653     2365340.514      379518.609
     2365856.891      379280.586
#Sta/Elev= 30
       0  673.97    23.4  668.25    54.6  656.29    74.2  647.81   132.7  620.04
   148.6  611.76  166.01604.0029   172.5  602.54   188.4   602.4  213.21600.3667
   227.2  598.93   232.1   598.6   242.2  599.15     252  600.39   283.8  599.34
   351.4  599.35   355.4  599.73   367.3  603.13     415   602.6   450.8  604.22
   466.7  605.74   474.6  607.64   490.6  613.17   534.3  632.56   566.1  645.46
     578  649.64   625.7  664.19   657.6  675.13   673.5  679.77   701.3  686.42
#Mann= 5 ,-1 , 0
       0     .12       0  166.01    .016       0  213.21     .12       0
   227.2    .045       0   242.2     .12       0
Bank Sta=227.2,242.2
XS Rating Curve= 0 ,0
Exp/Cntr=0.3,0.1

Type RM Length L Ch R = 1 ,46079.7 ,67.3,68.8,70.3
XS GIS Cut Line= 3
     2365230.608       379623.18     2365500.791      379675.264
     2365792.674       379460.42
#Sta/Elev= 30
       0  658.41    63.8  641.86   115.6  624.09   135.6  617.86   155.5  614.61
   163.5  614.49   177.6615.6185   195.4  614.49   215.3  611.42  237.91606.7733
   263.2  602.12     299  599.22     303  598.33     307  596.46     311  595.15
     315  594.87     323  596.22   342.9  597.76  357.05597.9031   478.3  598.87
   490.2  599.78  506.76602.8215     538  603.66   559.8 607.479   577.8     609
   597.8  612.93   601.7  615.21   605.7  619.14   609.7  622.12   637.6  635.81
#Mann= 8 ,-1 , 0
       0     .12       0   177.6     .06       0  237.91    .016       0
     307    .045       0     323    .016       0  357.05     .12       0
  506.76     .08       0   559.8     .12       0
Bank Sta=307,323
XS Rating Curve= 0 ,0
Exp/Cntr=0.3,0.1

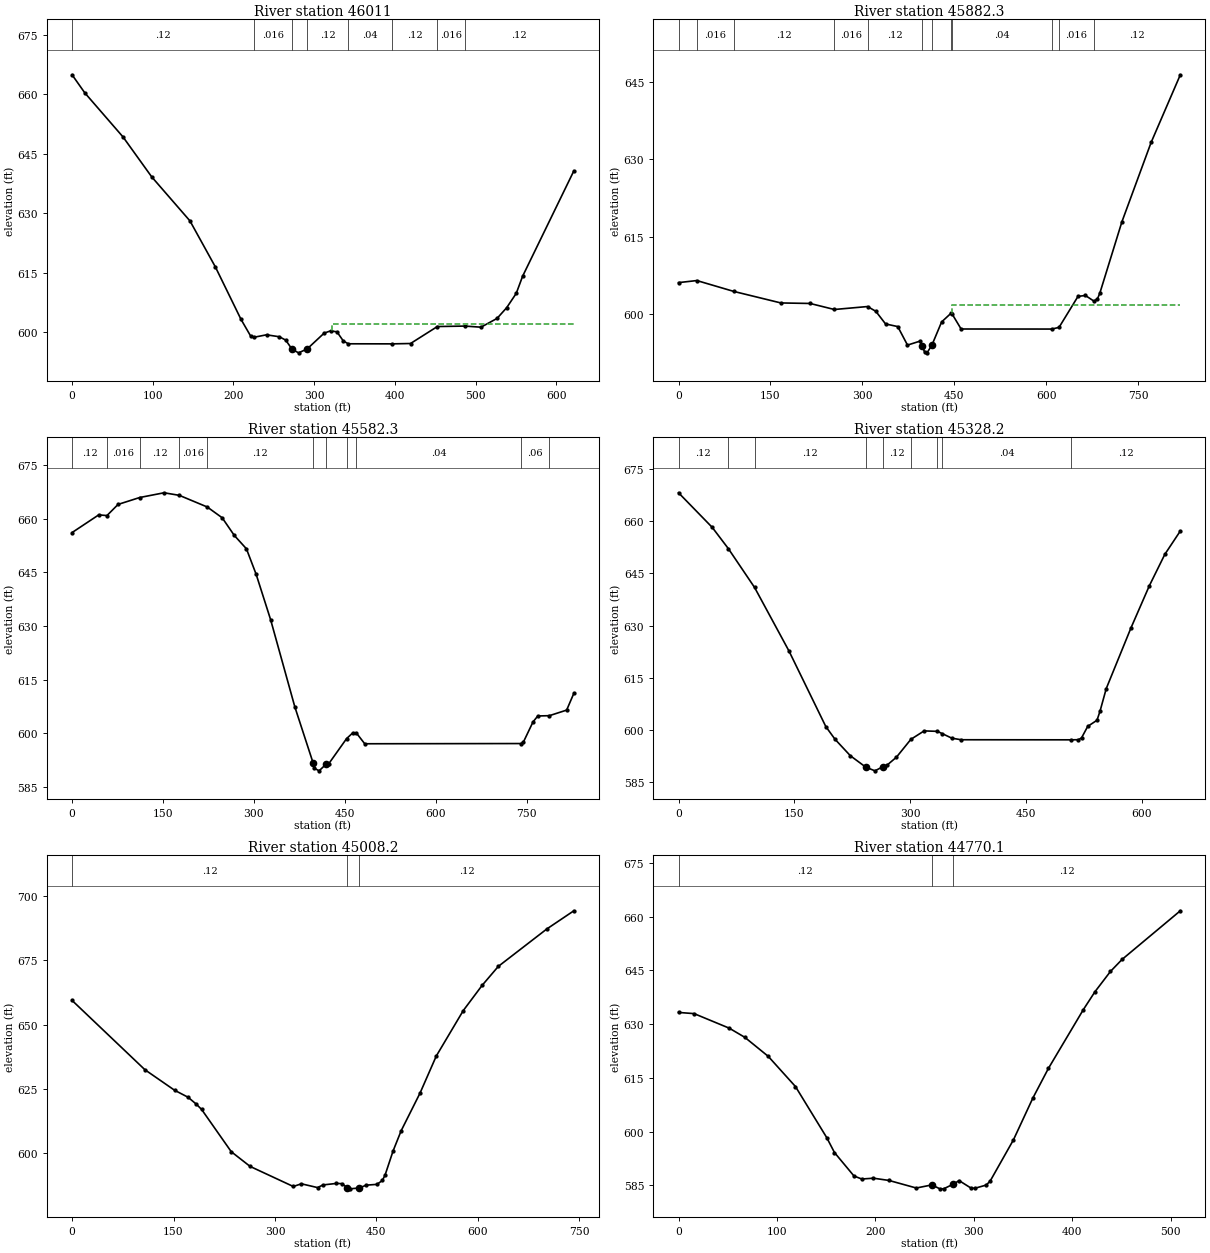
Type RM Length L Ch R = 1 ,46011   ,129,128.7,128.4
XS GIS Cut Line= 3
     2365303.308      379802.217     2365523.577      379739.283
     2365854.523      379527.694
#Sta/Elev= 30
       0  664.88    15.8  660.32    63.2  649.21    98.7  639.17   146.1  628.08
   177.7  616.45   209.3  603.31   221.2  599.12  225.76598.7864     241  599.39
   256.9   598.9   264.8  598.05   272.7  595.74   280.7  594.85   291.3  595.82
   312.4  599.81   320.3  600.38   328.3  600.14   336.2  597.83  342.42597.1278
  396.46  597.11   419.5   597.2  452.73601.4744  486.99601.5905   506.8  601.31
   526.7  603.52   538.6  606.21   550.5  609.83   558.4  614.15   621.9  640.68
#Mann= 8 ,-1 , 0
       0     .12       0  225.76    .016       0   272.7    .045       0
   291.3     .12       0  342.42     .04       0  396.46     .12       0
  452.73    .016       0  486.99     .12       0
#XS Ineff= 2 , 0
                          322.59          602.04
Permanent Ineff=
       F       F
Bank Sta=272.7,291.3
XS Rating Curve= 0 ,0
Exp/Cntr=0.3,0.1

Type RM Length L Ch R = 1 ,45882.3 ,309.8,300,292.3
XS GIS Cut Line= 3
      2365300.41       380041.03     2365642.508      379815.951
     2365984.121       379590.14
#Sta/Elev= 30
       0  606.11   29.86606.5091    90.2604.4023     167  602.17   214.7  602.07
  254.32600.9005  308.52 601.473     322  600.55   337.9   598.1   357.8  597.59
   373.7     594   393.6  594.75   397.6  593.92   401.6  592.64   405.5   592.5
   413.5  593.98   429.4  598.49   444.6600.1565  446.03600.1235   461.2  597.12
  609.34  597.11  621.03597.4336     652  603.44     664  603.62  678.13602.5115
   683.8  602.96   687.8  604.13   723.6  617.88   771.3  633.27     819  646.39
#Mann= 12 ,-1 , 0
       0     .12       0   29.86    .016       0    90.2     .12       0
  254.32    .016       0  308.52     .12       0   397.6    .045       0
   413.5     .12       0   444.6     .06       0  446.03     .04       0
  609.34     .12       0  621.03    .016       0  678.13     .12       0
#XS Ineff= 2 , 0
                          446.73          601.71
Permanent Ineff=
       F       F
Bank Sta=397.6,413.5
XS Rating Curve= 0 ,0
Exp/Cntr=0.3,0.1

Type RM Length L Ch R = 1 ,45582.3 ,259.1,254,247.3
XS GIS Cut Line= 3
     2365613.675      380396.961     2365826.199      380049.196
      2366080.39      379714.248
#Sta/Elev= 30
       0   656.1      44  661.04   57.57660.8468    75.9  663.96  111.71665.8905
   151.8  667.21  176.97666.4932  223.05663.2425   247.7  660.23   267.7   655.3
   287.7  651.57   303.7  644.47   327.6  631.79   367.6  607.42  398.02  591.63
   399.6  590.33   407.6  589.57   419.5  591.48   423.4  591.52  453.07598.5912
   463.1  600.15  469.27600.1121   482.9  597.13  741.31597.1902   744.7  597.59
   760.6  603.23   768.5  604.89  787.54604.9714   816.1  606.53     828  611.22
#Mann= 11 ,-1 , 0
       0     .12       0   57.57    .016       0  111.71     .12       0
  176.97    .016       0  223.05     .12       0  398.02    .045       0
   419.5     .12       0  453.07     .06       0  469.27     .04       0
  741.31     .06       0  787.54     .12       0
Bank Sta=398.02,419.5
XS Rating Curve= 0 ,0
Exp/Cntr=0.3,0.1

Type RM Length L Ch R = 1 ,45328.2 ,309.3,320,330
XS GIS Cut Line= 3
     2365969.541      380399.005     2366068.282      380113.632
     2366306.997      379860.811
#Sta/Elev= 30
       0  668.23    43.7  658.25   64.42652.1743   98.48640.9623     143  622.68
   190.7  600.92   202.6  597.27   222.5  592.52   242.4  589.25   254.3  588.18
   264.2  589.33   270.2  589.86   282.1   592.1  300.83597.2497     318  599.68
  335.26599.5466  341.72598.8621   353.9  597.58   365.9  597.13  508.61  597.11
   517.8  597.14   521.8  597.67   529.8  600.98   541.8  602.74   545.8  605.41
   553.8  611.87   585.7  629.28   609.7  641.52   629.7  650.53   649.7  657.23
#Mann= 9 ,-1 , 0
       0     .12       0   64.42    .016       0   98.48     .12       0
   242.4    .045       0   264.2     .12       0  300.83     .04       0
  335.26     .06       0  341.72     .04       0  508.61     .12       0
Bank Sta=242.4,264.2
XS Rating Curve= 0 ,0
Exp/Cntr=0.3,0.1

Type RM Length L Ch R = 1 ,45008.2 ,238.8,238.1,230.5
XS GIS Cut Line= 2
     2366054.176      380467.364     2366586.945      379950.871
#Sta/Elev= 30
       0   659.4   107.7  632.41   151.6  624.41   171.5  621.69   183.5  619.04
   191.5  616.96   235.4  600.47   263.3  594.74   327.1  586.93   339.1  587.97
     363   586.5     371  587.53     391  588.12   398.9  588.03   406.9  586.47
   410.9  586.01   424.8  586.35   434.8  587.44   450.8  587.75   458.8  589.27
   462.8  591.34   474.7  600.78   486.7  608.68   514.6  623.34   538.6  637.76
   578.5  655.46   606.4  665.28   630.3  672.66   702.1  687.25     742  694.32
#Mann= 3 ,-1 , 0
       0     .12       0   406.9    .045       0   424.8     .12       0
Bank Sta=406.9,424.8
XS Rating Curve= 0 ,0
Exp/Cntr=0.3,0.1

Type RM Length L Ch R = 1 ,44770.1 ,379.3,383,387.1
XS GIS Cut Line= 3
      2366269.02      380509.682     2366471.928       380320.88
     2366639.028      380159.205
#Sta/Elev= 30
       0  633.29    15.8  632.96    51.5   628.9    67.3  626.35    91.1  621.04
   118.8   612.6   150.5  598.37   158.4  594.19   178.2  587.65   186.1   586.8
     198  587.03   213.8   586.4   241.5  584.29   257.4  585.16   265.3  584.08
   269.2  584.06  278.91  585.34     285  586.36   296.9   584.3   300.8   584.2
   312.6  585.12   316.6  586.26   340.2  597.74   359.9  609.39   375.7  617.67
   411.2  634.08     423  639.07   438.7  644.72   450.6   648.1   509.7  661.66
#Mann= 3 ,-1 , 0
       0     .12       0   257.4    .045       0  278.91     .12       0
Bank Sta=257.4,278.91
XS Rating Curve= 0 ,0
Exp/Cntr=0.3,0.1