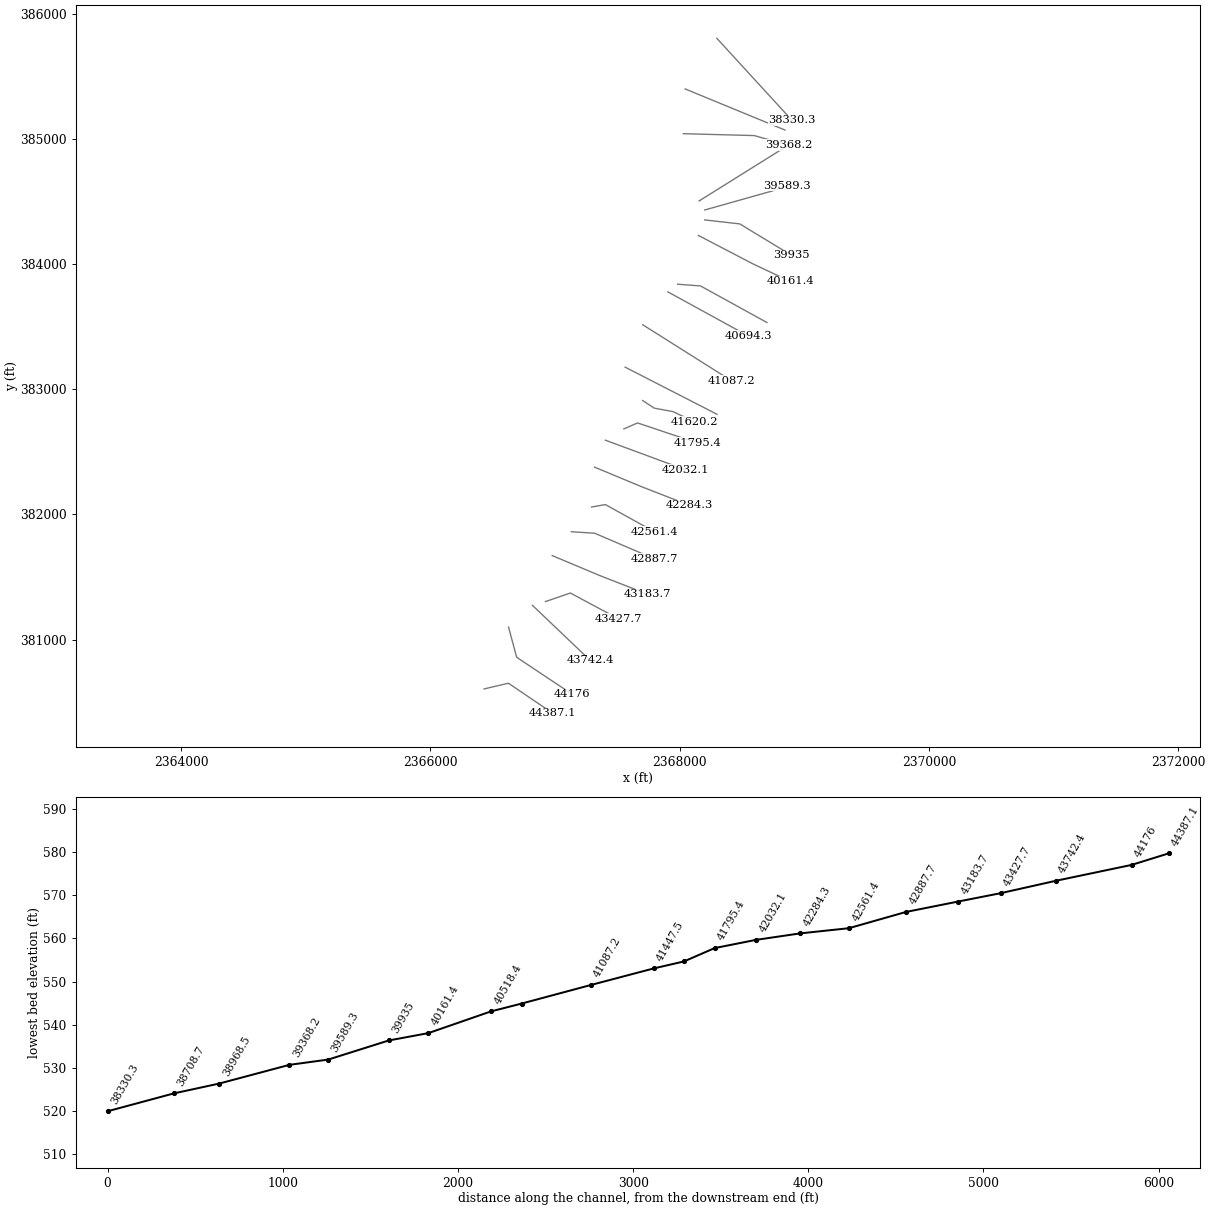
HEC-RAS study TILHANCECK.prj: TILHANCECK

--- TILHANCECK.g01 (geometry) --- (continued)

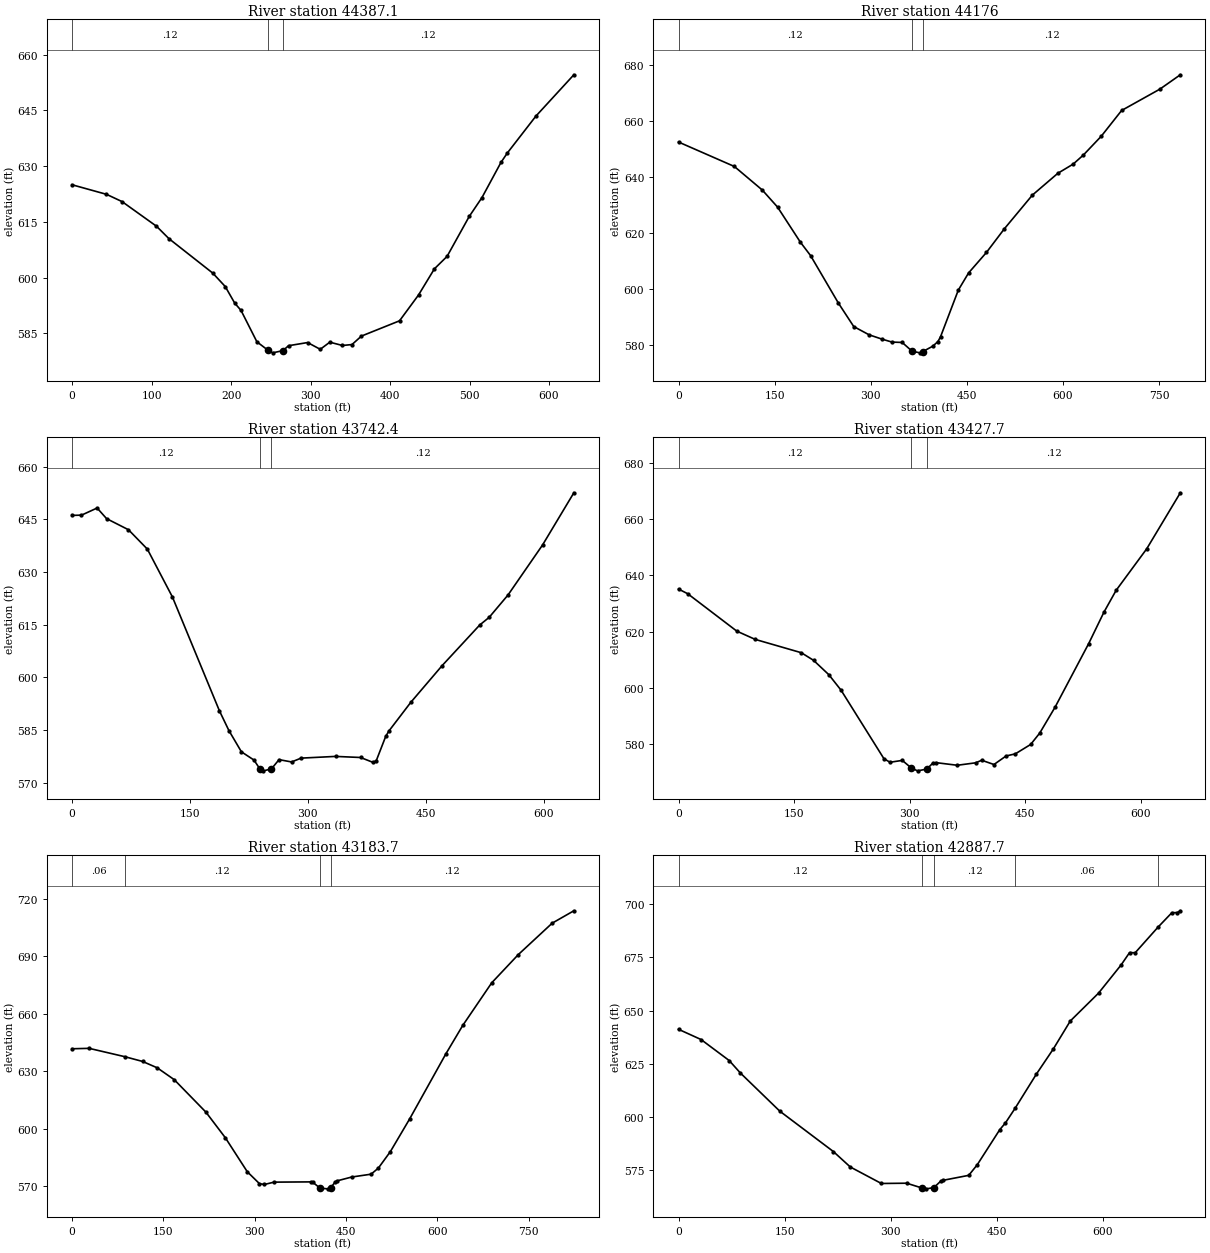
Type RM Length L Ch R = 1 ,44387.1 ,210.7,211.1,211.3
XS GIS Cut Line= 3
     2366430.695      380606.253     2366626.008      380651.826
     2366982.995      380410.941
#Sta/Elev= 30
       0  624.96    43.3  622.39    62.9  620.43   106.2   613.8   121.9  610.45
     177  601.18   192.7  597.56   204.6   593.1   212.5  591.15   232.5  582.69
  246.76  580.37   252.4  579.72   265.3  580.32   272.3  581.64   296.3  582.49
   312.2  580.67   324.2  582.59   340.1   581.7   352.1  581.95     364  584.23
   411.9  588.34   435.8  595.29   455.8  602.34   471.7  605.68   499.6  616.44
   515.6  621.51   539.5  630.97   547.5  633.51   583.4  643.43   631.2  654.57
#Mann= 3 ,-1 , 0
       0     .12       0  246.76    .045       0   265.3     .12       0
Bank Sta=246.76,265.3
XS Rating Curve= 0 ,0
Exp/Cntr=0.3,0.1

Type RM Length L Ch R = 1 ,44176   ,433.8,433.5,430.2
XS GIS Cut Line= 3
     2366627.093       381099.96     2366692.197      380859.074
     2367136.778      380564.294
#Sta/Elev= 30
       0  652.53    87.1  643.78   130.7  635.34   154.5  629.24   190.1  616.68
     206  611.88   249.5  594.84   273.4  586.46   297.3  583.51   317.2  581.98
   333.1   580.9     349  580.77   364.6   577.6   376.9  577.05   380.9  577.48
   396.8  579.44   404.8  581.11   408.8  582.79   436.6  599.53   452.6  605.66
   480.4  612.98   508.3  621.43   552.1  633.52   591.9  641.34   615.8  644.63
   631.7  647.87   659.6   654.6   691.4  663.83   751.1  671.47     783  676.61
#Mann= 3 ,-1 , 0
       0     .12       0   364.6    .045       0   380.9     .12       0
Bank Sta=364.6,380.9
XS Rating Curve= 0 ,0
Exp/Cntr=0.3,0.1

Type RM Length L Ch R = 1 ,43742.4 ,308.5,314.7,320.6
XS GIS Cut Line= 2
      2366819.15      381273.571     2367282.475      380834.118
#Sta/Elev= 30
       0  646.11      12  646.18    31.9  648.21    43.9  645.19    71.8  642.02
    95.8  636.51   127.7  622.88   187.6  590.42   199.6  584.83   215.5  578.78
   231.5  576.43   238.7  574.02   243.5  573.36   253.7  573.91   263.4  576.55
   279.4  575.89   291.4  576.98   335.3  577.47   367.2  577.16   383.2  575.75
   387.1  576.23   399.1  583.14   403.1  584.67     431  592.85     471  603.34
   518.8  614.89   530.8  617.07   554.8  623.44   598.7  637.66   638.6  652.55
#Mann= 3 ,-1 , 0
       0     .12       0   238.7    .045       0   253.7     .12       0
Bank Sta=238.7,253.7
XS Rating Curve= 0 ,0
Exp/Cntr=0.3,0.1

Type RM Length L Ch R = 1 ,43427.7 ,241.6,244,245.7
XS GIS Cut Line= 3
     2366923.317      381303.953     2367122.969      381372.312
     2367511.424      381165.064
#Sta/Elev= 30
       0  635.09      12  633.41    75.6  620.14    99.5   617.2   159.3  612.47
   175.2  609.77   195.1  604.65     211  599.13   266.6   574.8   274.5  573.54
   290.4   574.2   302.3  571.47   310.2  570.49   322.1   571.1     330   573.2
     334  573.41   361.8  572.47   385.6  573.34   393.5  574.25   409.4  572.74
   425.2  575.78   437.1  576.52     457  579.86   468.8   583.9   488.7   593.1
   532.3  615.68   552.2   626.9     568  634.64   607.7   649.4   651.3   669.3
#Mann= 3 ,-1 , 0
       0     .12       0   302.3    .045       0   322.1     .12       0
Bank Sta=302.3,322.1
XS Rating Curve= 0 ,0
Exp/Cntr=0.3,0.1

Type RM Length L Ch R = 1 ,43183.7 ,296.2,295.9,295.3
XS GIS Cut Line= 3
     2366977.631      381671.099     2367361.153      381510.934
     2367741.803      381362.907
#Sta/Elev= 30
       0  641.68      28   641.9   86.51637.5486   115.9  635.05   139.9  631.72
   167.8  625.54   219.8  608.59   251.8  595.17   287.7  577.48   307.7  571.25
   315.7  570.81   331.7  572.04   391.6  572.17   395.6  571.88   407.2  568.91
   419.6  568.54  424.55  569.02   431.5  571.92   435.4  572.72   459.2  574.71
     491  576.19   502.9  579.35   522.7  587.98   554.4  605.08   613.9  639.07
   641.6  653.89   689.2  676.15   732.8  690.86   788.4  707.26     824  713.73
#Mann= 4 ,-1 , 0
       0     .06       0   86.51     .12       0   407.2    .045       0
  424.55     .12       0
Bank Sta=407.2,424.55
XS Rating Curve= 0 ,0
Exp/Cntr=0.3,0.1

Type RM Length L Ch R = 1 ,42887.7 ,328.5,326.4,324
XS GIS Cut Line= 3
      2367131.65      381861.679     2367318.282      381849.743
     2367798.968      381644.665
#Sta/Elev= 30
       0  641.19    31.8  636.39    71.6  626.51    87.5  620.62   143.2  602.68
   218.9   583.7   242.9  576.42   286.8  568.66   322.6  568.79  344.41  566.52
   350.6  566.14   361.2  566.75   370.5  569.68   374.5  570.18   410.4  572.49
   422.4  577.46   454.3  593.99   462.3  597.16  475.86603.9926   506.2  620.19
   530.1     632     554   645.1   593.9  658.19   625.8  671.44   637.8  677.26
   645.8  677.22  677.94 689.205   697.6  696.03   705.6  696.11   709.6  696.95
#Mann= 5 ,-1 , 0
       0     .12       0  344.41    .045       0   361.2     .12       0
  475.86     .06       0  677.94     .12       0
Bank Sta=344.41,361.2
XS Rating Curve= 0 ,0
Exp/Cntr=0.3,0.1

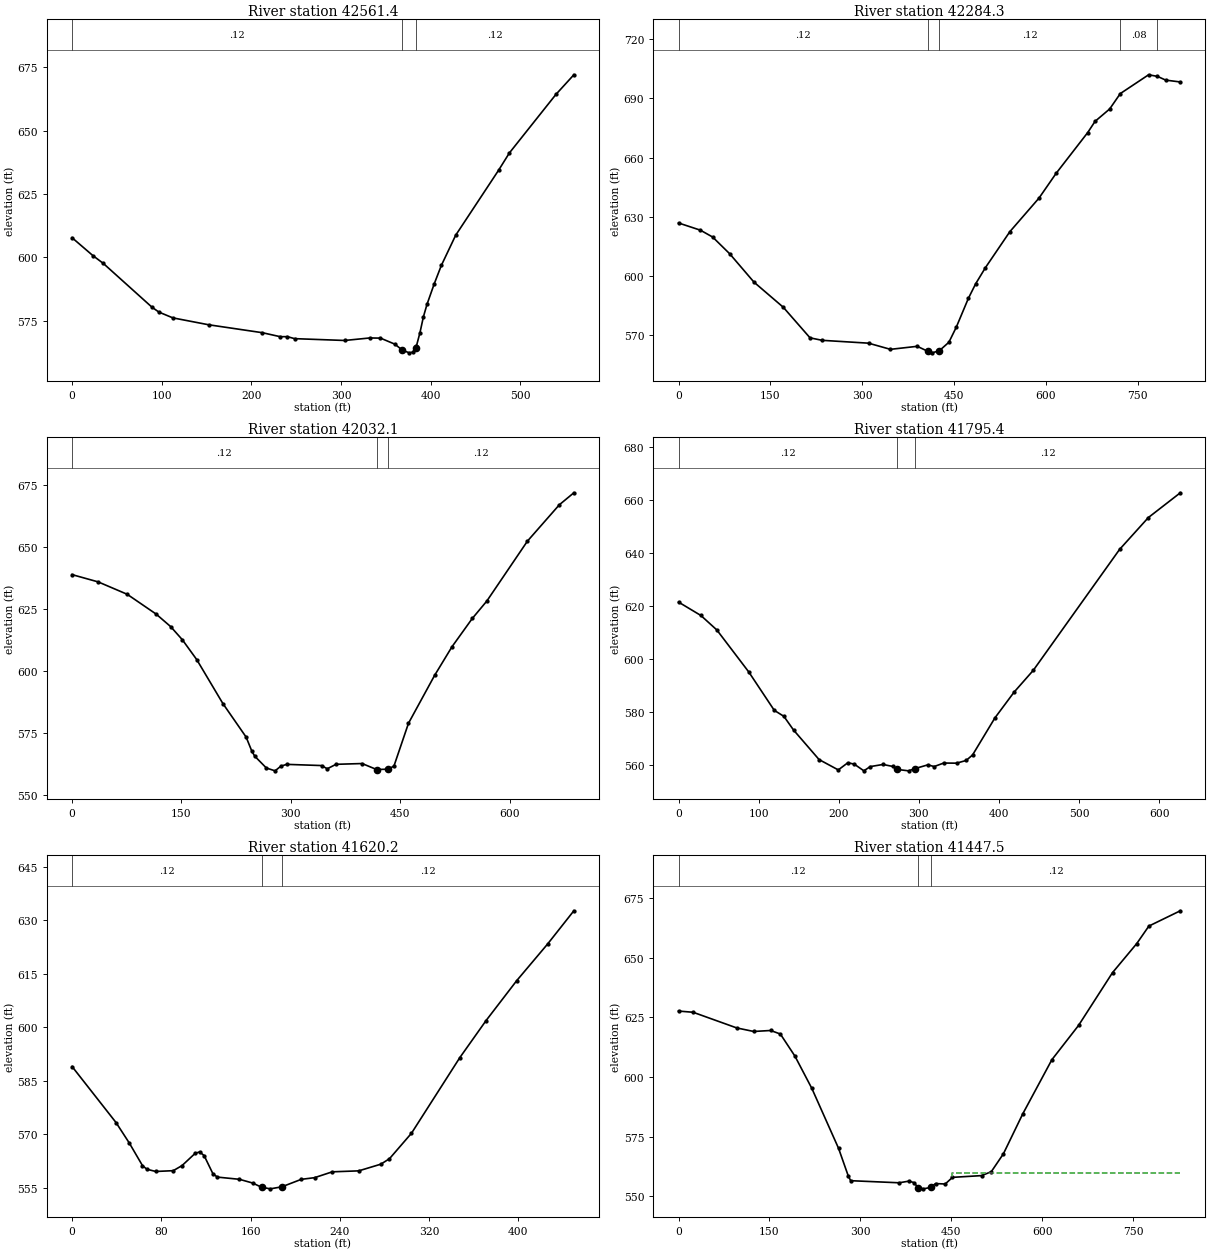
Type RM Length L Ch R = 1 ,42561.4 ,274.3,277.1,280
XS GIS Cut Line= 3
     2367293.325      382059.161     2367404.002      382078.692
     2367795.712      381862.764
#Sta/Elev= 30
       0   607.8    23.2  600.75    34.9  597.64    89.1  580.39    96.9  578.44
   112.4  576.17   152.3  573.45   212.2  570.32   232.2  568.74   240.2  568.76
   248.2  567.97   304.1  567.25     332  568.24     344  568.18     360   565.8
   368.1  563.52     376  562.37     380  562.63   383.1  564.41     384  564.93
     388  570.27   391.9  576.61   395.9  581.51   403.9  589.55   411.9  596.87
   427.9  608.79   475.8  634.46   487.8  641.26   539.7  664.35   559.7   672.1
#Mann= 3 ,-1 , 0
       0     .12       0   368.1    .045       0   383.1     .12       0
Bank Sta=368.1,383.1
XS Rating Curve= 0 ,0
Exp/Cntr=0.3,0.1

Type RM Length L Ch R = 1 ,42284.3 ,251.3,252.2,252.6
XS GIS Cut Line= 3
      2367317.27      382377.662      2367695.87      382220.848
     2368077.903      382072.615
#Sta/Elev= 30
       0  626.88    35.8  623.22    55.7  619.76    83.6  611.28   123.3  596.92
   171.1  584.23   214.8  568.75   234.7   567.5   310.3  566.06   346.1  562.94
   389.9  564.47   406.8     562   413.8  561.17   425.7  562.17   441.6  566.53
   453.6   574.1   473.4  588.73   485.4  596.16   501.3  604.29   541.1  622.45
   588.8  639.48   616.7  651.98   668.4  672.65   680.3  678.28   704.2  684.56
  721.56692.3439   767.8  701.86  782.26 701.047   795.7  699.16   819.6  698.22
#Mann= 5 ,-1 , 0
       0     .12       0   406.8    .045       0   425.7     .12       0
  721.56     .08       0  782.26    .016       0
Bank Sta=406.8,425.7
XS Rating Curve= 0 ,0
Exp/Cntr=0.3,0.1

Type RM Length L Ch R = 1 ,42032.1 ,236.2,236.7,236.8
XS GIS Cut Line= 2
      2367403.76      382592.925     2368049.619      382355.385
#Sta/Elev= 30
       0  638.73    35.8   635.8    75.6  630.81   115.4  622.81   135.2  617.79
   151.2  612.51     171  604.48   206.8   586.8   238.7  573.28   246.6  567.56
   250.6  565.55   266.5  560.81   278.4  559.67   286.4  561.56   294.4  562.28
   342.1   561.8     350   560.5     362   562.3   397.8  562.61   417.7   560.2
   433.8  560.34   441.5  561.63   461.4  578.84   497.2  598.12   521.1  609.69
   548.9  621.07   568.8  628.07   624.5  652.22   668.3  666.88   688.2  671.71
#Mann= 3 ,-1 , 0
       0     .12       0   417.7    .045       0   433.8     .12       0
Bank Sta=417.7,433.8
XS Rating Curve= 0 ,0
Exp/Cntr=0.3,0.1

Type RM Length L Ch R = 1 ,41795.4 ,171,175.2,178.8
XS GIS Cut Line= 3
     2367552.657      382683.076     2367662.249      382730.819
     2368142.935      382570.229
#Sta/Elev= 30
       0  621.36    27.9  616.31    47.8  610.86    87.7  595.01   119.5  580.56
   131.5   578.3   143.5  573.16   175.4  562.01   199.4  558.11   211.3  560.81
   219.3  560.29   231.3  557.77   239.3  559.36   255.2  560.16   267.2  559.43
  272.93  558.29   287.1  557.76   295.1  558.61   311.1  560.01   319.1  559.38
     331   560.7     347  560.65     359  561.67     367  563.75   394.9  577.72
   418.8  587.42   442.8  595.65   550.5  641.22   586.4  653.22   626.3  662.56
#Mann= 3 ,-1 , 0
       0     .12       0  272.93    .045       0   295.1     .12       0
Bank Sta=272.93,295.1
XS Rating Curve= 0 ,0
Exp/Cntr=0.3,0.1

Type RM Length L Ch R = 1 ,41620.2 ,179.3,172.7,165.8
XS GIS Cut Line= 4
     2367703.482      382909.856     2367795.712      382849.092
     2367947.622       382820.88     2368114.723       382741.67
#Sta/Elev= 30
       0  588.95    39.4  573.25    51.3  567.51    63.1  561.19    67.1  560.15
      75  559.53    90.7  559.75    98.6  561.18   110.4  564.62   114.4  565.01
   118.4  563.98   126.3  558.88   130.3  557.95   150.1  557.33     162  556.28
   169.9   555.1   177.8  554.66   188.1  555.23   205.5  557.32   217.4  557.79
   233.3  559.43     257   559.7   276.8  561.57   284.6  563.11   304.3  570.24
   347.6  591.42   371.2  601.84   398.7  613.04   426.3  623.27   449.9  632.61
#Mann= 3 ,-1 , 0
       0     .12       0   169.9    .045       0   188.1     .12       0
Bank Sta=169.9,188.1
XS Rating Curve= 0 ,0
Exp/Cntr=0.3,0.1

Type RM Length L Ch R = 1 ,41447.5 ,363.3,360.3,357.4
XS GIS Cut Line= 2
     2367562.541      383176.421       2368299.9      382799.866
#Sta/Elev= 30
       0  627.63      24  627.13      96  620.56     124  619.07     152  619.48
     168     618     192  608.74     220  595.15     264  570.05     280  558.48
     284  556.46     364  555.58     380  556.27     388  555.69   395.5  553.54
     404  553.04     416  553.63     424  555.25     440  555.07     452  557.86
     500  558.59     516  560.23     536  567.74     568  584.53     616  607.23
     660  621.61     716  643.75     756  655.95     776  663.29   827.9  669.71
#Mann= 3 ,-1 , 0
       0     .12       0   395.5    .045       0     416     .12       0
#XS Ineff= 2 , 0
                          451.86          559.64
Permanent Ineff=
       F       F
Bank Sta=395.5,416
XS Rating Curve= 0 ,0
Exp/Cntr=0.3,0.1

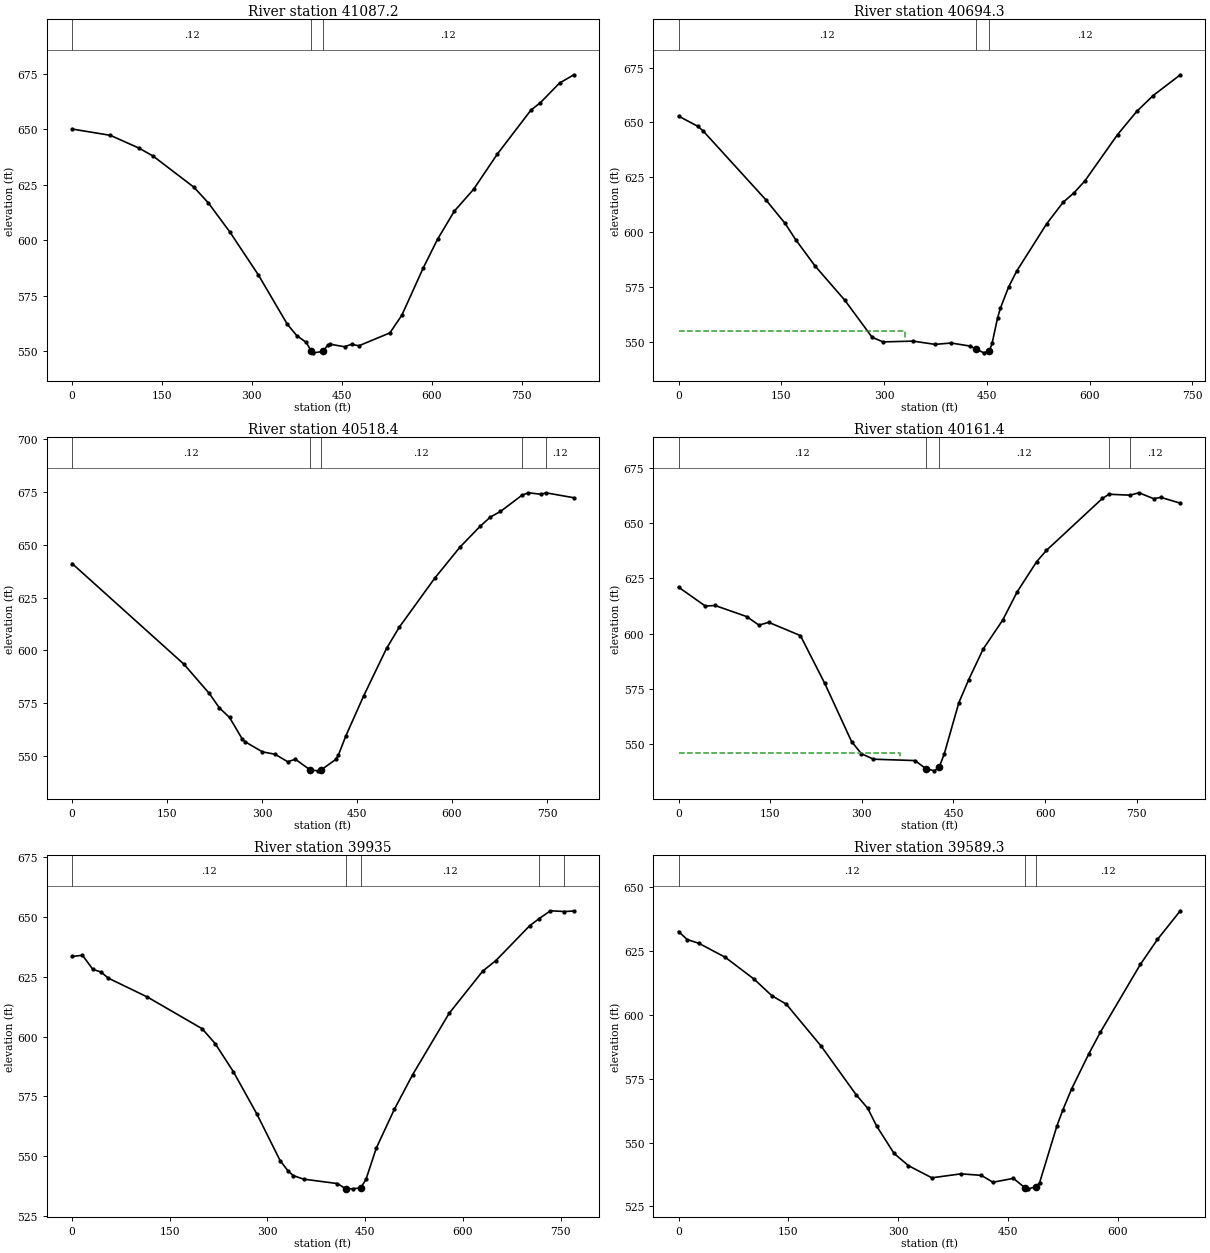
Type RM Length L Ch R = 1 ,41087.2 ,392,392.9,393.9
XS GIS Cut Line= 2
      2367704.23      383514.741     2368413.325      383069.438
#Sta/Elev= 30
       0  650.15    63.8  647.31   111.6  641.55   135.6  637.88   203.4  623.88
   227.3  616.85   263.2  603.73     311  584.27   358.8  562.24   374.8  556.97
   390.8  553.88   398.7  550.12   402.7  549.18   418.4   549.8   426.6  552.66
   430.6  553.06   454.6  551.94   466.5  553.04   478.5  552.36   530.3  558.17
   550.2  566.12   586.1  587.56     610   600.5     638  613.16   669.9  622.92
   709.7  638.89   765.6  658.65   781.5  662.05   813.4  670.88   837.3  674.62
#Mann= 3 ,-1 , 0
       0     .12       0   398.7    .045       0   418.4     .12       0
Bank Sta=398.7,418.4
XS Rating Curve= 0 ,0
Exp/Cntr=0.3,0.1

Type RM Length L Ch R = 1 ,40694.3 ,175,176,175.8
XS GIS Cut Line= 2
     2367905.749      383777.437     2368548.751      383426.349
#Sta/Elev= 30
       0   652.9    27.9   648.3    35.8  646.18   127.4  614.74   155.3  604.06
   171.2  596.46   199.1  584.62   242.9  568.84   282.7  551.97   298.6  549.89
   342.4  550.25   374.3  548.77   398.2  549.37     426  547.97     434  546.59
   445.9   544.9   453.9  545.75   457.9  549.37   465.8  560.87   469.8  565.18
   481.8  574.87   493.7   582.2   537.5  603.79   561.4  613.56   577.3  617.87
   593.2  623.32     641  644.49   668.9  655.02   692.8  662.25   732.6  671.76
#Mann= 3 ,-1 , 0
       0     .12       0     434    .045       0   453.9     .12       0
#XS Ineff= 2 , 0
          330.68  554.64
Permanent Ineff=
       F       F
Bank Sta=434,453.9
XS Rating Curve= 0 ,0
Exp/Cntr=0.3,0.1

Type RM Length L Ch R = 1 ,40518.4 ,356.5,357,357.6
XS GIS Cut Line= 3
      2367983.43      383838.675     2368167.615      383824.959
     2368700.575      383532.692
#Sta/Elev= 30
       0  641.08   176.8  593.45   216.7  579.65   232.7  572.82   248.7   568.3
   268.7  558.15   272.7  556.91   300.7  552.04   320.7   550.9   340.6  547.36
   352.6  548.55   376.1  543.49   388.6  543.07   392.6  543.36   416.6  548.48
   420.6   550.5   432.6  559.74   460.6  578.54   496.6  600.91   516.6   610.9
   572.6  634.08   612.6  648.82   644.6  658.72   660.6  663.04   676.6  665.68
  710.48 673.339   720.6  674.52   740.6  673.83  748.77674.4833   792.5  672.17
#Mann= 5 ,-1 , 0
       0     .12       0   376.1    .045       0   392.6     .12       0
  710.48    .016       0  748.77     .12       0
Bank Sta=376.1,392.6
XS Rating Curve= 0 ,0
Exp/Cntr=0.3,0.1

Type RM Length L Ch R = 1 ,40161.4 ,227.7,226.3,224.8
XS GIS Cut Line= 3
     2368150.841      384228.059     2368589.983       384000.35
      2368885.59      383861.331
#Sta/Elev= 30
       0  621.03    43.9  612.49    59.8  612.75   111.7  607.73   131.6  603.88
   147.6  605.14   199.5  599.14   239.4  577.51   283.2  551.29   299.2   545.8
   319.1   543.3     387  542.68   404.6  539.06   418.9  538.04   426.8  539.82
   434.8  545.58   458.8  568.84   474.7  579.11   498.6  593.05   530.5  606.13
   554.4  618.97   586.3  632.61   602.2  637.66   693.8  661.14  704.62663.0159
  739.17662.5956   753.6  663.68   777.5  661.03   789.5   661.6   821.3  658.98
#Mann= 5 ,-1 , 0
       0     .12       0   404.6    .045       0   426.8     .12       0
  704.62    .016       0  739.17     .12       0
#XS Ineff= 2 , 0
          363.29  546.12
Permanent Ineff=
       F       F
Bank Sta=404.6,426.8
XS Rating Curve= 0 ,0
Exp/Cntr=0.3,0.1

Type RM Length L Ch R = 1 ,39935   ,327.3,345.7,364.1
XS GIS Cut Line= 3
     2368200.797      384352.318     2368482.561      384320.446
     2368899.228       384068.71
#Sta/Elev= 30
       0  633.54      16     634      32  628.09    43.9  627.08    55.9  624.42
   115.8  616.53   199.7  603.29   219.7  597.09   247.6  585.34   283.6  567.69
   319.5   548.1   331.4   543.9   339.4  541.89   355.4  540.39   407.3  538.54
   419.8  536.44   431.2  536.33   443.2  536.77   451.2  540.24   467.1   553.4
     495  569.69     523  584.14   578.8  609.69   630.7  627.45   650.7   631.8
   702.5  646.34  716.56649.2402   734.5  652.62  755.51652.3145   770.4  652.51
#Mann= 5 ,-1 , 0
       0     .12       0   419.8    .045       0   443.2     .12       0
  716.56    .016       0  755.51     .12       0
Bank Sta=419.8,443.2
XS Rating Curve= 0 ,0
Exp/Cntr=0.3,0.1

Type RM Length L Ch R = 1 ,39589.3 ,214.4,221.1,227.6
XS GIS Cut Line= 3
     2368201.335      384431.571     2368737.553      384581.948
     2368859.081      384624.265
#Sta/Elev= 30
       0  632.65    11.9  629.51    27.8  628.04    63.6  622.61   103.4  613.98
   127.3  607.57   147.2  604.22   194.9  587.77   242.6  568.77   258.6   563.4
   270.5  556.57   294.4   545.8   314.2  540.96   346.1  536.22   385.9  537.77
   413.7  537.18   429.6  534.48   457.5     536   472.9  532.42   477.4   531.9
   487.9  532.63   493.3  534.28   517.1  556.64   525.1   562.8     537  570.98
   560.8  584.89   576.4  593.26     631  619.79   654.4  629.58   685.6  640.78
#Mann= 3 ,-1 , 0
       0     .12       0   472.9    .045       0   487.9     .12       0
Bank Sta=472.9,487.9
XS Rating Curve= 0 ,0
Exp/Cntr=0.3,0.1

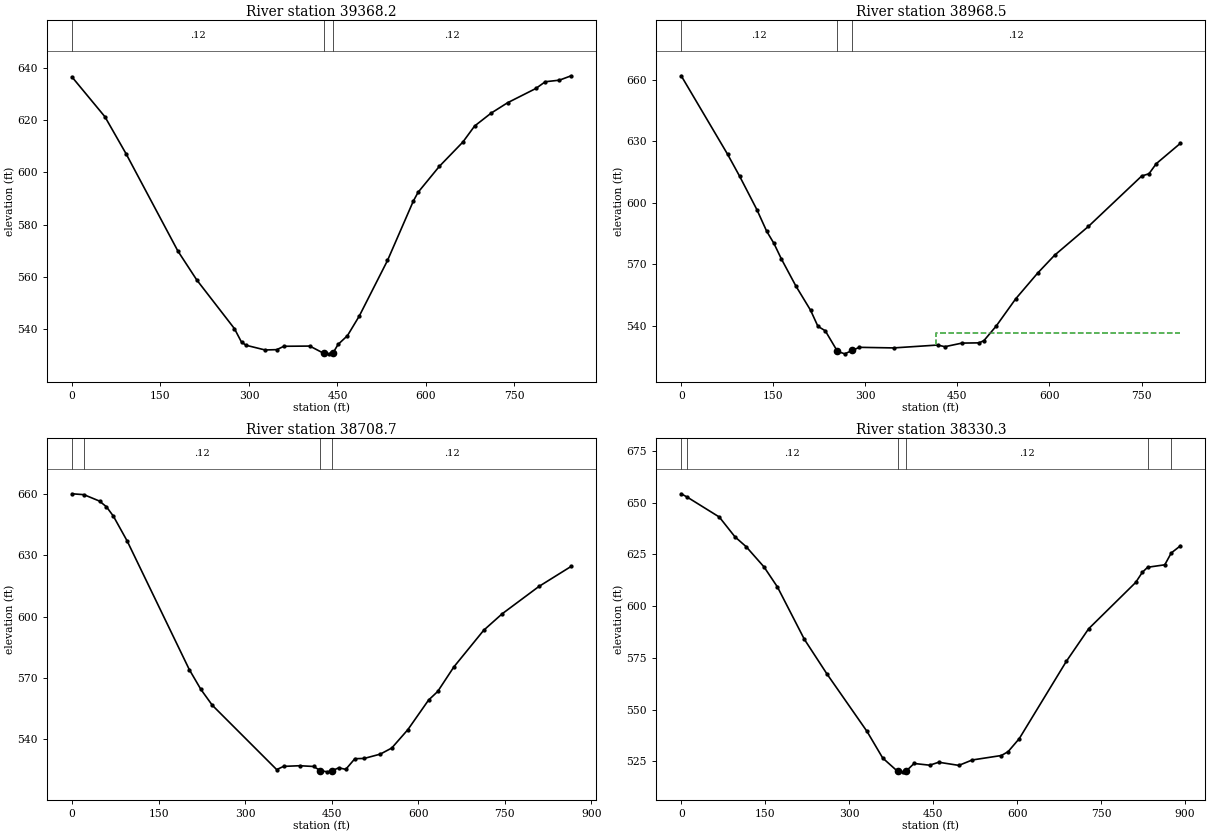
Type RM Length L Ch R = 1 ,39368.2 ,412.8,399.7,386.5
XS GIS Cut Line= 2
     2368156.365      384503.982     2368874.828      384950.817
#Sta/Elev= 30
       0  636.53    55.9   621.3    91.8  607.13   179.6  569.95   211.5  558.94
   275.4  540.31   287.4  535.14   295.3  533.95   327.3  532.16   347.2  532.28
   359.2  533.57   403.1  533.65   427.3  530.81     435  530.68   442.3  530.95
     451  534.27   466.9  537.62   486.9   545.1   534.8  566.36   578.7  589.13
   586.7  592.44   622.6  602.32   662.5  611.62   682.4  617.75   710.4  622.68
   738.3  626.65   786.2   632.1   802.2  634.68   826.1  635.28   846.1  636.96
#Mann= 3 ,-1 , 0
       0     .12       0   427.3    .045       0   442.3     .12       0
Bank Sta=427.3,442.3
XS Rating Curve= 0 ,0
Exp/Cntr=0.3,0.1

Type RM Length L Ch R = 1 ,38968.5 ,267.9,259.8,251.6
XS GIS Cut Line= 3
     2368030.087      385040.932     2368598.642      385025.983
     2368834.124      384959.552
#Sta/Elev= 30
       0  662.04    75.6  623.71    95.4  612.89   123.3   596.7   139.2  586.21
   151.1  580.21   163.1  572.72   186.9   559.4   210.8   547.6   222.7  539.79
   234.7   537.6   254.6  527.55   266.5  526.35   278.4  527.99   290.3  529.53
     346  529.24   417.6  530.64   429.6  529.84   457.4  531.59   485.2  531.71
   493.2   532.8   513.1  539.87   544.9  553.17   580.6  565.71   608.2  574.43
   663.5  588.54   750.3  613.14   762.1  614.22     774  619.15   813.4  629.11
#Mann= 3 ,-1 , 0
       0     .12       0   254.6    .045       0   278.4     .12       0
#XS Ineff= 2 , 0
                          414.63          536.33
Permanent Ineff=
       F       F
Bank Sta=254.6,278.4
XS Rating Curve= 0 ,0
Exp/Cntr=0.3,0.1

Type RM Length L Ch R = 1 ,38708.7 ,390.7,378.4,363
XS GIS Cut Line= 2
     2368044.672      385398.228     2368844.975      385070.229
#Sta/Elev= 30
       0   660.1   20.74659.6675    47.8  656.52    59.8  653.72    71.7   649.2
    95.7  636.98   203.3   574.1   223.2  564.47   243.1  556.66   354.7  525.16
   366.7  526.73   394.6  527.05   418.5  526.69   430.5  524.65   442.4  524.06
   451.4  524.71   462.4  526.04   474.3  525.26   490.2   530.5   506.2  530.61
   534.1  532.72     554   535.7   581.9  544.68   617.8  559.16   633.7  563.39
   661.6  575.37   713.4  593.34   745.3  601.37   809.1  614.77   864.9  624.58
#Mann= 4 ,-1 , 0
       0    .016       0   20.74     .12       0   430.5    .045       0
   451.4     .12       0
Bank Sta=430.5,451.4
XS Rating Curve= 0 ,0
Exp/Cntr=0.3,0.1

Type RM Length L Ch R = 1 ,38330.3 ,298,289.3,280.5
XS GIS Cut Line= 2
     2368298.486      385802.629     2368902.648      385146.517
#Sta/Elev= 30
       0  654.32   10.81652.6953      68  643.09      96  633.52     116  628.76
     148  618.94     172  609.23     220  583.98     260  567.38     332  539.43
     360  526.59   386.4   520.2     396  519.92   401.4  520.17     416  523.96
     444  523.13     460  524.56     496  523.04   519.9  525.65   571.9  527.81
   583.9  529.65   603.9  535.96   687.9  573.28   727.9  589.08   811.9  611.46
   823.9   616.4  833.29618.7997   863.9  619.99  875.43625.6985   891.9  629.19
#Mann= 6 ,-1 , 0
       0     .06       0   10.81     .12       0   386.4    .045       0
   401.4     .12       0  833.29    .016       0  875.43     .12       0
Bank Sta=386.4,401.4
XS Rating Curve= 0 ,0
Exp/Cntr=0.3,0.1