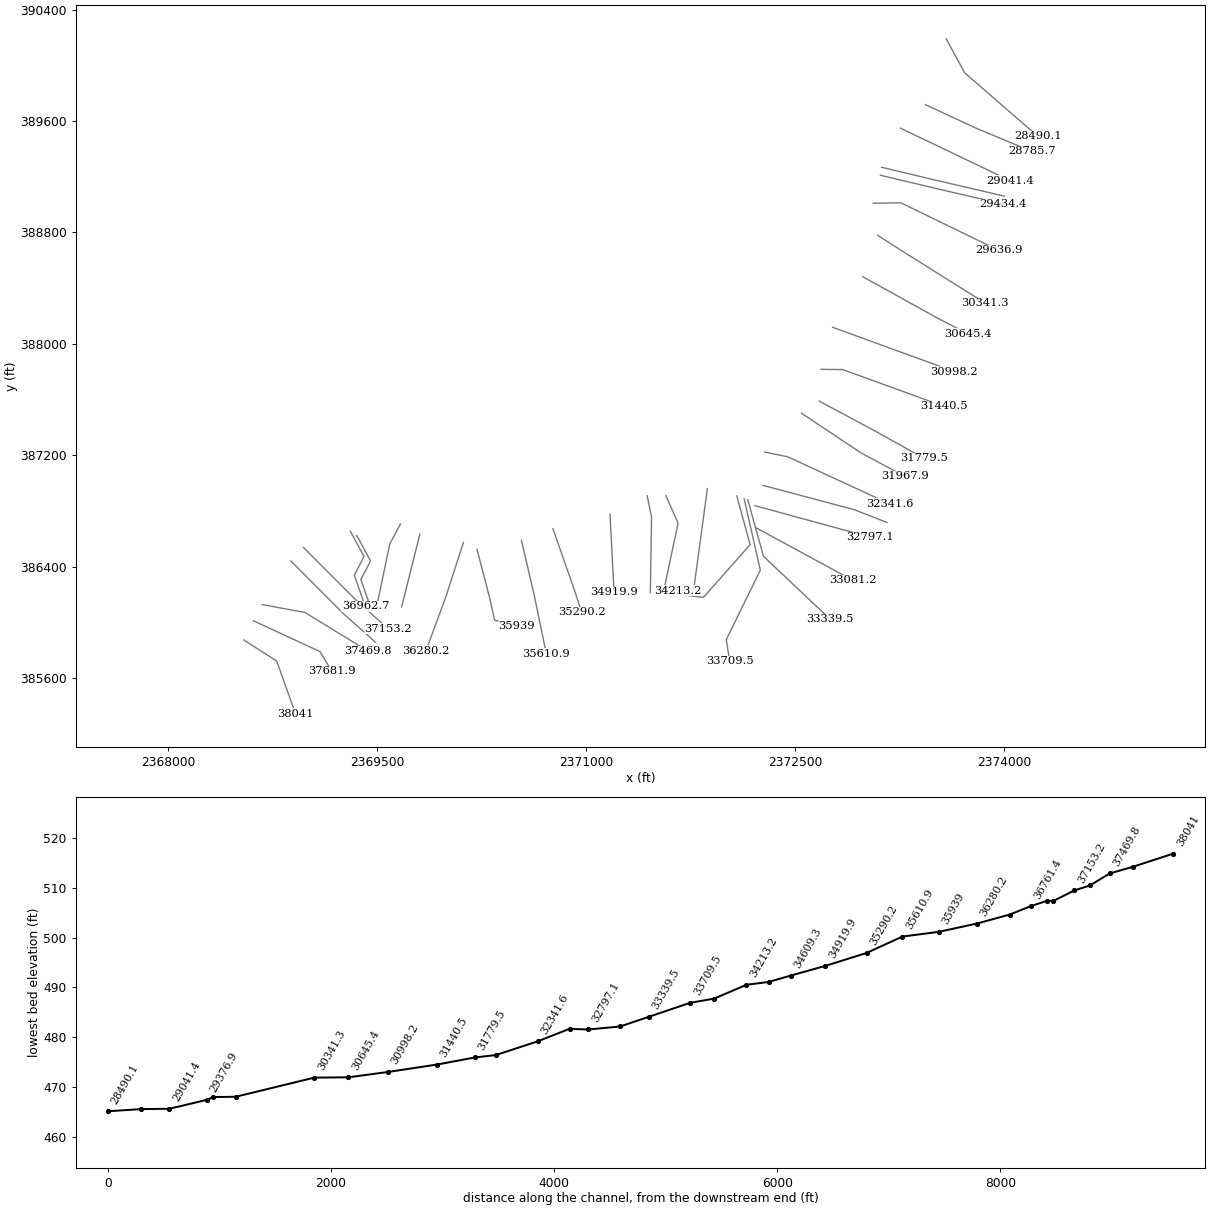
HEC-RAS study TILHANCECK.prj: TILHANCECK

--- TILHANCECK.g01 (geometry) --- (continued)

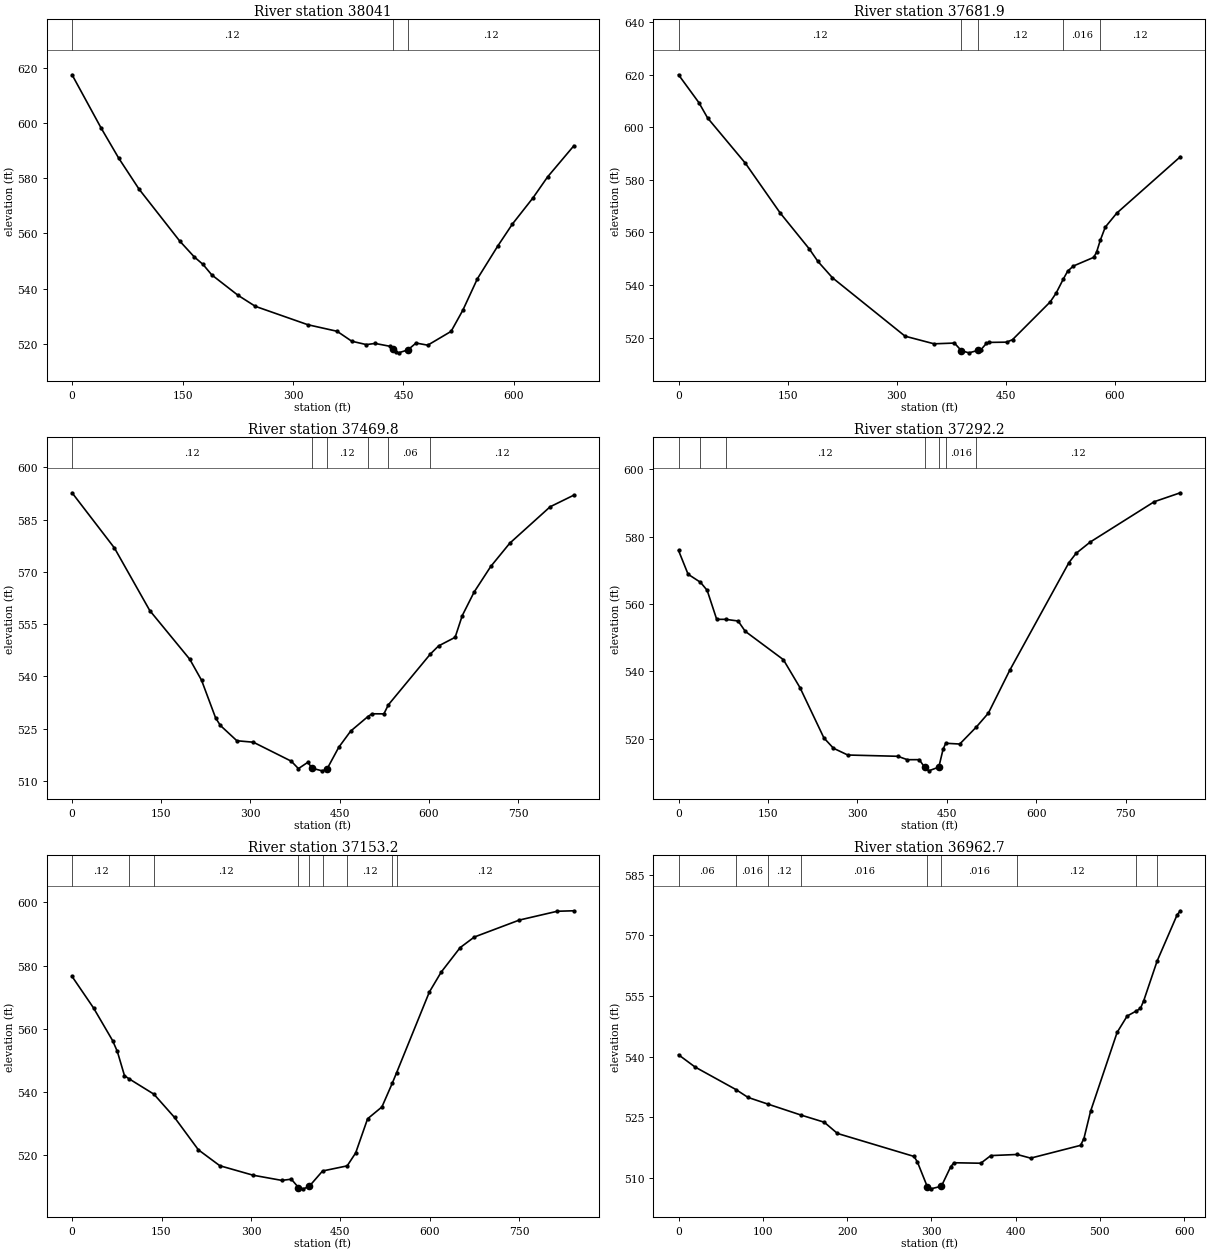
Type RM Length L Ch R = 1 ,38041   ,339.7,359.2,378.3
XS GIS Cut Line= 3
     2368541.155       385873.18       2368777.7      385722.356
     2368912.249      385344.752
#Sta/Elev= 30
       0  617.37    39.5  598.09    63.2  587.29    90.9  576.05   146.2  557.26
     166  551.51   177.8  548.82   189.7  545.03   225.2  537.68   248.9  533.66
   320.2  527.01   359.9  524.64   379.8  521.05   399.6  519.83   411.5  520.25
   431.4  519.23   435.3  518.27   439.3  517.03   443.3  516.85   455.9   517.9
   467.1  520.39     483  519.62   514.7  524.61   530.6  532.24   550.4  543.63
   578.2  555.52     598  563.43   625.8  572.84   645.7  580.44   681.4  591.71
#Mann= 3 ,-1 , 0
       0     .12       0   435.3    .045       0   455.9     .12       0
Bank Sta=435.3,455.9
XS Rating Curve= 0 ,0
Exp/Cntr=0.3,0.1

Type RM Length L Ch R = 1 ,37681.9 ,213.3,212.1,210.3
XS GIS Cut Line= 3
     2368610.444      386011.107     2369089.115       385789.63
     2369172.666      385649.656
#Sta/Elev= 30
       0  619.94      28  609.35      40  603.52    91.9  586.34   139.8  567.42
   179.8  553.77   191.8  548.97   211.8  542.76   311.7  520.56   351.6  517.66
   379.6  517.95  389.27  515.01   399.6  514.23   411.4  515.12   415.6  515.29
   423.5  517.79   427.5   518.2   451.5  518.29   459.5  519.24   511.4   533.6
   519.4  536.88  529.35542.2502   535.4  545.29   543.3  547.24   571.2  550.53
   575.1  552.45  580.18556.9434   587.1  562.01     603  567.36   690.4  588.78
#Mann= 5 ,-1 , 0
       0     .12       0  389.27    .045       0   411.4     .12       0
  529.35    .016       0  580.18     .12       0
Bank Sta=389.27,411.4
XS Rating Curve= 0 ,0
Exp/Cntr=0.3,0.1

Type RM Length L Ch R = 1 ,37469.8 ,182.1,177.6,173.1
XS GIS Cut Line= 3
     2368673.069      386127.877     2368980.608      386070.663
     2369433.636      385793.317
#Sta/Elev= 30
       0   592.7    71.3  576.84   130.7  558.88     198  544.89   217.8  538.87
   241.5  528.03   249.5  525.88   277.2   521.5   304.9  521.08   368.7  515.63
   380.7   513.5   396.7  515.33   403.4  513.62   420.6  512.86   428.6  513.32
   448.6  519.63   468.6  524.27  497.17528.3823   504.5  529.24   524.5  529.22
  531.97531.8086  602.73546.4142   616.4  548.72   644.3   551.2   656.3  557.44
   676.3  564.21   704.2  571.54   736.2  578.22   804.1  588.68     844  592.02
#Mann= 6 ,-1 , 0
       0     .12       0   403.4    .045       0   428.6     .12       0
  497.17    .016       0  531.97     .06       0  602.73     .12       0
Bank Sta=403.4,428.6
XS Rating Curve= 0 ,0
Exp/Cntr=0.3,0.1

Type RM Length L Ch R = 1 ,37292.2 ,140.1,139.1,138.1
XS GIS Cut Line= 3
     2368879.638      386440.387     2369255.131      386064.153
      2369486.43      385857.876
#Sta/Elev= 30
       0   575.9      16  568.84   36.76566.4487      48  564.06      64  555.44
   78.76555.4471    99.9  554.95   111.9  551.88   175.8  543.47   203.8  535.12
   243.8  520.22   259.8  517.16   283.8  515.15   367.7  514.77   383.7  513.76
   403.7  513.77   412.5  511.57   419.6  510.45   436.5  511.56   443.6  516.83
  448.08518.6392   471.6  518.41  499.34 523.451   519.6  527.59   555.4   540.3
   654.7  572.29   666.6  575.03   690.5  578.41   797.8  590.38   841.5  593.03
#Mann= 7 ,-1 , 0
       0     .12       0   36.76    .016       0   78.76     .12       0
   412.5    .045       0   436.5     .12       0  448.08    .016       0
  499.34     .12       0
Bank Sta=412.5,436.5
XS Rating Curve= 0 ,0
Exp/Cntr=0.3,0.1

Type RM Length L Ch R = 1 ,37153.2 ,218.8,190.4,161.8
XS GIS Cut Line= 3
     2368969.916       386537.61     2369345.409      386161.375
     2369576.708      385955.098
#Sta/Elev= 30
       0  576.56      36  566.61    67.9  556.32    75.9  552.87    87.9  545.22
   95.25544.2657  137.25539.3661   171.9     532   211.8  521.79   247.8  516.76
   303.7  513.76   351.7  512.13   367.7  512.51   379.7  509.88   387.7  509.46
   397.5   510.2   420.1515.0975  461.36 516.718   475.6  520.81   495.6   531.6
   519.6  535.33  536.83542.7585  544.08546.0779   599.1  571.62     619  577.93
   650.8  585.67   674.6  589.02   750.1  594.38   813.7  597.16   841.5  597.31
#Mann= 9 ,-1 , 0
       0     .12       0   95.25    .016       0  137.25     .12       0
   379.7    .045       0   397.5     .12       0   420.1    .016       0
  461.36     .12       0  536.83     .06       0  544.08     .12       0
Bank Sta=379.7,397.5
XS Rating Curve= 0 ,0
Exp/Cntr=0.3,0.1

Type RM Length L Ch R = 1 ,36962.7 ,56.2,56.1,56.4
XS GIS Cut Line= 5
     2369306.129      386655.515      2369404.87      386472.139
     2369335.426      386338.675     2369413.551      386115.151
     2369414.636      386115.151
#Sta/Elev= 30
       0  540.47    19.6  537.45   67.99531.8879    82.5  529.93  105.76528.2997
  145.13525.5825   172.9   523.8   188.6  521.02   279.5  515.34   283.5  513.96
   295.4  507.77   299.3  507.33   311.9  507.96   323.1  512.84     327  513.78
   358.7  513.66   370.6  515.55  401.84 515.824   417.9  514.92   477.1  518.08
   481.1  519.77     489  526.51   520.5  546.01   532.4  550.05   543.4 551.314
   548.2  551.94   552.1  553.86  567.98563.6508   591.6  575.02   595.5  576.07
#Mann= 9 ,-1 , 0
       0     .06       0   67.99    .016       0  105.76     .12       0
  145.13    .016       0   295.4    .045       0   311.9    .016       0
  401.84     .12       0   543.4     .06       0  567.98     .12       0
Bank Sta=295.4,311.9
XS Rating Curve= 0 ,0
Exp/Cntr=0.3,0.1

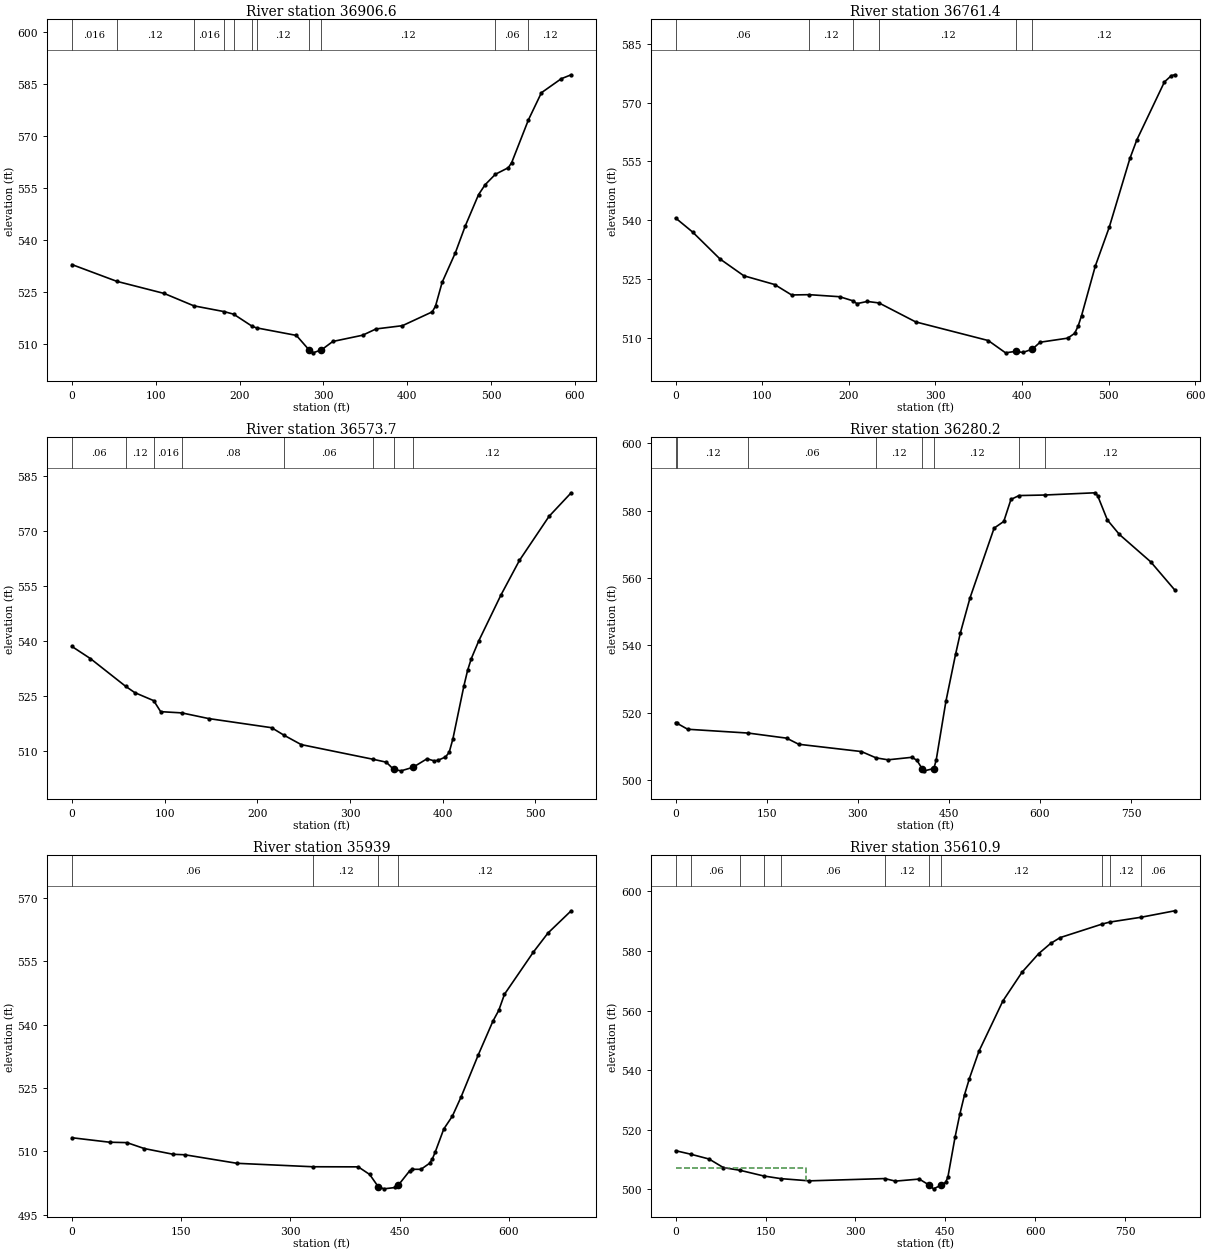
Type RM Length L Ch R = 1 ,36906.6 ,139.2,145.2,149.9
XS GIS Cut Line= 5
     2369352.787      386624.048     2369451.528      386440.672
     2369382.084      386307.208     2369460.209      386083.684
     2369461.294      386083.684
#Sta/Elev= 30
       0  532.89   53.48528.0458     110  524.54   145.4  520.96  181.61 519.286
   192.9518.5438  215.26515.0016  220.15514.5941   267.7  512.41  282.43  508.33
   287.5  507.37  297.65  508.23   311.2  510.66   346.8  512.47   362.7  514.28
   394.2  515.22   429.8  519.22   433.7   520.9   441.6  527.77   457.4  536.33
   469.2  544.07     485  553.11   492.9  555.98  505.09558.9973   520.5  560.89
   524.5  562.35  544.52 574.738     560  582.57   583.7  586.62   595.5  587.76
#Mann= 11 ,-1 , 0
       0    .016       0   53.48     .12       0   145.4    .016       0
  181.61     .08       0   192.9     .12       0  215.26     .06       0
  220.15     .12       0  282.43    .045       0  297.65     .12       0
  505.09     .06       0  544.52     .12       0
Bank Sta=282.43,297.65
XS Rating Curve= 0 ,0
Exp/Cntr=0.3,0.1

Type RM Length L Ch R = 1 ,36761.4 ,188,187.7,188
XS GIS Cut Line= 3
     2369666.372      386705.575     2369589.983      386563.214
     2369504.914      386156.964
#Sta/Elev= 30
       0  540.61    19.7  537.03    51.2   530.2    78.8  525.91   114.3  523.69
     134  521.03  154.35521.1016   189.5  520.58  204.88519.5335   209.4  518.82
   221.4  519.38  234.93518.9952   277.3  514.17   361.1  509.43   381.1   506.3
     393  506.69     401  506.39     412  507.24     421     509   452.9  510.04
   460.9  511.26   464.9   513.1   468.9  515.79   484.8  528.42   500.8  538.23
   524.7  555.76   532.7  560.49   564.6  575.25   572.6  576.84   576.6  577.06
#Mann= 6 ,-1 , 0
       0     .06       0  154.35     .12       0  204.88    .016       0
  234.93     .12       0     393    .045       0     412     .12       0
Bank Sta=393,412
XS Rating Curve= 0 ,0
Exp/Cntr=0.3,0.1

Type RM Length L Ch R = 1 ,36573.7 ,294.7,293.6,290.7
XS GIS Cut Line= 2
     2369805.754      386632.507     2369675.053      386110.089
#Sta/Elev= 30
       0  538.56      20  535.24   57.89527.6915    67.8  525.96    88.2 523.774
    95.7  520.77   118.5 520.433   147.6  518.88   215.4  516.39   228.7514.3455
   247.3  511.78  324.92507.7699   339.1  506.98     347     505     355  504.62
   367.9  505.59     383  507.91   390.9  507.33   394.9   507.5   402.9   508.4
   406.9  509.66   410.9  513.32   422.8   527.8   426.8  532.06   430.8  535.27
   438.8  540.08   462.7  552.58   482.7  562.05   514.6  574.06   538.5   580.5
#Mann= 8 ,-1 , 0
       0     .06       0   57.89     .12       0    88.2    .016       0
   118.5     .08       0   228.7     .06       0  324.92     .12       0
     347    .045       0   367.9     .12       0
Bank Sta=347,367.9
XS Rating Curve= 0 ,0
Exp/Cntr=0.3,0.1

Type RM Length L Ch R = 1 ,36280.2 ,329.2,341.2,354.1
XS GIS Cut Line= 3
     2370118.775      386573.111     2369991.528      386179.815
     2369849.894      385796.429
#Sta/Elev= 30
       0  517.12    2.32516.9228    19.9  515.15  119.79514.0153   182.8  512.51
   202.7   510.7     306  508.54  330.16506.6631   349.8  506.09   389.5  506.84
   397.5  505.91   405.9  503.47   409.4  502.82   425.3   503.5   429.2  506.09
   445.1   523.4     461  537.35   468.9   543.7   484.8  554.09   524.5  574.78
   540.4  576.76   552.2  583.28   565.5584.4366  607.62 584.595   691.1  585.26
   695.1  584.35     711   577.2   730.8   572.9   782.4  564.78   822.1  556.41
#Mann= 8 ,-1 , 0
       0    .016       0    2.32     .12       0  119.79     .06       0
  330.16     .12       0   405.9    .045       0   425.3     .12       0
   565.5     .08       0  607.62     .12       0
Bank Sta=405.9,425.3
XS Rating Curve= 0 ,0
Exp/Cntr=0.3,0.1

Type RM Length L Ch R = 1 ,35939   ,328.4,328.1,327.6
XS GIS Cut Line= 4
     2370216.719      386523.283     2370308.733      386169.117
     2370342.364      386016.099     2370499.706      385972.936
#Sta/Elev= 30
       0  513.25    51.7  512.19    75.6  512.09    99.4  510.69   139.2  509.33
   155.1  509.22   226.7   507.2  330.93506.3838   393.3  506.36     409  504.56
   420.7  501.68   428.6  501.16   444.3  501.48   448.2     502   463.8  505.39
   467.8  505.78   479.5  505.78   491.3  507.21   495.2  508.28   499.1  509.89
   510.8  515.32   522.6  518.36   534.5  522.87   558.4  532.94   578.3  540.83
   586.3  543.37   594.2   547.2     634   557.2   653.9  561.67   685.8  566.94
#Mann= 4 ,-1 , 0
       0     .06       0  330.93     .12       0   420.7    .045       0
   448.2     .12       0
Bank Sta=420.7,448.2
XS Rating Curve= 0 ,0
Exp/Cntr=0.3,0.1

Type RM Length L Ch R = 1 ,35610.9 ,318.5,320.8,322.9
XS GIS Cut Line= 3
      2370535.48      386588.576     2370627.769      386192.771
     2370714.173      385775.231
#Sta/Elev= 30
       0     513   25.03511.8337    55.8  510.21    79.7  507.33  107.86506.4031
   147.1504.5097  175.64503.6264   223.1  502.88  348.72 503.647   366.6  502.79
   406.4  503.48   421.9   501.6   430.3   500.2   442.3  501.37   450.3  502.37
   454.2  504.11   466.2  517.57   474.2   525.3   482.1  531.85   490.1  537.22
     506  546.36   545.9  563.22   577.8  572.86   605.7  579.13   625.6  582.54
   641.5   584.5  711.43589.0372  724.24589.7064  777.18591.3522   832.8   593.5
#Mann= 11 ,-1 , 0
       0     .08       0   25.03     .06       0  107.86     .08       0
   147.1     .12       0  175.64     .06       0  348.72     .12       0
   421.9    .045       0   442.3     .12       0  711.43     .06       0
  724.24     .12       0  777.18     .06       0
#XS Ineff= 2 , 0
          218.23  507.27
Permanent Ineff=
       F       F
Bank Sta=421.9,442.3
XS Rating Curve= 0 ,0
Exp/Cntr=0.3,0.1

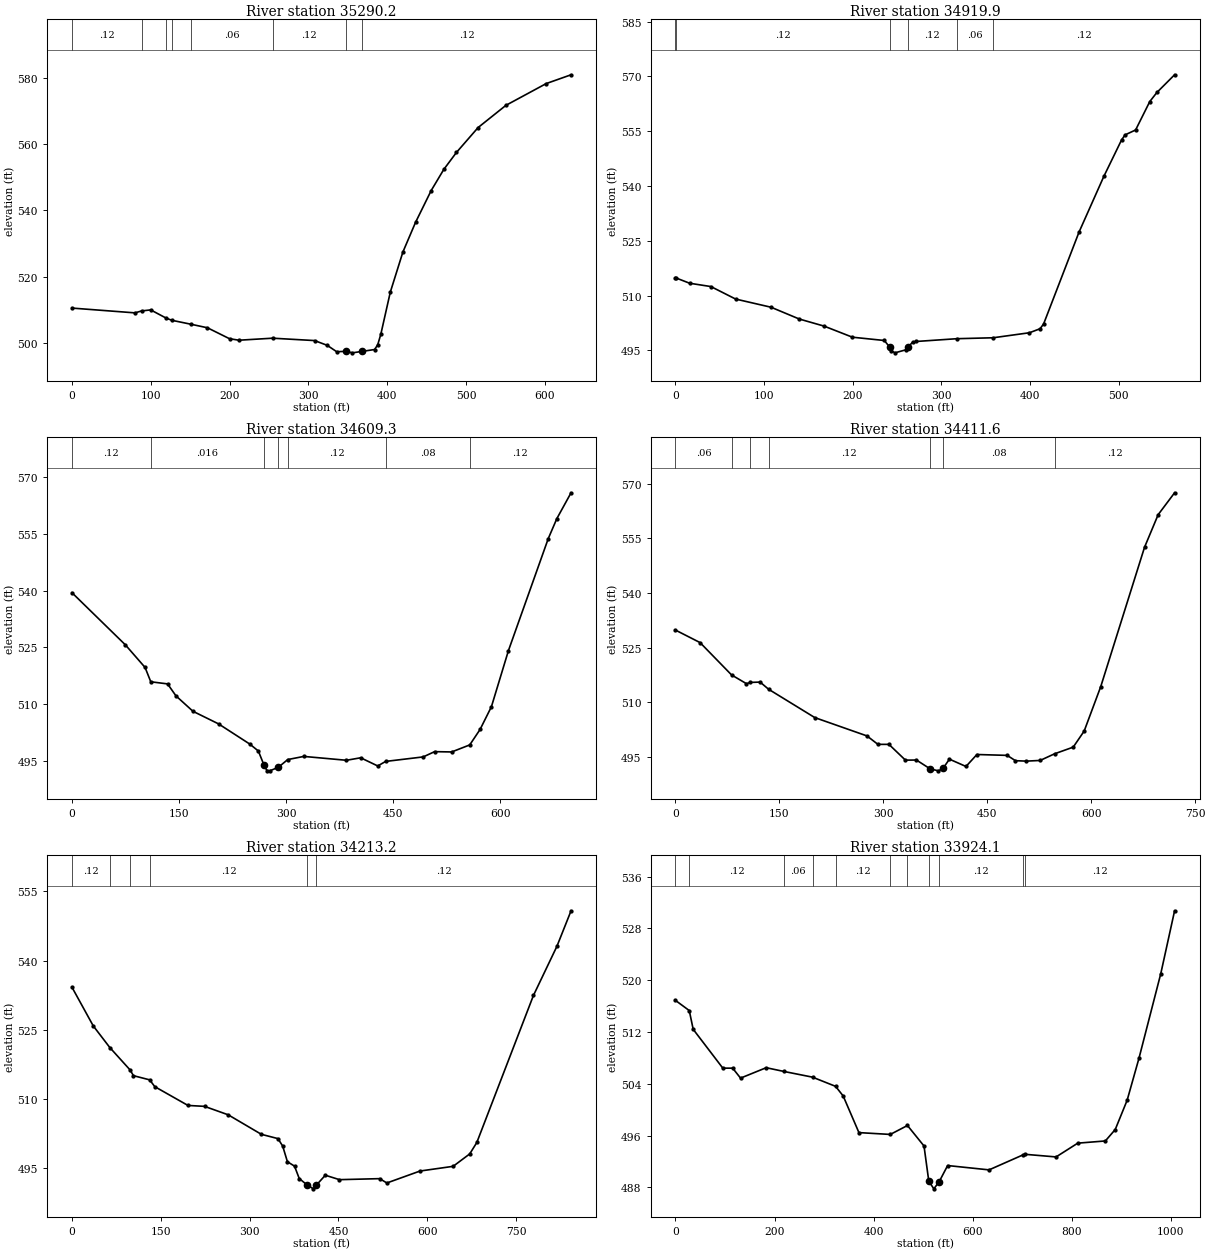
Type RM Length L Ch R = 1 ,35290.2 ,376.6,370.2,363.8
XS GIS Cut Line= 3
     2370761.858      386672.589     2370921.581      386215.992
     2370966.719      386073.631
#Sta/Elev= 30
       0  510.45      80     509   88.34509.5859    99.9   509.9  119.79507.3793
  126.86506.7484  151.25505.5476   171.9  504.49   199.9  501.18   211.9  500.73
  254.49  501.34   307.8  500.62   323.8  499.18   335.8  497.25   347.8  497.36
   355.8  496.91   367.8  497.34   383.8  497.91   387.8   499.3   391.8  502.53
   403.8  515.25   419.8  527.41   435.8  536.36   455.7  546.01   471.7   552.4
   487.7  557.52   515.2  565.06   550.5  571.78   601.6  578.36   633.1  581.02
#Mann= 8 ,-1 , 0
       0     .12       0   88.34     .08       0  119.79     .06       0
  126.86     .12       0  151.25     .06       0  254.49     .12       0
   347.8    .045       0   367.8     .12       0
Bank Sta=347.8,367.8
XS Rating Curve= 0 ,0
Exp/Cntr=0.3,0.1

Type RM Length L Ch R = 1 ,34919.9 ,311.6,310.7,308.5
XS GIS Cut Line= 2
     2371171.581      386776.756     2371201.094      386214.256
#Sta/Elev= 30
       0  514.88     .32514.8448      16  513.37      40  512.46    67.9  509.04
   107.9   506.8   139.8  503.57   167.8  501.63   199.7   498.6   235.7   497.7
  241.89  495.86   243.7   494.9   247.7  494.32   259.7  495.13   262.3  495.89
   267.6  497.21   271.6  497.43  317.62498.1902  358.48498.4445   399.5  499.82
   411.5  500.92   415.5  502.24   455.4  527.34   483.4  542.59   503.4  552.57
   507.4  553.98   519.3  555.32   535.3   563.1   543.3  565.58   563.3  570.43
#Mann= 6 ,-1 , 0
       0    .016       0     .32     .12       0  241.89    .045       0
   262.3     .12       0  317.62     .06       0  358.48     .12       0
Bank Sta=241.89,262.3
XS Rating Curve= 0 ,0
Exp/Cntr=0.3,0.1

Type RM Length L Ch R = 1 ,34609.3 ,202.9,197.6,191.8
XS GIS Cut Line= 3
     2371438.942        386908.7     2371470.192      386754.186
     2371461.511       386212.52
#Sta/Elev= 30
       0  539.44    74.9  525.65   102.5  519.68  110.48515.8959     134  515.34
   145.8  512.17   169.6   508.1   205.4  504.78   249.3  499.43   261.2  497.61
   269.2  493.86   273.2  492.45   277.1  492.37   289.1  493.29  302.39495.3499
   324.9  496.18   384.7  495.16   404.6  495.82   428.5  493.66  439.59494.8585
   492.2  496.05   508.2  497.44   532.1  497.36  557.42499.2169   571.9   503.3
   587.8  509.31   611.7  524.16   667.5  553.75   679.5  559.01   699.4  565.83
#Mann= 7 ,-1 , 0
       0     .12       0  110.48    .016       0   269.2    .045       0
   289.1    .016       0  302.39     .12       0  439.59     .08       0
  557.42     .12       0
Bank Sta=269.2,289.1
XS Rating Curve= 0 ,0
Exp/Cntr=0.3,0.1

Type RM Length L Ch R = 1 ,34411.6 ,195.6,198.5,201
XS GIS Cut Line= 4
     2371572.622      386910.436     2371660.641      386712.269
     2371574.358      386304.533     2371556.997      386219.464
#Sta/Elev= 30
       0   529.8    35.5  526.36   80.94517.4744   102.5  515.06  108.15515.4125
   122.2   515.5  134.42513.5323   201.1  505.74   276.4   500.7   292.2  498.38
   308.1  498.38   331.9  494.04   347.8  494.07   367.7  491.63   379.6   491.1
  386.09 491.751   395.4  494.31   419.3   492.3   435.1  495.59   478.8  495.35
   490.7  493.89   506.6  493.77   526.4  493.96  547.22 495.788   574.1  497.62
   589.9  502.04   613.8  514.25     677  552.56   696.7  561.54   720.4  567.55
#Mann= 7 ,-1 , 0
       0     .06       0   80.94     .08       0  108.15    .016       0
  134.42     .12       0   367.7    .045       0  386.09     .08       0
  547.22     .12       0
Bank Sta=367.7,386.09
XS Rating Curve= 0 ,0
Exp/Cntr=0.3,0.1

Type RM Length L Ch R = 1 ,34213.2 ,302.3,289,275.7
XS GIS Cut Line= 3
     2371871.233      386960.783     2371774.011       386243.77
     2371655.956      386228.145
#Sta/Elev= 30
       0  534.25      36  525.85   63.92521.1684   98.09516.3165   103.9  515.06
  131.21 514.159   139.9  512.68   195.9  508.61   223.9  508.41   263.8  506.58
   319.8  502.35   347.8  501.42   355.8  499.81   363.8  496.41   375.8  495.45
   383.8  492.76   397.3  491.35   407.8  490.53   412.3  491.28   427.8  493.48
   451.7  492.52   519.7  492.74   531.7   491.8   587.7  494.39   643.6  495.41
   671.6   498.1   683.6  500.58   779.2  532.46   818.8   543.1   842.7  550.81
#Mann= 6 ,-1 , 0
       0     .12       0   63.92     .06       0   98.09    .016       0
  131.21     .12       0   397.3    .045       0   412.3     .12       0
Bank Sta=397.3,412.3
XS Rating Curve= 0 ,0
Exp/Cntr=0.3,0.1

Type RM Length L Ch R = 1 ,33924.1 ,207.3,214.6,223.7
XS GIS Cut Line= 4
     2372082.221      386907.435     2372178.525      386558.006
     2371843.456      386179.533     2371704.567      386195.158
#Sta/Elev= 30
       0  516.88   27.85515.3107    35.8  512.41    95.6  506.41   115.5  506.41
   131.4  504.87   183.2  506.48  218.86 505.902  276.67505.0192  323.28503.5992
   338.6  502.11   370.4  496.45  433.73496.1676  468.38497.5486   501.8  494.38
  511.45  488.94   521.7  487.76   532.6  488.89   549.5  491.36   633.1  490.69
  701.49493.0024  706.04493.0941   768.4  492.69   812.2  494.82   867.9  495.16
   887.9  496.93   911.9  501.45   935.8  507.94   979.8  521.01  1007.7  530.73
#Mann= 11 ,-1 , 0
       0    .016       0   27.85     .12       0  218.86     .06       0
  276.67     .08       0  323.28     .12       0  433.73     .06       0
  468.38     .12       0  511.45    .045       0   532.6     .12       0
  701.49     .04       0  706.04     .12       0
Bank Sta=511.45,532.6
XS Rating Curve= 0 ,0
Exp/Cntr=0.3,0.1

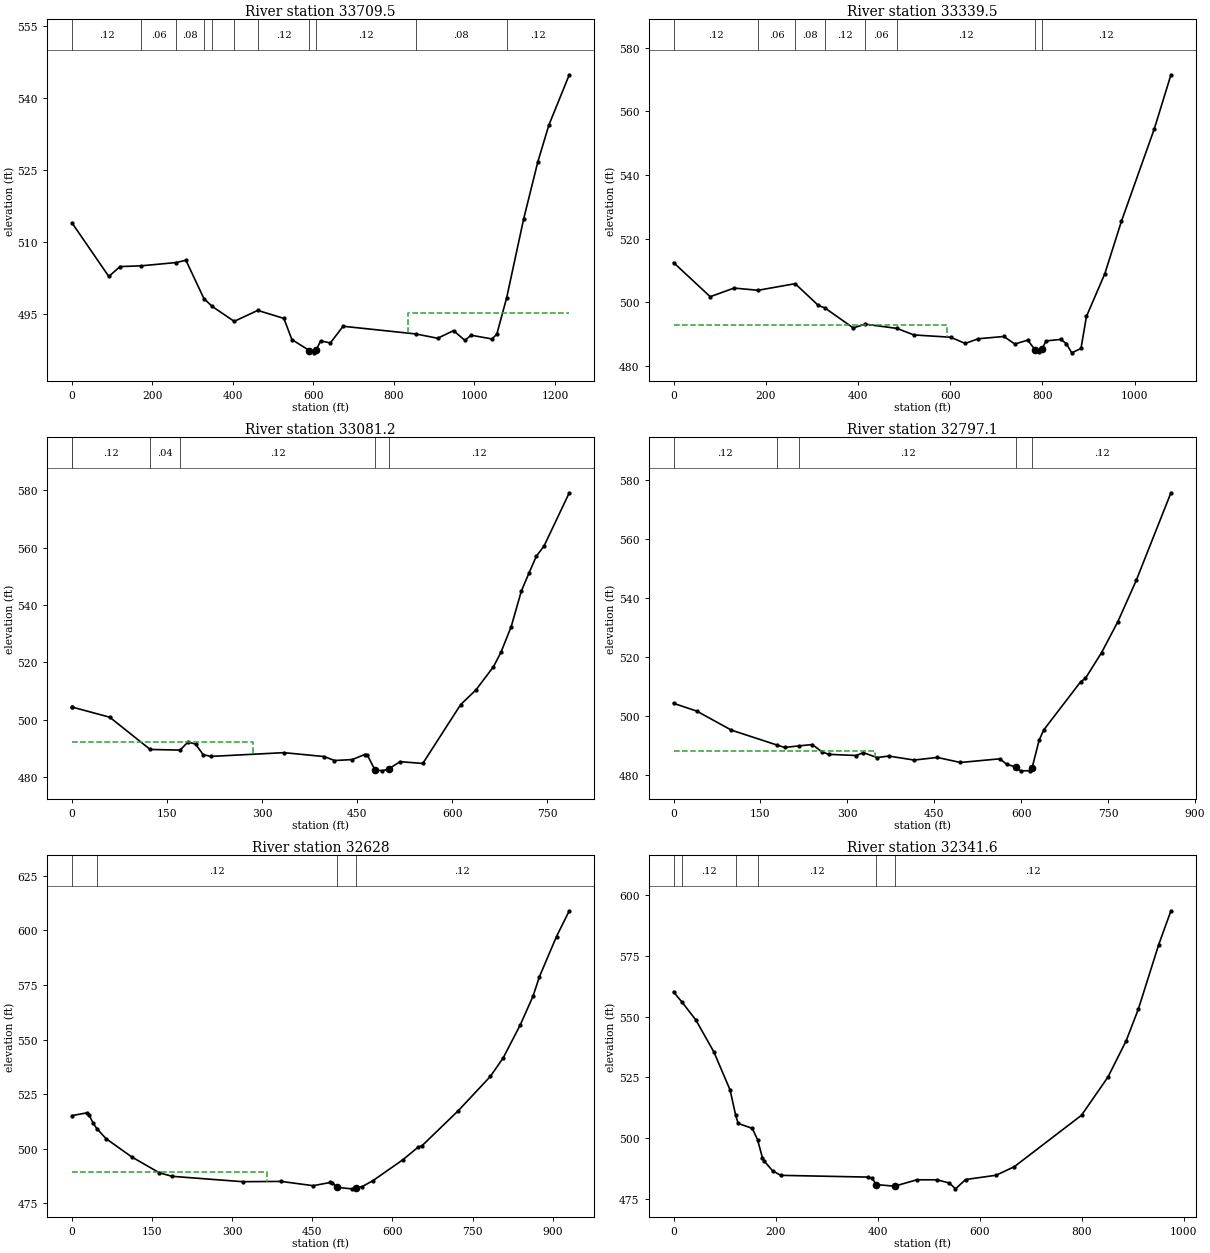
Type RM Length L Ch R = 1 ,33709.5 ,341,370,397.1
XS GIS Cut Line= 4
     2372135.752      386885.409     2372251.442      386375.714
     2372007.077      385875.505     2372030.956        385721.2
#Sta/Elev= 30
       0  514.05    91.8  502.84   119.7   504.9  172.49  505.06  259.63505.7465
   283.3  506.22  327.96498.2358  348.24 496.616  403.23493.4837  461.76495.7644
   526.6   494.1   546.5  489.69   590.2  487.39   602.2  486.92   606.2  487.44
   618.1  489.41     642  488.98   673.8  492.46  854.71490.8552   908.4  489.96
   948.1  491.54     976  489.53   991.9  490.59  1043.6  489.81  1055.5   490.8
 1079.97498.3911  1122.3  514.87  1157.4  526.74  1184.8  534.39  1235.5  544.88
#Mann= 11 ,-1 , 0
       0     .12       0  172.49     .06       0  259.63     .08       0
  327.96     .06       0  348.24     .12       0  403.23     .06       0
  461.76     .12       0   590.2    .045       0   606.2     .12       0
  854.71     .08       0 1079.97     .12       0
#XS Ineff= 2 , 0
                          835.69          495.27
Permanent Ineff=
       F       F
Bank Sta=590.2,606.2
XS Rating Curve= 0 ,0
Exp/Cntr=0.3,0.1

Type RM Length L Ch R = 1 ,33339.5 ,252.2,258.3,264.4
XS GIS Cut Line= 3
     2372161.164      386880.922     2372274.011      386474.672
     2372751.442      386023.283
#Sta/Elev= 30
       0  512.49    79.6  501.76   131.3  504.47  183.36503.7809  263.84505.8461
   314.2     499  327.98498.2566   389.8  491.95  415.42493.1297  484.45491.7992
   521.2  489.74   600.8  489.03   632.7  487.07   660.6  488.54   716.3  489.26
   740.2  486.89   768.1  488.11   783.8  485.13     792  484.24   798.8  485.23
   807.9  487.87   839.7  488.34   851.7  487.03   863.6  484.12   883.6  485.49
   895.5  495.56   935.3  508.97   971.2   525.4  1042.8  554.57  1078.7  571.49
#Mann= 8 ,-1 , 0
       0     .12       0  183.36     .06       0  263.84     .08       0
  327.98     .12       0  415.42     .06       0  484.45     .12       0
   783.8    .045       0   798.8     .12       0
#XS Ineff= 2 , 0
          593.07  492.76
Permanent Ineff=
       F       F
Bank Sta=783.8,798.8
XS Rating Curve= 0 ,0
Exp/Cntr=0.3,0.1

Type RM Length L Ch R = 1 ,33081.2 ,279.1,284.1,289.1
XS GIS Cut Line= 2
     2372225.358      386676.581     2372914.678      386302.278
#Sta/Elev= 30
       0   504.4    1.02504.3745    59.7  500.87  123.55489.6265  170.61489.4005
   183.2  492.23   195.1   491.5     207  487.83     219   487.2   334.5  488.51
   398.2  487.14   414.1  485.77     442  486.09   461.9  487.86   465.8  487.74
   477.8  482.56   489.7  482.17   499.9  482.87   517.6  485.37   553.4  484.74
   613.2  505.29   637.1  510.35   664.9  518.48   676.9  523.63   692.8  532.44
   708.7  544.77   720.7  551.06   732.6  557.06   744.6  560.56   784.4  579.13
#Mann= 6 ,-1 , 0
       0     .06       0    1.02     .12       0  123.55     .04       0
  170.61     .12       0   477.8    .045       0   499.9     .12       0
#XS Ineff= 2 , 0
          285.49  492.24
Permanent Ineff=
       F       F
Bank Sta=477.8,499.9
XS Rating Curve= 0 ,0
Exp/Cntr=0.3,0.1

Type RM Length L Ch R = 1 ,32797.1 ,169,169.1,169.2
XS GIS Cut Line= 2
     2372213.247       386837.52     2373041.372      386611.825
#Sta/Elev= 30
       0  504.43    39.9  501.82    99.8  495.36  177.91 490.349   191.6   489.5
  217.24490.0322   239.5  490.48   255.5  488.08   267.5  487.16   315.4  486.76
   327.4  487.74   351.3  486.06   371.3  486.58   415.2  485.22   455.1  486.11
     495   484.4   562.9  485.64   574.9  483.82   590.8  482.82   598.8  481.57
   614.8  481.61   618.8  482.64   630.8   491.9   638.8  495.42   702.6  511.75
   710.6  512.85   738.6   521.6   766.5     532   798.4  546.04   858.3  575.73
#Mann= 5 ,-1 , 0
       0     .12       0  177.91     .04       0  217.24     .12       0
   590.8    .045       0   618.8     .12       0
#XS Ineff= 2 , 0
          347.88  488.29
Permanent Ineff=
       F       F
Bank Sta=590.8,618.8
XS Rating Curve= 0 ,0
Exp/Cntr=0.3,0.1

Type RM Length L Ch R = 1 ,32628   ,291.5,286.4,281.3
XS GIS Cut Line= 3
     2372270.539      386983.353     2372923.317      386809.742
     2373161.381      386717.062
#Sta/Elev= 30
       0  515.22      28  516.49      32  515.65      40   511.7   46.74509.2834
      64  504.67   111.9  496.34   163.9  489.02   187.8  487.43   319.8  484.97
   391.7   485.1   451.6  483.14   483.6  484.62   487.6  484.52   495.6  482.39
   523.6   481.7   530.9  481.97   543.6  482.76   563.6  485.47   619.5  495.02
   647.5  500.68   655.5  501.48   723.4  517.53   783.2  533.18   807.2  541.64
   839.1  556.73   863.1  569.93     875  578.81     907  597.24   930.9  609.02
#Mann= 4 ,-1 , 0
       0    .016       0   46.74     .12       0   495.6    .045       0
   530.9     .12       0
#XS Ineff= 2 , 0
          365.85  489.46
Permanent Ineff=
       F       F
Bank Sta=495.6,530.9
XS Rating Curve= 0 ,0
Exp/Cntr=0.3,0.1

Type RM Length L Ch R = 1 ,32341.6 ,363,373.7,373.7
XS GIS Cut Line= 3
     2372282.692      387222.936     2372449.358      387188.214
     2373179.849      386850.672
#Sta/Elev= 30
       0  560.16   16.93555.9238    43.6   548.7    79.2  535.45   110.9  519.85
  121.51509.7359   126.7  506.08   154.4  504.07  164.74499.4083   174.2  492.02
   178.2  490.51   194.2  486.61   210.1  484.74   381.4  484.02   389.4  483.58
   397.3  480.94   433.2  480.28     477  482.91   516.8   482.9   540.7  481.57
   552.7  479.19   572.6  483.02   632.4  484.78   668.2  488.33   799.7  509.45
   851.5  525.15   887.3   540.1   911.2  553.15     951  579.61     975  593.55
#Mann= 6 ,-1 , 0
       0     .06       0   16.93     .12       0  121.51    .016       0
  164.74     .12       0   397.3    .045       0   433.2     .12       0
Bank Sta=397.3,433.2
XS Rating Curve= 0 ,0
Exp/Cntr=0.3,0.1

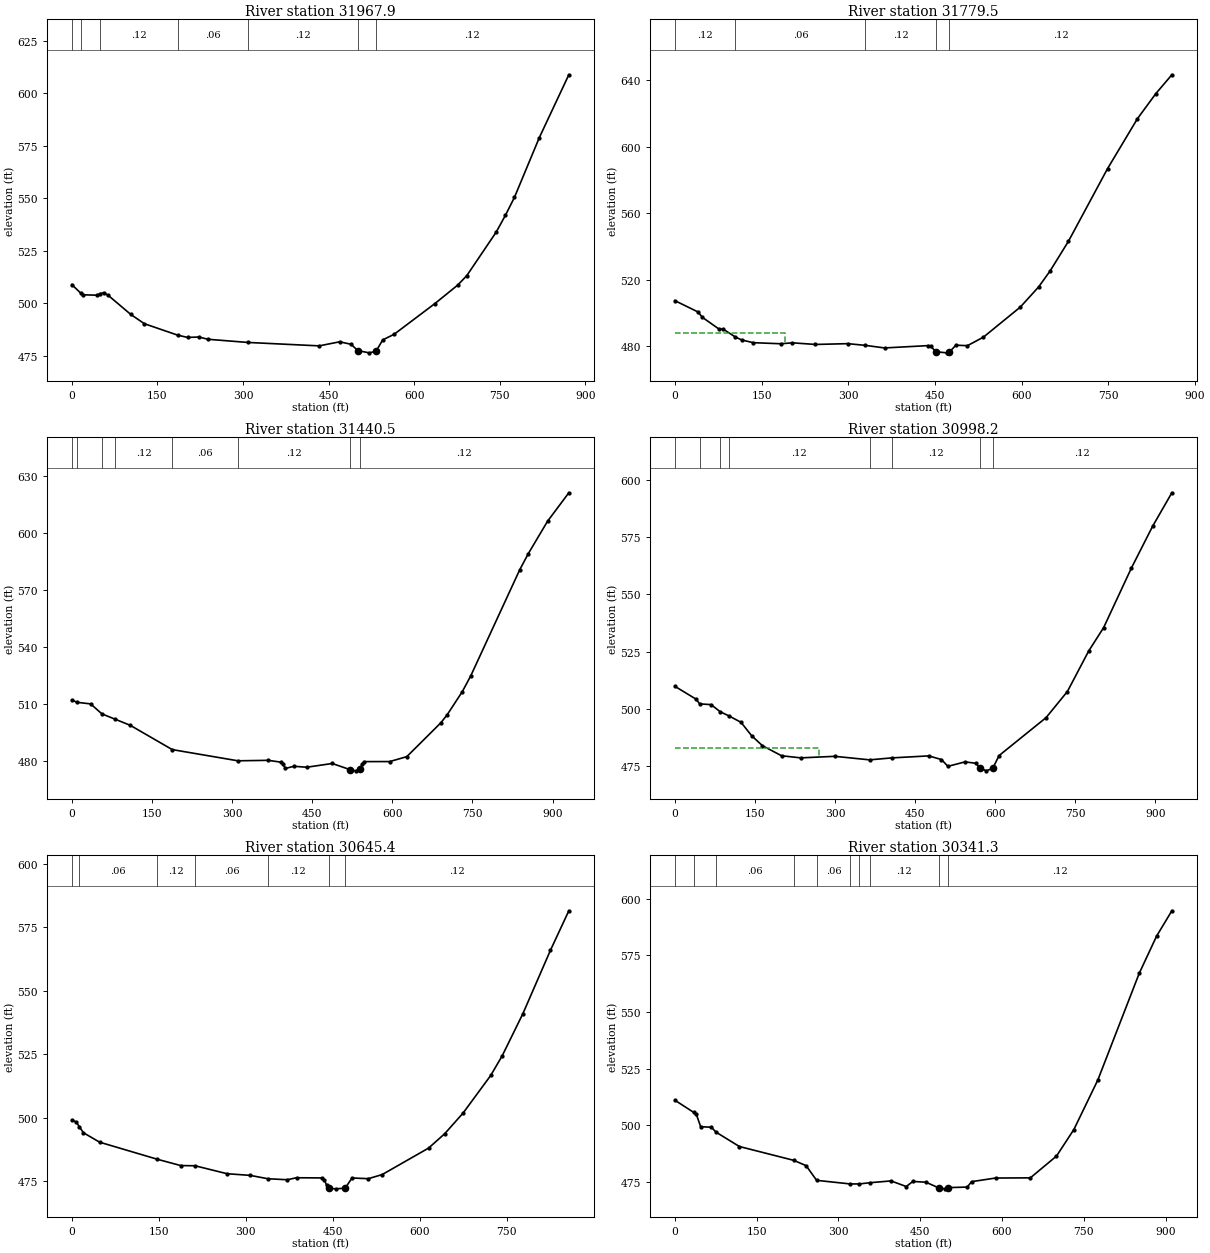
Type RM Length L Ch R = 1 ,31967.9 ,198,188.4,187.8
XS GIS Cut Line= 3
     2372548.317      387500.714       2372975.4      387215.992
     2373291.372      387047.589
#Sta/Elev= 30
       0  508.94   15.24504.9865    19.9  504.09    43.8   503.9   49.87 504.652
    55.7  505.08    63.7  503.84   103.4  494.72   127.3   490.3  185.72484.8544
   202.9  483.78   222.8  483.98   238.7   482.9  308.39481.3952   433.7  479.76
   469.5   481.7   489.4  480.53   501.4  477.52   521.2  476.44   533.2  477.14
   545.1  482.62     565  485.27   636.6  499.93   676.4  508.69   692.3  513.17
     744  533.96     760  541.89   775.9  550.46   819.6  578.99   871.3   608.9
#Mann= 7 ,-1 , 0
       0     .08       0   15.24    .016       0   49.87     .12       0
  185.72     .06       0  308.39     .12       0   501.4    .045       0
   533.2     .12       0
Bank Sta=501.4,533.2
XS Rating Curve= 0 ,0
Exp/Cntr=0.3,0.1

Type RM Length L Ch R = 1 ,31779.5 ,337.2,339,342.3
XS GIS Cut Line= 3
     2372673.742      387589.023     2373077.877      387372.706
     2373428.383      387177.095
#Sta/Elev= 30
       0   507.4    39.9   500.6    47.8  497.29    75.7  490.44    83.7  490.22
  104.72485.4796   115.6  483.72   135.5  482.08   183.4  481.43   203.3  481.99
   243.1  481.01     299  481.49  329.74480.4565   362.7  478.91   438.5  480.32
   442.4  479.96   451.6  476.64   470.3  475.96   474.3   476.2   486.2  480.57
   506.1  480.27   533.9  485.44   597.5  503.48   629.3  515.65   649.2   525.3
   680.9  543.16   748.5  586.88   800.2  616.96     832  632.05   859.8  643.42
#Mann= 5 ,-1 , 0
       0     .12       0  104.72     .06       0  329.74     .12       0
   451.6    .045       0   474.3     .12       0
#XS Ineff= 2 , 0
          191.27  488.06
Permanent Ineff=
       F       F
Bank Sta=451.6,474.3
XS Rating Curve= 0 ,0
Exp/Cntr=0.3,0.1

Type RM Length L Ch R = 1 ,31440.5 ,439,442.4,442
XS GIS Cut Line= 3
     2372687.206      387816.686     2372843.456       387814.95
     2373571.124      387550.777
#Sta/Elev= 30
       0  511.94   10.04510.7196    35.2   509.9   56.31504.6207   81.34501.7751
   109.4  498.58  187.98 485.757   310.9  479.84   367.8  480.09   391.7  479.11
   395.7  478.11   399.7  475.78   415.6  476.95   439.6  476.44   487.5  478.42
     521  475.16   531.4  474.54   539.3  475.25   543.3  478.04   547.3  479.41
   595.2  479.44   627.1  482.04     691  499.96   702.9  504.25   730.9  516.33
   746.8   524.7   838.6   580.8   854.6  589.28   890.5  606.33   930.4   621.4
#Mann= 8 ,-1 , 0
       0     .12       0   10.04    .016       0   56.31     .06       0
   81.34     .12       0  187.98     .06       0   310.9     .12       0
     521    .045       0   539.3     .12       0
Bank Sta=521,539.3
XS Rating Curve= 0 ,0
Exp/Cntr=0.3,0.1

Type RM Length L Ch R = 1 ,30998.2 ,356.2,352.8,348.9
XS GIS Cut Line= 3
     2372770.539       388118.77     2373438.942      387875.714
     2373645.539      387801.061
#Sta/Elev= 30
       0  509.91      40  504.27   46.47502.2455    67.9  501.93   84.59498.8713
  101.63496.9527   123.9  494.21   143.8  488.36   163.8  484.05   199.8  479.62
   235.7   478.7   299.7  479.37  364.86477.8305  406.03478.6839   475.5  479.56
   499.4  477.96   511.4     475   543.4  476.94   563.4  476.36   572.3  474.21
   583.4  473.04   595.4  474.13   607.3  479.71   695.2  496.23   735.2  507.64
   775.1  525.31   803.1  535.52     855  561.46     895   579.8   930.9  594.34
#Mann= 8 ,-1 , 0
       0     .12       0   46.47    .016       0   84.59     .06       0
  101.63     .12       0  364.86     .06       0  406.03     .12       0
   572.3    .045       0   595.4     .12       0
#XS Ineff= 2 , 0
          270.86  483.21
Permanent Ineff=
       F       F
Bank Sta=572.3,595.4
XS Rating Curve= 0 ,0
Exp/Cntr=0.3,0.1

Type RM Length L Ch R = 1 ,30645.4 ,304.5,304.1,302.6
XS GIS Cut Line= 3
     2372987.553      388481.617     2373539.636      388176.061
     2373741.025      388073.631
#Sta/Elev= 30
       0  499.11       8  498.26   12.72496.5184      20  494.08    47.9  490.36
  147.33 483.637   187.7  481.15  212.51481.0676   267.6  477.94   307.5  477.28
  337.92475.9651   371.4  475.56   387.4  476.35   431.3  476.28   435.3  475.55
   439.3  473.38   443.3  472.19   455.3  471.98   471.2  472.25   483.2  476.26
   511.2  475.98   535.2  477.61     615  488.02   642.9  493.69   674.6  501.84
   722.2  516.64     742  524.38   777.7  540.99   825.2  565.96   856.9  581.53
#Mann= 7 ,-1 , 0
       0    .016       0   12.72     .06       0  147.33     .12       0
  212.51     .06       0  337.92     .12       0   443.3    .045       0
   471.2     .12       0
Bank Sta=443.3,471.2
XS Rating Curve= 0 ,0
Exp/Cntr=0.3,0.1

Type RM Length L Ch R = 1 ,30341.3 ,702.6,704.4,693.1
XS GIS Cut Line= 3
     2373095.192      388778.492       2373287.9      388655.228
     2373866.257      388292.444
#Sta/Elev= 30
       0  511.06   34.45505.6831    39.4  504.81    47.3  499.36      67  499.12
   75.41 496.961   118.3  490.61  217.87484.5145   240.7  482.16     260475.6687
  321.82474.0783  338.36474.0876   357.6474.6193   396.4  475.42   424.4  472.94
   436.4  475.18   460.3  474.86   484.3   472.3   496.3  471.92   500.2  472.46
   536.2   472.7   544.2  475.09   588.1  476.69     652  476.77   699.9  486.39
   731.8  498.12   775.7  519.96   851.6  567.06   883.5  583.51   911.5   594.7
#Mann= 10 ,-1 , 0
       0     .12       0   34.45    .016       0   75.41     .06       0
  217.87     .12       0     260     .06       0  321.82     .12       0
  338.36     .06       0   357.6     .12       0   484.3    .045       0
   500.2     .12       0
Bank Sta=484.3,500.2
XS Rating Curve= 0 ,0
Exp/Cntr=0.3,0.1

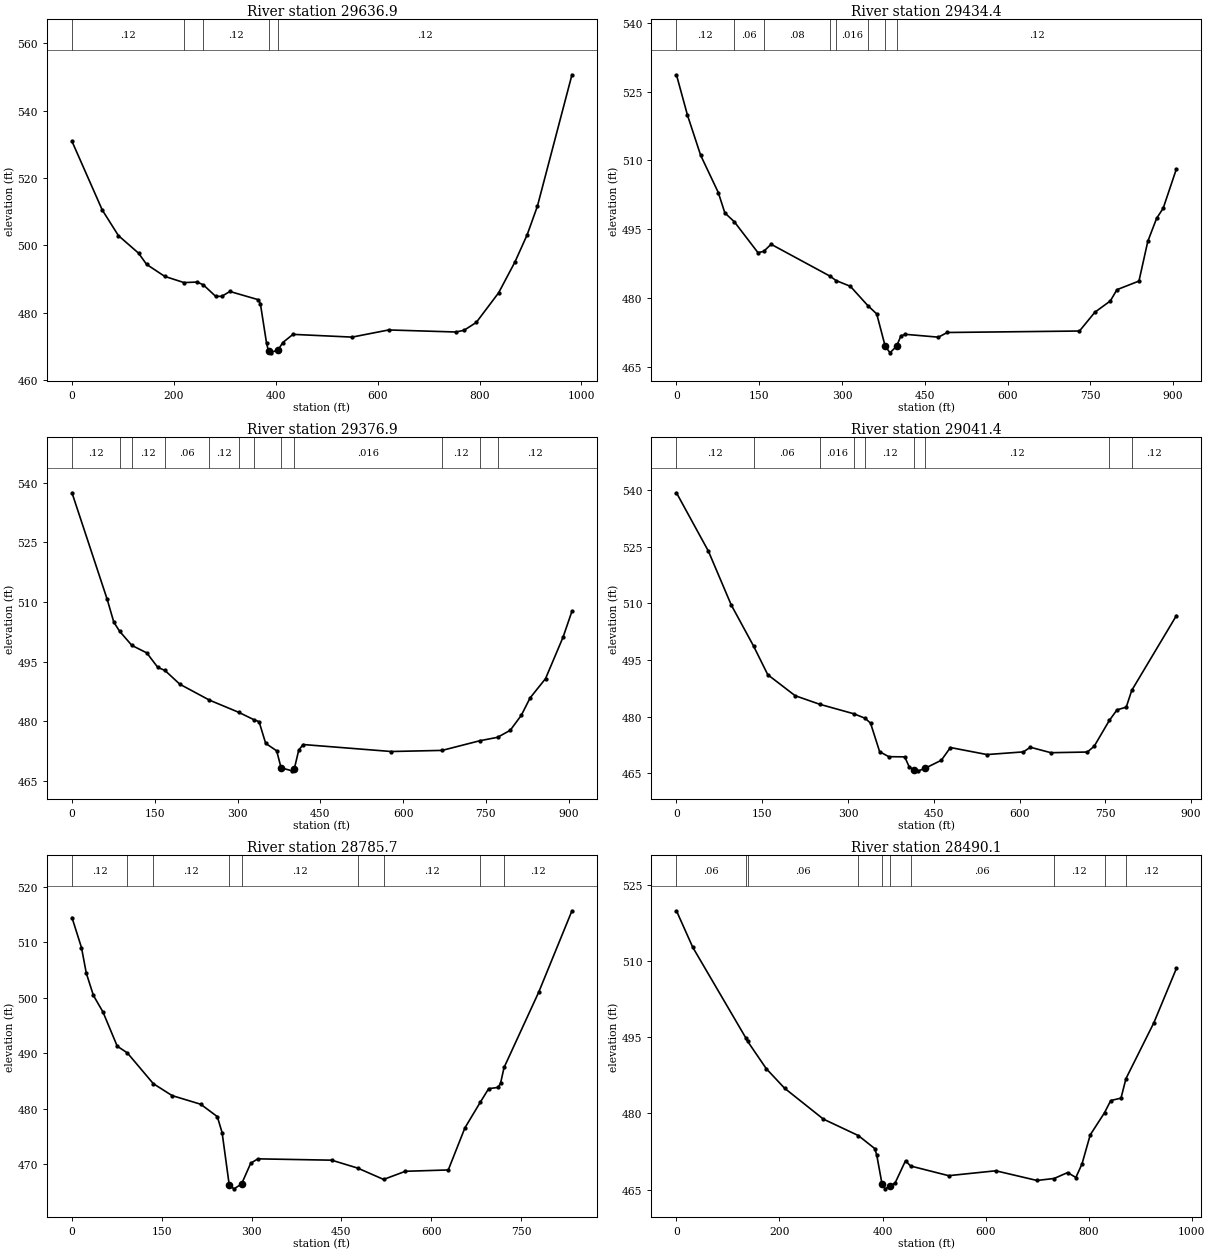
Type RM Length L Ch R = 1 ,29636.9 ,197.2,202.5,218.7
XS GIS Cut Line= 3
     2373062.206      389009.395     2373260.122      389012.867
     2373964.745      388670.554
#Sta/Elev= 30
       0  530.91    59.4  510.52    91.1  502.91   130.6   497.7   146.5  494.35
   182.1  490.79  219.87 488.951   245.9  489.11  257.98488.2564   281.9  484.88
   293.9  484.86   309.9  486.31   365.8  483.86   369.8  482.66   381.8  471.02
   385.8  468.51   389.8  468.08   404.9  469.04   413.8  471.15   433.8  473.57
   549.7  472.75   621.6  474.88   753.5  474.27   769.5  474.78   793.5  477.11
   837.4  485.92   869.4  495.07   893.4  503.16   913.4   511.6   981.3  550.68
#Mann= 5 ,-1 , 0
       0     .12       0  219.87    .016       0  257.98     .12       0
   385.8    .045       0   404.9     .12       0
Bank Sta=385.8,404.9
XS Rating Curve= 0 ,0
Exp/Cntr=0.3,0.1

Type RM Length L Ch R = 1 ,29434.4 ,57.5,57.5,57.6
XS GIS Cut Line= 3
     2373114.333      389210.399     2373494.559       389119.87
     2373996.331      389003.199
#Sta/Elev= 30
       0  528.69    19.9   519.9    43.9  511.11    75.8     503    87.7  498.55
  104.92496.6109   147.6   489.9  157.92490.1336   171.5  491.71  278.81484.7161
  289.11483.7959   315.1  482.54  346.64478.3451   362.9  476.51     378  469.57
   386.9  468.02   398.8  469.47   406.8  471.72   414.8  472.06   474.7  471.44
   490.7  472.46   730.3  472.78   758.2  476.88   786.2  479.34   798.2   481.8
   838.1  483.68   854.1  492.34   870.1  497.37     882  499.57     906  508.17
#Mann= 8 ,-1 , 0
       0     .12       0  104.92     .06       0  157.92     .08       0
  278.81     .06       0  289.11    .016       0  346.64     .12       0
     378    .045       0   398.8     .12       0
Bank Sta=378,398.8
XS Rating Curve= 0 ,0
Exp/Cntr=0.3,0.1

Type RM Length L Ch R = 1 ,29376.9 ,338.1,335.5,331
XS GIS Cut Line= 3
     2373122.145      389267.691     2373502.371      389177.162
     2374004.144      389060.491
#Sta/Elev= 30
       0  537.52    63.8  510.67    75.8  504.92    86.3502.6318  108.46499.0726
   135.6  497.17   155.5  493.53   168.5492.7525   195.4  489.29  249.09485.2768
  302.02482.2132  329.58480.3532     339  479.85     351  474.38   370.9  472.51
   378.9  468.23   398.6  467.46   402.8  467.91   410.8  472.64   418.8  474.09
   578.6  472.33   670.8 472.612  739.02475.0434   771.2475.9075   794.2  477.68
   814.2  481.45   830.1  485.83   858.1  490.69     890  501.18     906  507.69
#Mann= 12 ,-1 , 0
       0     .12       0    86.3     .08       0  108.46     .12       0
   168.5     .06       0  249.09     .12       0  302.02    .016       0
  329.58     .12       0   378.9    .045       0   402.8    .016       0
   670.8     .12       0  739.02    .016       0   771.2     .12       0
Bank Sta=378.9,402.8
XS Rating Curve= 0 ,0
Exp/Cntr=0.3,0.1

Type RM Length L Ch R = 1 ,29041.4 ,255.3,255.7,256
XS GIS Cut Line= 2
      2373257.58      389548.903      2374046.19       389171.33
#Sta/Elev= 30
       0  539.29    55.9  523.82    95.8  509.59  134.76498.7337   159.7  491.12
   207.6  485.56  250.59 483.291  310.51480.7612  329.89479.5891   339.4   478.3
   355.3  470.74   371.3  469.42   399.2  469.37   407.2  466.65   415.2  465.98
   423.2  465.67   434.8  466.35   463.1  468.46   479.1  471.84     543  469.98
   606.8  470.69   618.8  471.92   654.8  470.47   718.6  470.65   730.6  472.21
  756.89479.0025   770.5  481.83   786.5  482.52  796.12486.9608   874.3  506.78
#Mann= 9 ,-1 , 0
       0     .12       0  134.76     .06       0  250.59    .016       0
  310.51     .06       0  329.89     .12       0   415.2    .045       0
   434.8     .12       0  756.89    .016       0  796.12     .12       0
Bank Sta=415.2,434.8
XS Rating Curve= 0 ,0
Exp/Cntr=0.3,0.1

Type RM Length L Ch R = 1 ,28785.7 ,301.6,295.6,288.9
XS GIS Cut Line= 3
     2373437.035      389717.544     2373805.346      389546.658
     2374201.353      389381.156
#Sta/Elev= 30
       0  514.44    15.9  509.02    23.9  504.44    35.8  500.42    51.8  497.43
    75.6  491.28   92.45490.0792  135.84484.5368   167.2  482.39     215  480.83
   242.8   478.6   250.8  475.71   262.7  466.28   270.7   465.6   283.2  466.46
   298.6  470.21   310.5     471   433.8  470.76  477.44469.3292  520.56467.2948
     557  468.76   628.6     469   656.4  476.58  682.02 481.184   696.1  483.64
     712  483.86     716  484.65   721.8  487.45   779.6  500.99   835.2  515.66
#Mann= 9 ,-1 , 0
       0     .12       0   92.45     .08       0  135.84     .12       0
   262.7    .045       0   283.2     .12       0  477.44     .06       0
  520.56     .12       0  682.02    .016       0   721.8     .12       0
Bank Sta=262.7,283.2
XS Rating Curve= 0 ,0
Exp/Cntr=0.3,0.1

Type RM Length L Ch R = 1 ,28490.1 ,321.1,323.7,325.7
XS GIS Cut Line= 3
      2373586.85      390189.661     2373719.367       389946.07
     2374242.805      389491.643
#Sta/Elev= 30
       0  519.86    31.7  512.67  134.32494.9122  138.21 494.174   174.3  488.81
     210  484.95   285.3  478.88  353.09475.6475   384.9  473.09   388.8  471.81
   399.2  466.03   404.8  465.17   414.2  465.64   424.7  466.38   444.6  470.69
  454.51469.6593   528.3  467.76   619.9  468.72   699.6  466.82  733.01467.2021
   759.3  468.37   775.3   467.4   787.2  470.07   803.2  475.79  830.91480.1373
     843  482.54   862.9  483.01  872.53486.8505   926.7  497.84   970.5  508.53
#Mann= 10 ,-1 , 0
       0     .06       0  134.32     .12       0  138.21     .06       0
  353.09     .12       0   399.2    .045       0   414.2     .12       0
  454.51     .06       0  733.01     .12       0  830.91    .016       0
  872.53     .12       0
Bank Sta=399.2,414.2
XS Rating Curve= 0 ,0
Exp/Cntr=0.3,0.1