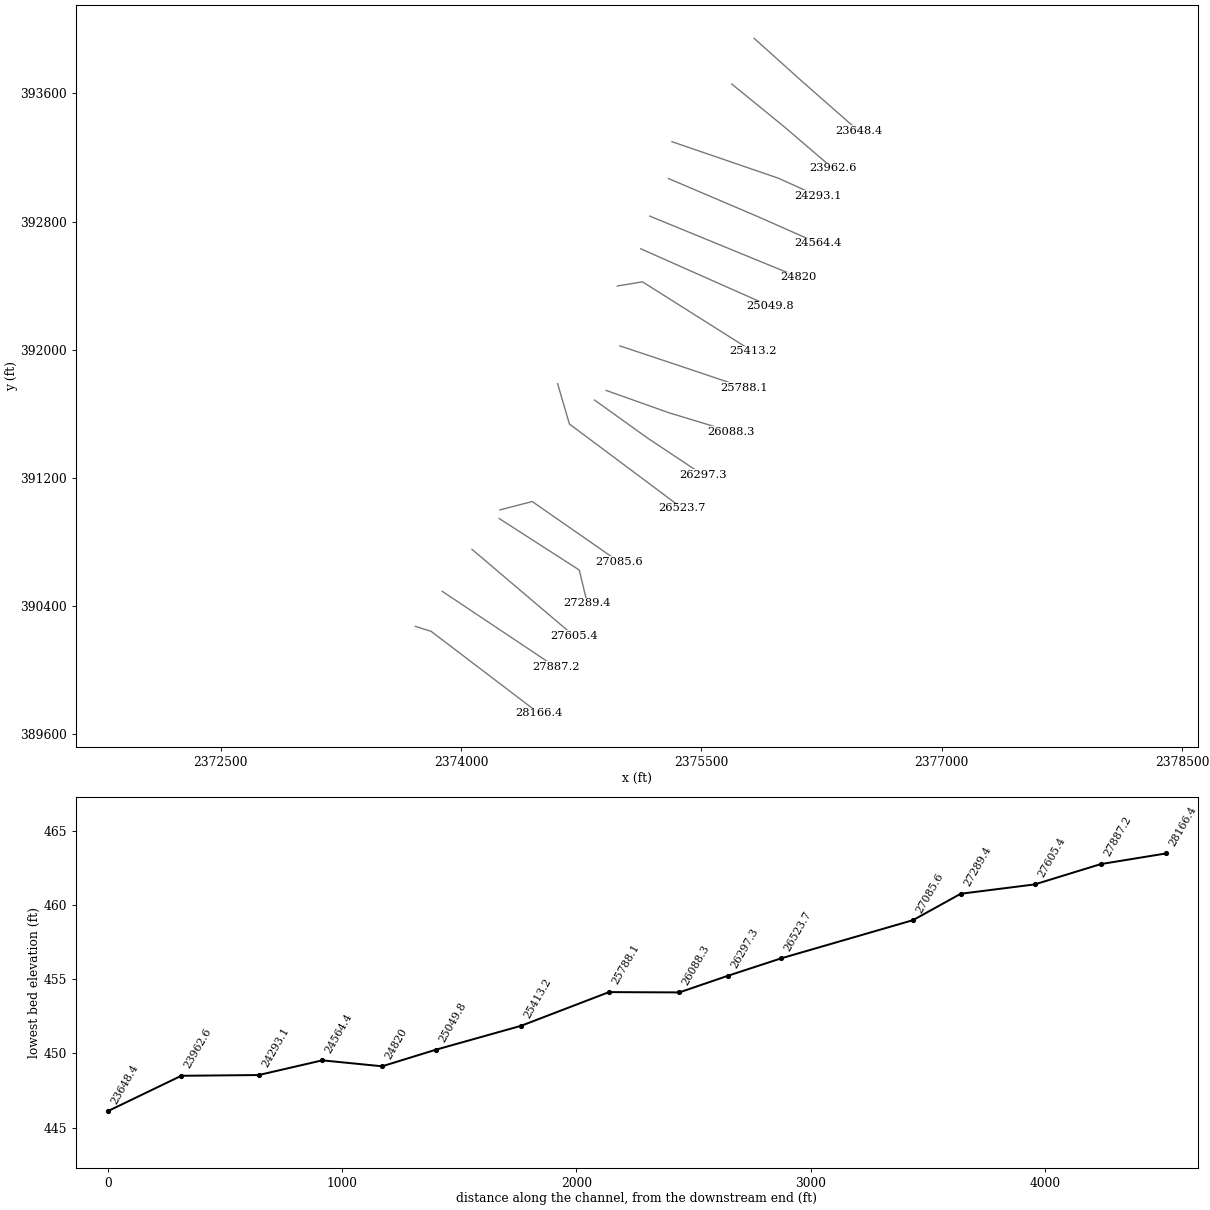
HEC-RAS study TILHANCECK.prj: TILHANCECK

--- TILHANCECK.g01 (geometry) --- (continued)

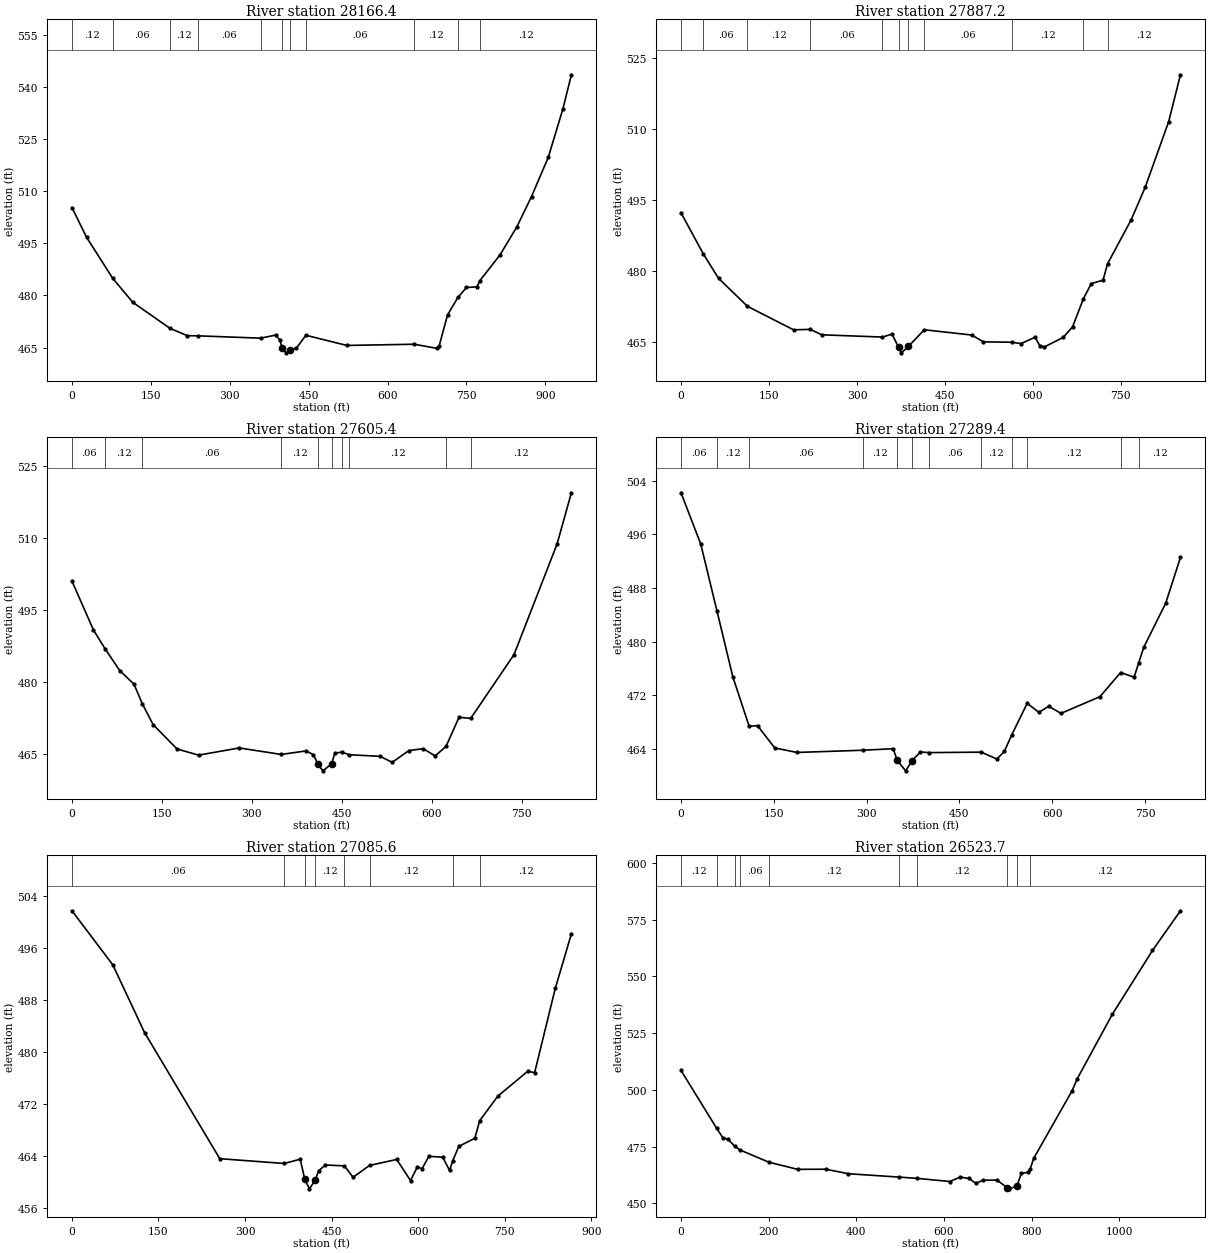
Type RM Length L Ch R = 1 ,28166.4 ,275.8,279.2,282
XS GIS Cut Line= 3
     2373715.461      390272.893     2373814.419      390241.643
     2374487.596      389729.924
#Sta/Elev= 30
       0  505.29    27.9  496.69   77.66484.8838   115.7  478.01   186.5 470.511
   219.4  468.42   239.9468.3712  358.49467.6995     387  468.58     395  467.22
   399.5  464.93   406.9  463.48   414.5  464.23   426.8  464.88  444.76468.5362
   522.6  465.61  650.42465.9544   694.1  464.77   698.1   465.5     714   474.4
  733.61479.4044   749.9  482.28   769.9  482.46   775.5484.2615   813.8  491.67
   845.7  499.71   873.6  508.44   905.5  519.74   933.4  533.72   949.4  543.48
#Mann= 11 ,-1 , 0
       0     .12       0   77.66     .06       0   186.5     .12       0
   239.9     .06       0  358.49     .12       0   399.5    .045       0
   414.5     .12       0  444.76     .06       0  650.42     .12       0
  733.61    .016       0   775.5     .12       0
Bank Sta=399.5,414.5
XS Rating Curve= 0 ,0
Exp/Cntr=0.3,0.1

Type RM Length L Ch R = 1 ,27887.2 ,284.7,281.9,279.3
XS GIS Cut Line= 2
      2373883.43      390491.643     2374591.763      390018.987
#Sta/Elev= 30
       0  492.35   38.31 483.599      64   478.5  113.31472.5855   191.9  467.62
  220.45467.7152   239.9  466.57  343.55466.0919   359.8  466.72  370.85  463.95
   375.8  462.76   387.8  464.13  414.87 467.636   495.7  466.52   515.7  465.08
  564.37464.9983   579.7  464.71   603.7  466.06   611.7  464.29   619.7  464.01
   651.7  466.03   667.6  468.24  686.26474.2307   699.6  477.39   719.6  478.12
  727.29481.5665   767.6  490.87   791.6  497.77   831.6  511.63   851.6   521.5
#Mann= 11 ,-1 , 0
       0     .12       0   38.31     .06       0  113.31     .12       0
  220.45     .06       0  343.55     .12       0  370.85    .045       0
   387.8     .12       0  414.87     .06       0  564.37     .12       0
  686.26    .016       0  727.29     .12       0
Bank Sta=370.85,387.8
XS Rating Curve= 0 ,0
Exp/Cntr=0.3,0.1

Type RM Length L Ch R = 1 ,27605.4 ,312.7,315.9,318.9
XS GIS Cut Line= 2
     2374069.073      390753.665     2374704.176      390214.833
#Sta/Elev= 30
       0     501    35.9   490.8   55.08 486.917    79.7  482.32   103.6  479.47
  117.22 475.425   135.5  471.02   175.3  465.95   211.2  464.67     279  466.17
  349.08464.8121   390.5  465.55   402.5  464.78   410.5  462.72   418.4  461.39
   432.9  462.81   438.4  465.07  449.63465.2968  462.79464.7449   514.1  464.42
     534  463.16   561.9  465.62   585.8  466.02   605.7   464.5  623.76466.4774
   645.6  472.57  665.01472.3427   737.2  485.65     809  508.74   832.9  519.45
#Mann= 10 ,-1 , 0
       0     .06       0   55.08     .12       0  117.22     .06       0
  349.08     .12       0   410.5    .045       0   432.9     .12       0
  449.63     .06       0  462.79     .12       0  623.76    .016       0
  665.01     .12       0
Bank Sta=410.5,432.9
XS Rating Curve= 0 ,0
Exp/Cntr=0.3,0.1

Type RM Length L Ch R = 1 ,27289.4 ,204.1,203.8,203.6
XS GIS Cut Line= 3
     2374238.898       390946.07     2374738.898      390624.455
     2374788.377      390417.424
#Sta/Elev= 30
       0  502.19    31.9  494.55   58.04484.6091    83.8  474.76  110.13467.4081
   123.7  467.49   151.6  464.17   187.5   463.5  294.95463.8326   343.1  464.06
  349.26  462.35   363.1  460.76  373.73   462.3     387  463.57  401.15463.4756
  485.21 463.546   510.7  462.52   522.7  463.66  534.47466.0794  559.67470.8215
   578.5  469.48   594.5  470.38   614.2  469.32   677.3  471.81  710.71475.4121
   732.5  474.71  739.99476.8942   748.2  479.18   783.7  485.77   807.4  492.56
#Mann= 12 ,-1 , 0
       0     .06       0   58.04     .12       0  110.13     .06       0
  294.95     .12       0  349.26    .045       0  373.73     .12       0
  401.15     .06       0  485.21     .12       0  534.47     .06       0
  559.67     .12       0  710.71    .016       0  739.99     .12       0
Bank Sta=349.26,373.73
XS Rating Curve= 0 ,0
Exp/Cntr=0.3,0.1

Type RM Length L Ch R = 1 ,27085.6 ,563,561.9,560.2
XS GIS Cut Line= 3
     2374243.239      390999.998     2374445.061      391052.081
     2374984.785      390677.137
#Sta/Elev= 30
       0  501.76    70.8  493.44   125.8  483.03   256.2  463.62  367.91462.8814
   395.6  463.54   403.6  460.43   411.6  458.98   421.7  460.33   427.5  461.76
   439.4  462.65  472.14462.5142   487.2  460.76  515.77462.5833   562.9   463.5
   586.8  460.25   598.8  462.38   606.7  462.06   618.7  463.99   642.6  463.84
   654.5  461.81  660.15463.3368   670.4  465.51   698.3  466.76  706.55469.4482
   738.2  473.25   789.9  477.06   801.9  476.86   837.7  489.82   865.6  498.21
#Mann= 8 ,-1 , 0
       0     .06       0  367.91     .12       0   403.6    .045       0
   421.7     .12       0  472.14     .06       0  515.77     .12       0
  660.15    .016       0  706.55     .12       0
Bank Sta=403.6,421.7
XS Rating Curve= 0 ,0
Exp/Cntr=0.3,0.1

Type RM Length L Ch R = 1 ,26523.7 ,224.8,226.3,227.6
XS GIS Cut Line= 3
     2374603.482      391787.758     2374677.266      391536.022
     2375380.391      391010.849
#Sta/Elev= 30
       0  508.56   81.22483.1242    95.4  478.93   107.3  478.23  122.41475.2243
  134.24473.5547  200.68468.1363   266.3  464.99   330.1  465.06     382  463.07
   496.9 461.592  538.39461.0384   613.4  459.64   637.3  461.59   657.2  460.97
   673.2  458.81   689.2  460.21   721.1  460.25     745  456.86     749  456.41
   766.5  457.63   776.9  463.25   792.9  463.71  797.17465.2757   804.8  469.78
   892.6  499.61   904.6  504.99   984.4  533.29  1076.1  561.41  1139.9  578.89
#Mann= 10 ,-1 , 0
       0     .12       0   81.22    .016       0  122.41     .12       0
  134.24     .06       0  200.68     .12       0   496.9     .06       0
  538.39     .12       0     745    .045       0   766.5    .016       0
  797.17     .12       0
Bank Sta=745,766.5
XS Rating Curve= 0 ,0
Exp/Cntr=0.3,0.1

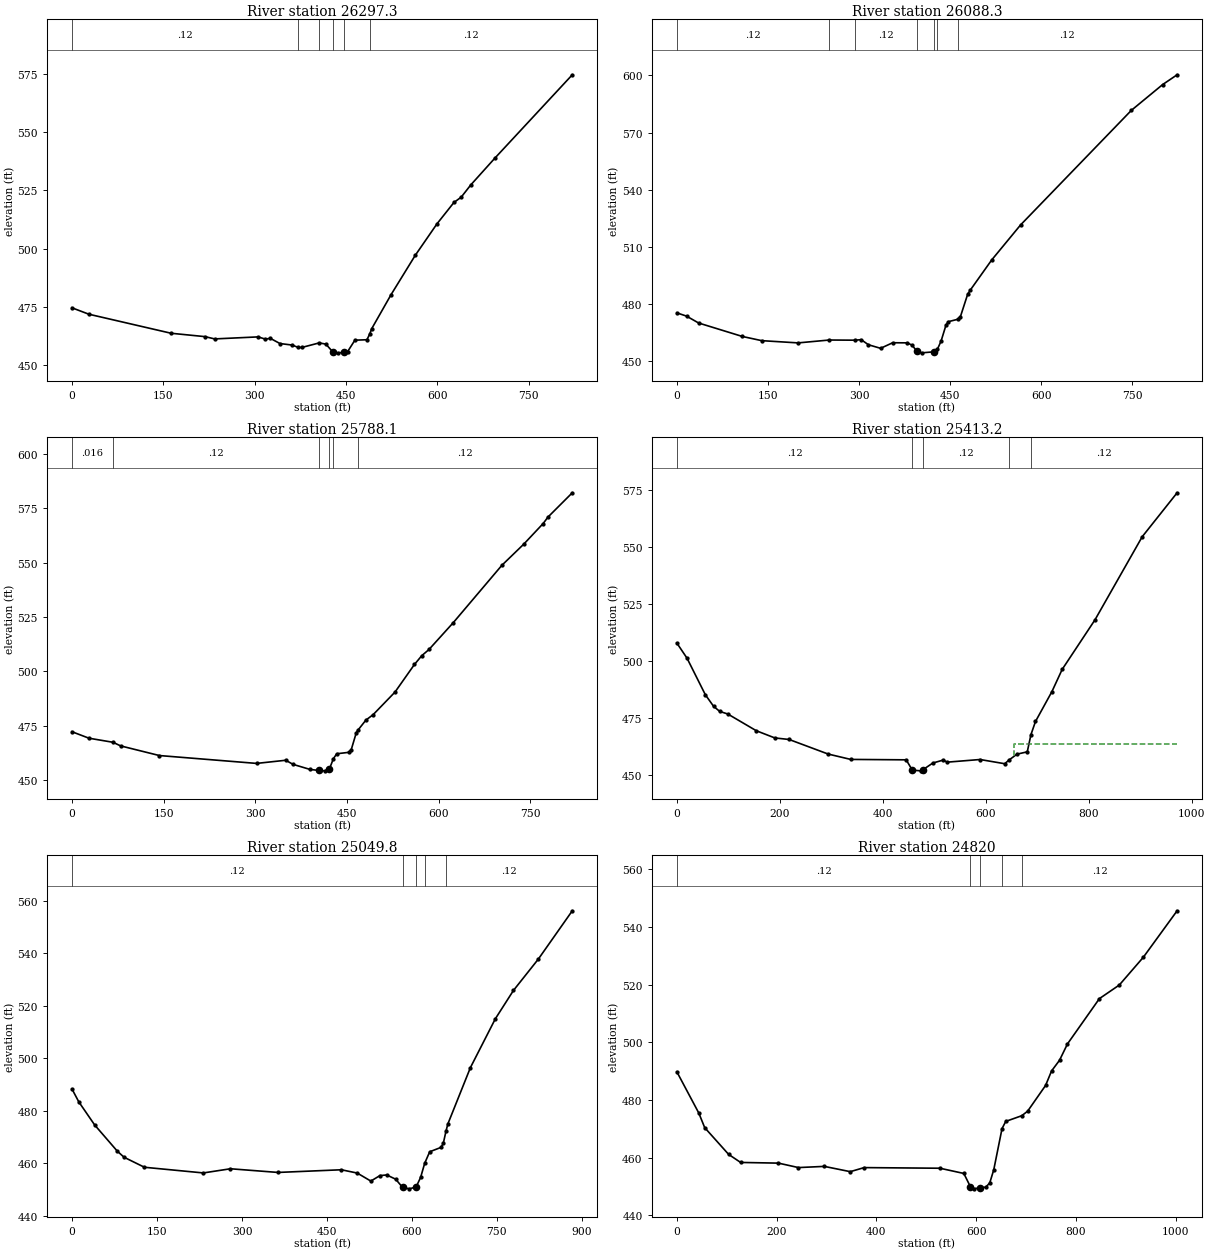
Type RM Length L Ch R = 1 ,26297.3 ,203.6,209,215.7
XS GIS Cut Line= 3
     2374834.028      391685.543     2375166.346      391447.408
     2375509.903      391219.106
#Sta/Elev= 30
       0  474.58    27.8  471.82   162.7  463.65   218.3   462.2   234.2  461.22
   305.6  462.09   317.5  461.12   325.5  461.48   341.4  459.23   361.2  458.59
   371.1 457.605   377.1  457.54   405.9459.5097   416.8  458.98   428.7  455.47
   436.6  455.24   447.2  455.41   452.5  455.78   464.4  460.68   484.2  460.86
  488.82463.3876   492.1  465.65   523.8  480.24   563.5  497.12   599.2  510.66
     627  519.83   638.9   522.1   654.7  527.38   694.4  538.92   821.3  574.67
#Mann= 6 ,-1 , 0
       0     .12       0   371.1    .016       0   405.9     .12       0
   428.7    .045       0   447.2    .016       0  488.82     .12       0
Bank Sta=428.7,447.2
XS Rating Curve= 0 ,0
Exp/Cntr=0.3,0.1

Type RM Length L Ch R = 1 ,26088.3 ,299.6,300.2,299.3
XS GIS Cut Line= 3
     2374906.571      391745.784     2375297.713      391606.439
     2375688.398      391487.926
#Sta/Elev= 30
       0  475.15      16  473.42    35.9   469.8   107.8  462.73   139.7  460.52
   199.6  459.34  250.93460.8528  293.65460.7675   303.4  461.05   315.4  458.36
   335.4  456.49   355.3  459.42   379.3  459.36   387.3  458.13   395.3  454.88
   403.2  454.11     423  454.64  428.98456.0272     435  460.32     443  468.64
   446.9   470.5  462.25 471.749   466.8  473.15   478.6   484.8   482.6  486.91
   518.3  502.97   565.8  521.38   748.2  581.67   799.7  595.23   823.5  600.37
#Mann= 7 ,-1 , 0
       0     .12       0  250.93    .016       0  293.65     .12       0
   395.3    .045       0     423     .12       0  428.98    .016       0
  462.25     .12       0
Bank Sta=395.3,423
XS Rating Curve= 0 ,0
Exp/Cntr=0.3,0.1

Type RM Length L Ch R = 1 ,25788.1 ,380.2,374.9,368
XS GIS Cut Line= 3
     2374992.393        392023.6     2375380.878      391894.105
     2375768.937      391763.326
#Sta/Elev= 30
       0  472.13    27.8  469.15   67.26467.2697    79.5  465.62   143.1  461.17
   302.2  457.55   349.9     459   361.8  457.12   389.6  454.78   404.8  454.29
   413.5  454.13   421.4  455.01  427.94459.7332   433.4  461.99   453.2  462.65
   457.2  463.94   465.2   471.5  467.66472.7048   481.1  477.48     493     480
   528.8   490.4   560.6   503.1   572.5  507.12   584.4  509.99   624.2  522.36
   703.7  548.74   739.5  558.47   771.3  567.98   779.2  570.95     819  582.13
#Mann= 6 ,-1 , 0
       0    .016       0   67.26     .12       0   404.8    .045       0
   421.4     .12       0  427.94    .016       0  467.66     .12       0
Bank Sta=404.8,421.4
XS Rating Curve= 0 ,0
Exp/Cntr=0.3,0.1

Type RM Length L Ch R = 1 ,25413.2 ,359.1,363.4,367.5
XS GIS Cut Line= 3
     2374976.745      392397.567     2375132.995      392423.609
      2375820.93      391989.581
#Sta/Elev= 30
       0  507.93    19.8  501.28    55.4  485.24    71.3   480.2    83.2  477.94
      99  476.79   154.4  469.45   190.3   466.3   218.2  465.61     294  459.22
   337.8  456.87   445.5  456.69   457.4  452.18   473.4  451.86   477.4  452.26
   497.3  455.29   517.3  456.57   525.2  455.67     589  456.83   636.9  454.98
  645.71456.6847   660.8  459.18   680.7  460.19  687.92467.7801   696.7  473.52
   728.6  486.62   748.5  496.35   812.3  518.12     904  554.56   971.8  573.83
#Mann= 5 ,-1 , 0
       0     .12       0   457.4    .045       0   477.4     .12       0
  645.71    .016       0  687.92     .12       0
#XS Ineff= 2 , 0
                          654.69          463.57
Permanent Ineff=
       F       F
Bank Sta=457.4,477.4
XS Rating Curve= 0 ,0
Exp/Cntr=0.3,0.1

Type RM Length L Ch R = 1 ,25049.8 ,229,229.8,230.2
XS GIS Cut Line= 2
     2375122.145      392629.772     2375929.436      392271.699
#Sta/Elev= 30
       0  488.29      12   483.4      40   474.6    79.9  464.63    91.9  462.29
   127.9  458.47   231.8  456.31   279.7   457.9   363.6   456.5   475.5  457.52
   503.5  456.26   527.5  453.21   543.5  455.29   555.5  455.54   571.4  453.92
   583.4  450.82   595.4  450.25   607.4  450.96   615.4  454.62  622.55459.9904
   631.4  464.38   651.4  466.05   655.4  467.58  660.08472.1529   663.4  474.95
   703.3  496.47   747.3  515.07   779.2  525.85   823.2  537.82   883.1  556.22
#Mann= 5 ,-1 , 0
       0     .12       0   583.4    .045       0   607.4     .12       0
  622.55    .016       0  660.08     .12       0
Bank Sta=583.4,607.4
XS Rating Curve= 0 ,0
Exp/Cntr=0.3,0.1

Type RM Length L Ch R = 1 ,24820   ,256.1,255.6,255.1
XS GIS Cut Line= 2
     2375178.568      392833.765     2376106.523      392453.064
#Sta/Elev= 30
       0  489.76      44  475.45    55.9  470.36   103.9  461.08   127.9  458.29
   203.8  458.05   243.8  456.51   295.7  456.92   347.7  455.09   375.6   456.5
   527.5  456.28   575.4  454.47   588.6  449.85   595.4  449.13   607.4   449.5
   619.4   449.7   627.4  451.21   635.4  455.76  651.96470.0242   659.4  472.53
  691.55474.5069   703.3  476.08   739.3  485.01   751.3  490.05   767.2  493.73
   783.2  499.43   847.2  515.14   887.1  519.86   935.1  529.46    1003  545.62
#Mann= 5 ,-1 , 0
       0     .12       0   588.6    .045       0   607.4     .12       0
  651.96    .016       0  691.55     .12       0
Bank Sta=588.6,607.4
XS Rating Curve= 0 ,0
Exp/Cntr=0.3,0.1

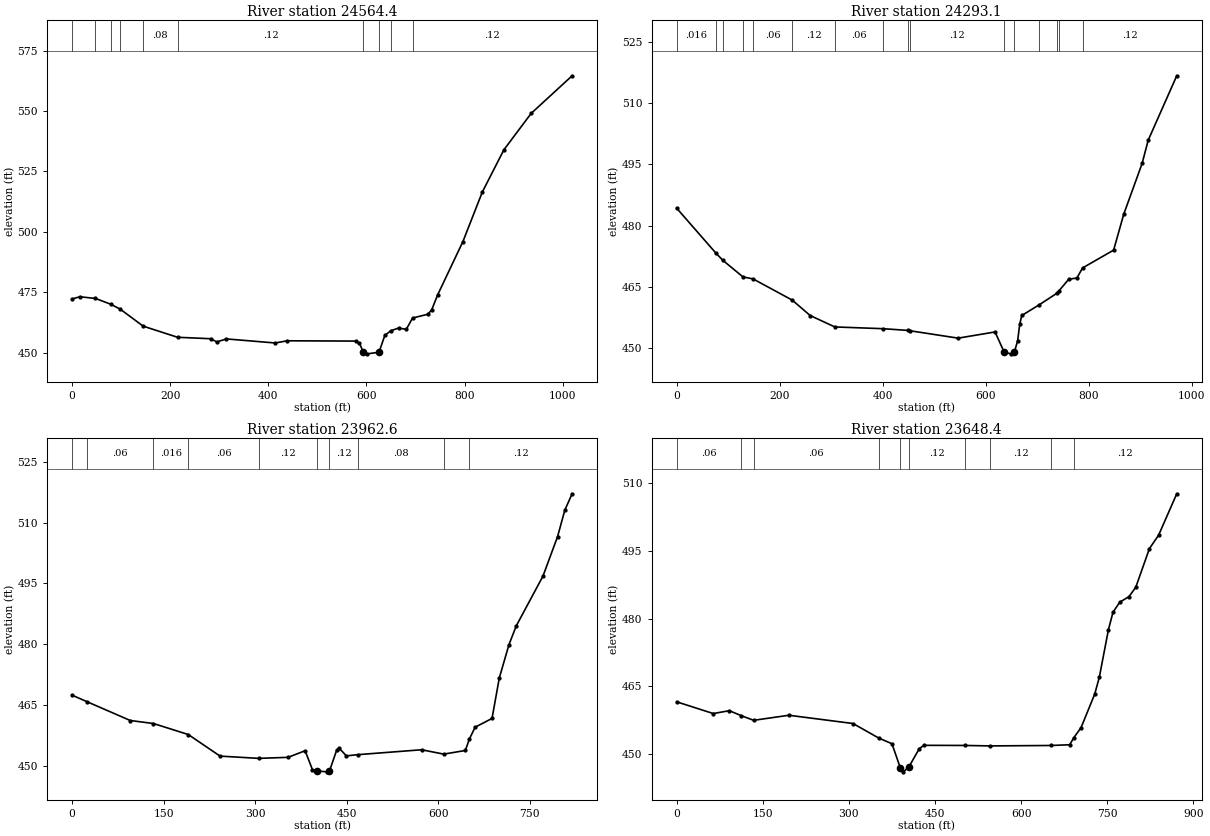
Type RM Length L Ch R = 1 ,24564.4 ,270.2,271.3,273.5
XS GIS Cut Line= 3
     2375295.756       393068.14     2375856.747      392829.079
      2376231.25      392663.435
#Sta/Elev= 30
       0  472.21    15.9  473.15   47.91472.4445   79.77 469.993   98.77467.9498
     145460.9887   215.2  456.38     283  455.78   294.9  454.45   314.9   455.7
   414.5  454.02   438.4  454.93   577.9  454.81   585.9   453.9   593.9  450.17
   601.8  449.53   625.7  450.19   637.6  457.16  649.99  459.11   665.5  460.18
   681.4  459.69  694.12464.3505   725.1   465.9     733  467.68     745  473.82
   796.7  495.96   836.4  516.52   880.2  533.93   935.8     549  1019.3  564.57
#Mann= 10 ,-1 , 0
       0    .016       0   47.91     .08       0   79.77     .06       0
   98.77     .12       0     145     .08       0   215.2     .12       0
   593.9    .045       0   625.7     .12       0  649.99    .016       0
  694.12     .12       0
Bank Sta=593.9,625.7
XS Rating Curve= 0 ,0
Exp/Cntr=0.3,0.1

Type RM Length L Ch R = 1 ,24293.1 ,337.9,330.5,321.5
XS GIS Cut Line= 3
     2375317.457      393298.175      2375981.52       393070.31
     2376226.745      392959.633
#Sta/Elev= 30
       0  484.29   75.96473.2984   89.95471.4642   128.8 467.418  148.37466.9284
  224.46461.7234   259.3  457.94  307.16455.1414  401.63454.7073  449.13454.2867
  452.68454.2136   546.5  452.39   618.3  453.91   636.3  448.87   650.2  448.54
  655.87  448.99   662.2   451.8   666.2  455.82   670.2  457.95  703.26 460.513
  738.71463.4305  742.51 464.006   761.4  466.86   777.2  467.14  788.14469.6114
   848.5  473.99   868.2  482.82   903.8  495.25   915.7  500.98   971.1  516.77
#Mann= 16 ,-1 , 0
       0    .016       0   75.96     .12       0   89.95     .06       0
   128.8    .016       0  148.37     .06       0  224.46     .12       0
  307.16     .06       0  401.63     .12       0  449.13     .06       0
  452.68     .12       0   636.3    .045       0  655.87     .12       0
  703.26     .06       0  738.71     .12       0  742.51    .016       0
  788.14     .12       0
Bank Sta=636.3,655.87
XS Rating Curve= 0 ,0
Exp/Cntr=0.3,0.1

Type RM Length L Ch R = 1 ,23962.6 ,315.3,314.1,313.7
XS GIS Cut Line= 3
     2375690.989      393657.684     2376008.721      393399.015
     2376320.209      393132.991
#Sta/Elev= 30
       0  467.43   25.12465.7661    95.5  461.16  133.34460.4195  190.49457.7021
   242.6  452.37  305.79451.8164     354  452.07   381.9   453.7   393.8  449.06
   401.1  448.72   417.7  448.49   421.6   448.6   433.6  453.83   437.6  454.34
   449.5  452.43  468.56452.7342   572.8  453.94  609.02452.8622   644.4  453.76
  651.06456.5945   660.3   459.5   688.1  461.67     700  471.65   715.9  479.91
   727.9  484.54   771.6  496.82   795.5  506.56   807.4  513.11   819.3  517.12
#Mann= 10 ,-1 , 0
       0     .12       0   25.12     .06       0  133.34    .016       0
  190.49     .06       0  305.79     .12       0   401.1    .045       0
   421.6     .12       0  468.56     .08       0  609.02    .016       0
  651.06     .12       0
Bank Sta=401.1,421.6
XS Rating Curve= 0 ,0
Exp/Cntr=0.3,0.1

Type RM Length L Ch R = 1 ,23648.4 ,290.5,290.9,292.2
XS GIS Cut Line= 3
     2375830.414      393943.319     2376127.147      393676.676
     2376481.924       393365.26
#Sta/Elev= 30
       0  461.61    63.8  459.01    91.8  459.64  112.83458.5266  134.16457.5112
   195.5  458.63   307.2   456.8  351.74453.6011     375  452.32   389.6  446.97
     395   446.1   404.6  447.21   422.7  451.26   430.7  451.97  501.63451.9435
  546.04451.8413  651.77451.9368   684.6   452.1  691.51453.6329   704.4  455.91
   728.2  463.35   736.1  467.04     752  477.57   759.9  481.43   771.8  483.69
   787.7  484.89   799.6  486.97   823.4  495.55   839.3  498.49     871  507.68
#Mann= 10 ,-1 , 0
       0     .06       0  112.83     .08       0  134.16     .06       0
  351.74     .12       0   389.6    .045       0   404.6     .12       0
  501.63    .016       0  546.04     .12       0  651.77    .016       0
  691.51     .12       0
Bank Sta=389.6,404.6
XS Rating Curve= 0 ,0
Exp/Cntr=0.3,0.1