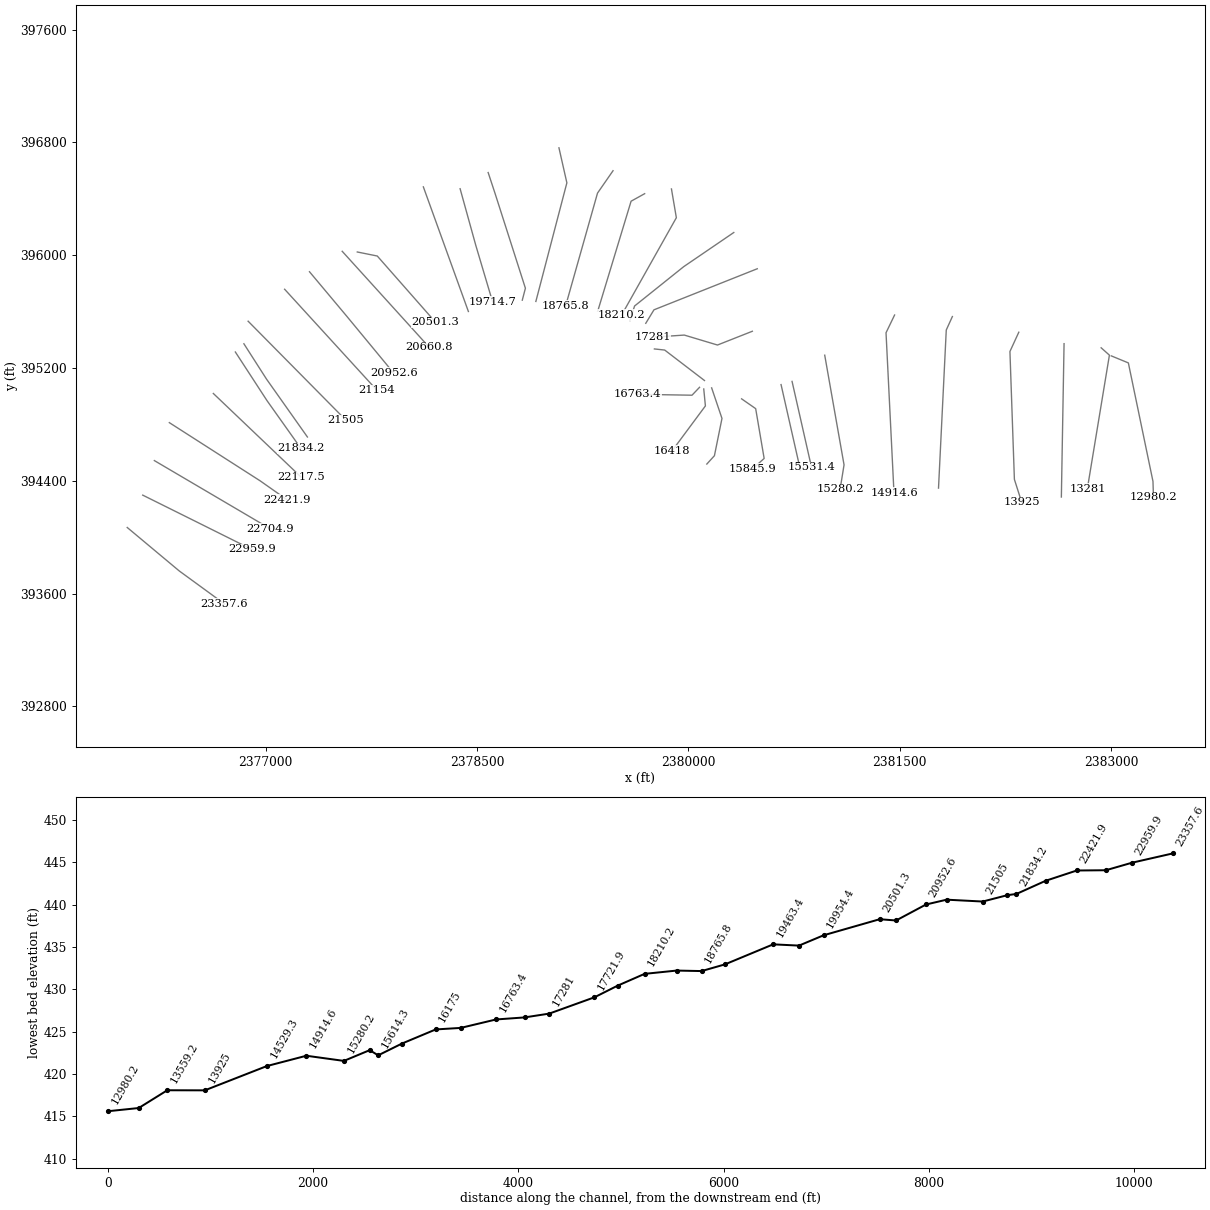
HEC-RAS study TILHANCECK.prj: TILHANCECK

--- TILHANCECK.g01 (geometry) --- (continued)

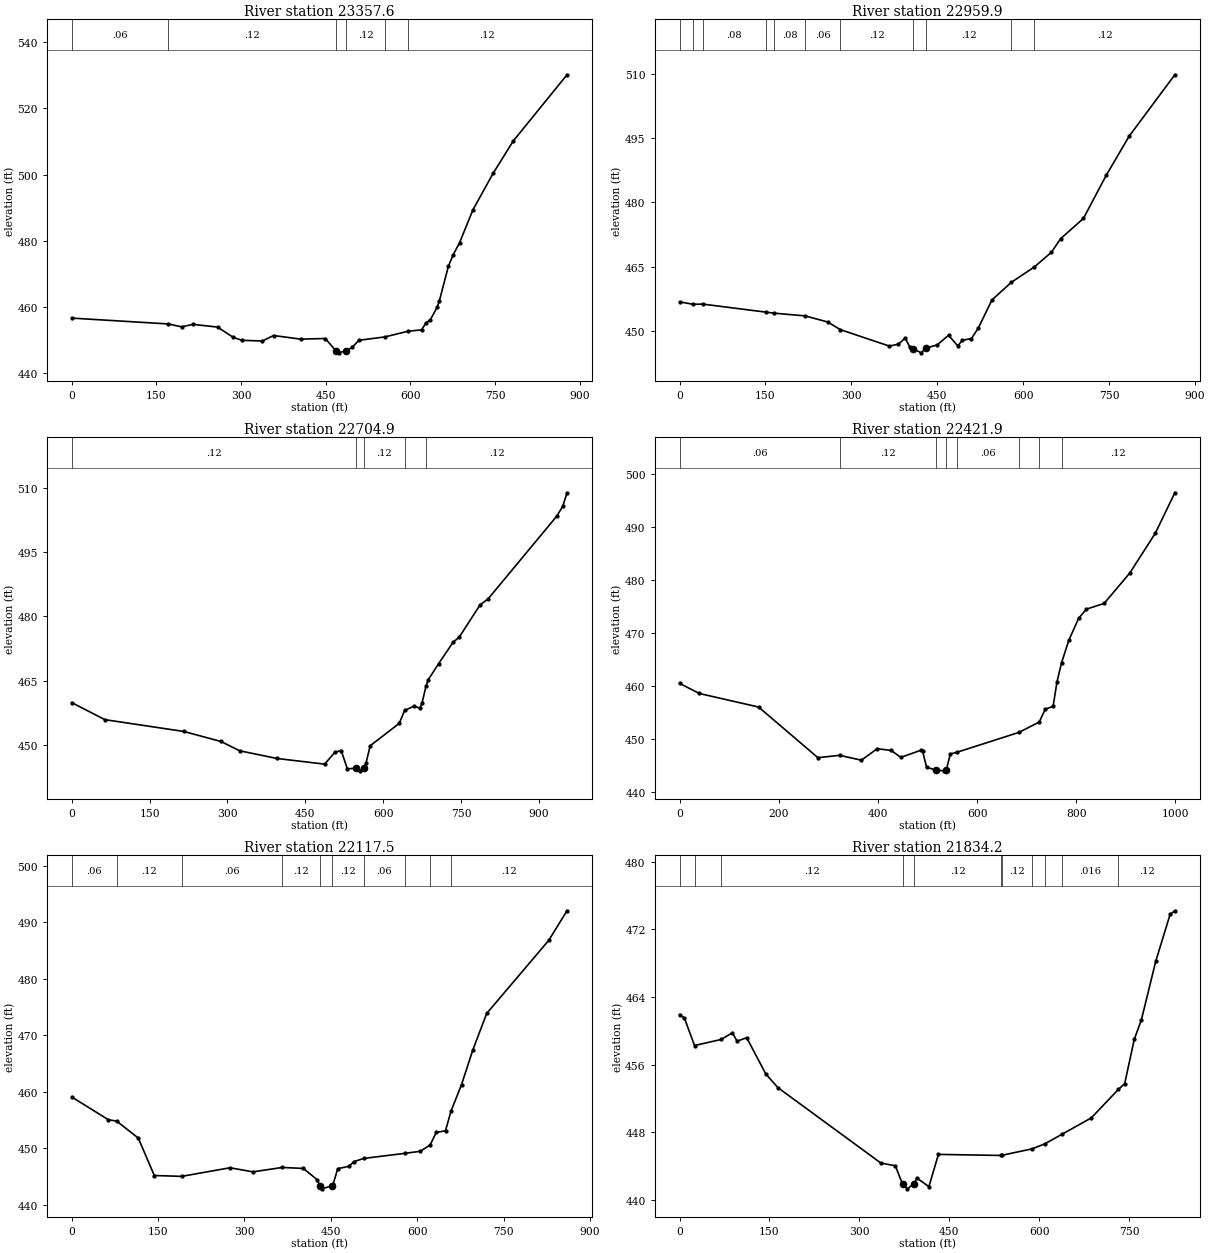
Type RM Length L Ch R = 1 ,23357.6 ,392.3,397.7,401.6
XS GIS Cut Line= 3
     2376016.858      394069.402     2376386.092      393761.194
     2376706.649      393527.609
#Sta/Elev= 30
       0  456.58  171.06454.8092   194.8  453.93   214.6  454.68   258.4  453.86
   286.2  450.75   302.1  449.85   337.9  449.66   357.7  451.31   405.4  450.22
   449.2   450.4  468.02  446.72     473  446.07   486.3  446.73   496.8  447.69
   508.7  449.86  554.99450.8928  595.56452.5903   619.8  453.02   627.7  455.12
   635.6  456.11   647.6  459.93   651.5  461.86   667.4  472.25   675.3  475.53
   687.2  479.37     711  489.36   746.7  500.39   782.4  510.16   877.6  530.18
#Mann= 6 ,-1 , 0
       0     .06       0  171.06     .12       0  468.02    .045       0
   486.3     .12       0  554.99    .016       0  595.56     .12       0
Bank Sta=468.02,486.3
XS Rating Curve= 0 ,0
Exp/Cntr=0.3,0.1

Type RM Length L Ch R = 1 ,22959.9 ,256.4,255,253.3
XS GIS Cut Line= 3
     2376126.908      394298.859     2376511.875       394107.63
     2376901.079      393913.904
#Sta/Elev= 30
       0  456.85   23.37456.2853   40.66456.3228  150.61 454.457  164.82454.2157
  219.27453.5763   258.7  452.15  280.75450.3734   366.2  446.54   382.1  446.99
     394  448.44     402  446.27     407  445.96   421.9  444.97   429.8  446.04
   449.8  446.83   469.7  449.07   485.7  446.57   493.7   447.9   509.6   448.3
   521.6  450.76   545.5  457.31  578.96461.3711  619.61465.0006   649.2   468.4
   665.2  471.56   705.1  476.29   744.9  486.34   784.8  495.43   864.6  509.75
#Mann= 11 ,-1 , 0
       0     .08       0   23.37     .12       0   40.66     .08       0
  150.61     .06       0  164.82     .08       0  219.27     .06       0
  280.75     .12       0     407    .045       0   429.8     .12       0
  578.96    .016       0  619.61     .12       0
Bank Sta=407,429.8
XS Rating Curve= 0 ,0
Exp/Cntr=0.3,0.1

Type RM Length L Ch R = 1 ,22704.9 ,284,283,282.2
XS GIS Cut Line= 2
     2376209.384      394543.835     2377032.096      394060.182
#Sta/Elev= 30
       0  459.95    63.9  455.99   215.6  453.25   287.5  450.91   323.4  448.75
   395.3  446.96   487.2  445.64   507.1   448.4   519.1  448.81   531.1  444.55
     547  444.68     555  444.08     563  444.77     567  445.84     575  449.92
   630.9   455.1  641.39458.1282   658.9  459.11   670.8  458.69   674.8  459.77
   682.6 463.789   686.8  465.27   706.8     469   734.7  473.99   746.7   475.2
   786.6  482.66   802.6  484.14   934.4  503.31   946.4  505.72   954.3  508.78
#Mann= 5 ,-1 , 0
       0     .12       0     547    .045       0     563     .12       0
  641.39    .016       0   682.6     .12       0
Bank Sta=547,563
XS Rating Curve= 0 ,0
Exp/Cntr=0.3,0.1

Type RM Length L Ch R = 1 ,22421.9 ,308.2,304.4,299.9
XS GIS Cut Line= 3
     2376315.721      394812.932     2376960.127       394400.27
     2377151.225      394266.057
#Sta/Elev= 30
       0  460.56    39.8  458.65   159.4  456.09     279  446.53  322.68 446.977
   366.7  446.06   398.6  448.23   426.4   447.9   446.4  446.59   486.2  447.92
   490.2  447.72   498.2  444.71   518.1  444.18     534  444.05     538  444.25
     546  447.23  559.07447.5468  684.19451.2979  725.37453.2663   737.3  455.67
   753.3  456.24   761.2   460.9  770.39464.4723     785  468.71   804.8  472.85
   820.6  474.57   856.2  475.65   907.7  481.36   959.2  488.87   998.7  496.53
#Mann= 8 ,-1 , 0
       0     .06       0  322.68     .12       0   518.1    .045       0
     538     .12       0  559.07     .06       0  684.19     .12       0
  725.37    .016       0  770.39     .12       0
Bank Sta=518.1,538
XS Rating Curve= 0 ,0
Exp/Cntr=0.3,0.1

Type RM Length L Ch R = 1 ,22117.5 ,289.6,283.3,271.2
XS GIS Cut Line= 2
     2376628.059      395019.673     2377250.903      394426.495
#Sta/Elev= 30
       0   459.1    63.7  455.06   77.92454.8288   115.5  451.83   143.4  445.19
  190.76445.0374   274.8  446.56   314.6  445.84  365.79446.6174   402.2  446.44
   426.1  444.46   431.2  443.28     434  442.83   451.5  443.35     454  443.68
   461.9   446.4   481.8  446.83   489.8  447.64  507.36448.2198  578.17449.1115
   605.3  449.48  622.39450.5969   633.1  452.83   649.1  453.11  658.48456.5459
   676.9  461.28   696.8   467.5   720.7   473.9   828.3  486.82   860.1  492.07
#Mann= 10 ,-1 , 0
       0     .06       0   77.92     .12       0  190.76     .06       0
  365.79     .12       0   431.2    .045       0   451.5     .12       0
  507.36     .06       0  578.17     .12       0  622.39    .016       0
  658.48     .12       0
Bank Sta=431.2,451.5
XS Rating Curve= 0 ,0
Exp/Cntr=0.3,0.1

Type RM Length L Ch R = 1 ,21834.2 ,89.4,90.1,94.5
XS GIS Cut Line= 3
      2376784.24      395313.891     2377009.092      394968.696
     2377248.998      394630.862
#Sta/Elev= 30
       0  461.92       8  461.52   24.98458.2531    69.5458.9713      88  459.76
      96  458.77     112  459.18     144  454.87     164  453.27     336  444.33
     360  444.01     372  441.85     380  441.28   391.1  441.89     396  442.56
     416  441.54   431.9  445.36  536.32445.2323  538.23 445.261  588.04446.0114
  609.24446.6022  637.85 447.735   686.9  449.68  732.14453.0576   742.6  453.72
   758.6  458.98   770.5  461.29   794.4  468.21   818.4  473.78   826.3  474.21
#Mann= 11 ,-1 , 0
       0     .06       0   24.98     .04       0    69.5     .12       0
     372    .045       0   391.1     .12       0  536.32     .06       0
  538.23     .12       0  588.04    .016       0  609.24     .12       0
  637.85    .016       0  732.14     .12       0
Bank Sta=372,391.1
XS Rating Curve= 0 ,0
Exp/Cntr=0.3,0.1

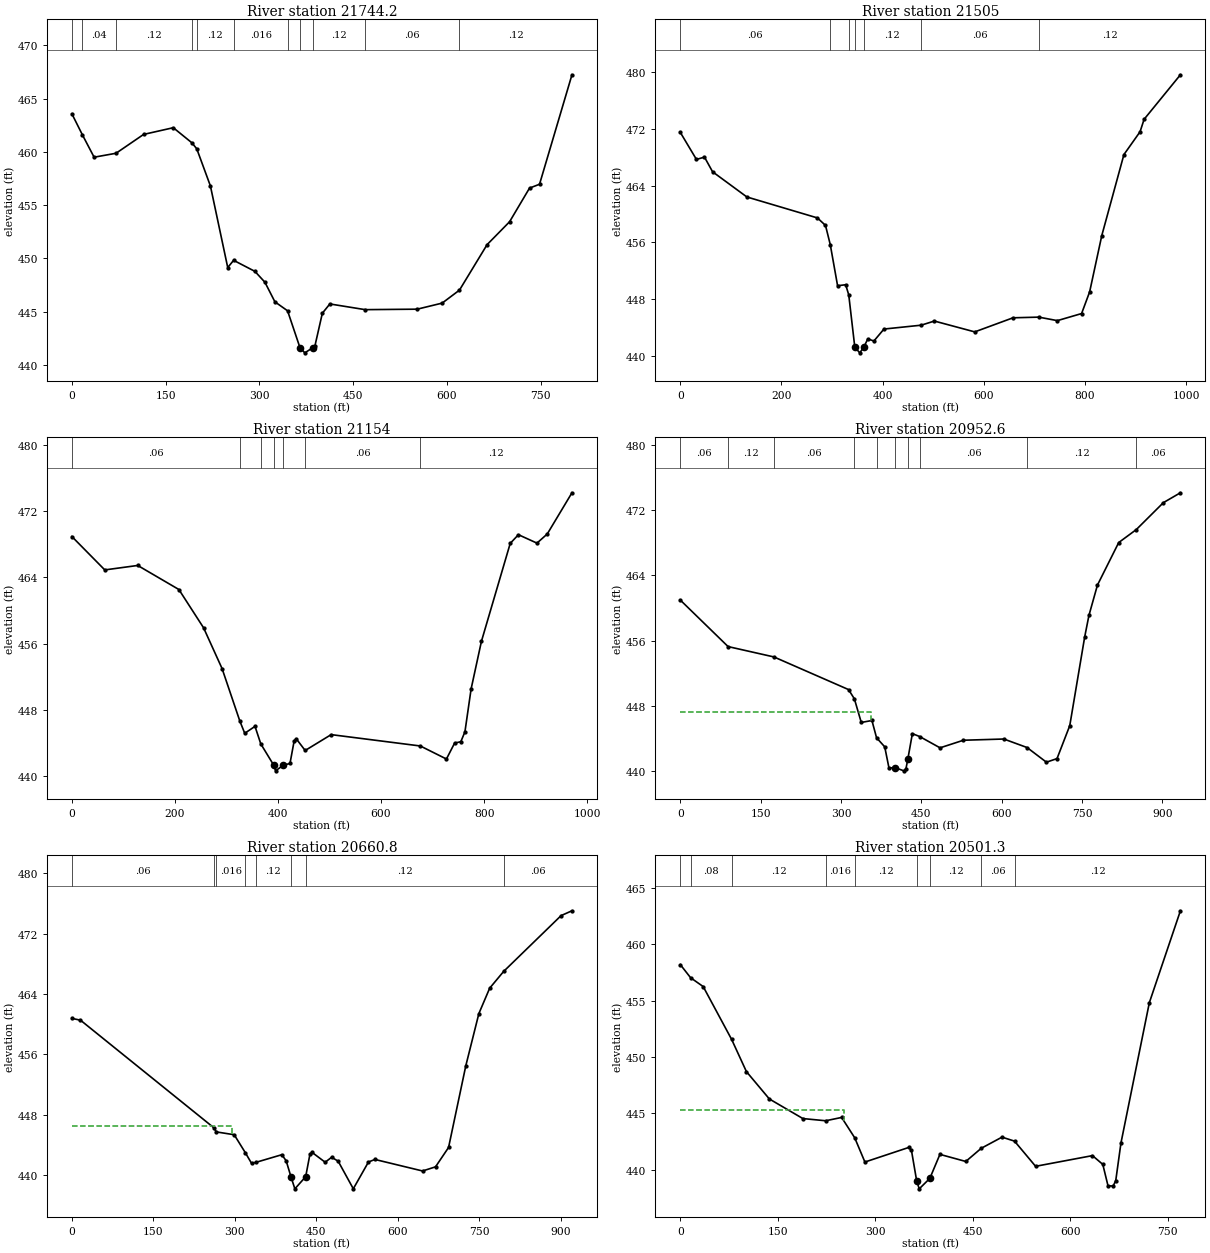
Type RM Length L Ch R = 1 ,21744.2 ,234.5,239.2,243.7
XS GIS Cut Line= 3
     2376844.888      395372.133     2377005.044      395122.133
     2377295.656      394711.157
#Sta/Elev= 30
       0  463.58   16.69461.6209    35.6   459.5   70.69459.8702   114.8  461.64
   162.3  462.27  191.99460.8554  199.85460.2911   221.7   456.8   249.4  449.14
  258.83449.8165   292.9  448.78   308.9  447.76   324.9  445.92  345.15 445.077
  365.09   441.6   372.8  441.13  385.43  441.61   388.8  441.75   400.8  444.85
   412.8  445.72  469.35445.1851   552.6  445.23   592.5   445.8  620.21447.0198
   664.4  451.29   700.4  453.44   732.3   456.6   748.3  456.96   800.2  467.24
#Mann= 11 ,-1 , 0
       0     .06       0   16.69     .04       0   70.69     .12       0
  191.99     .06       0  199.85     .12       0  258.83    .016       0
  345.15     .12       0  365.09    .045       0  385.43     .12       0
  469.35     .06       0  620.21     .12       0
Bank Sta=365.09,385.43
XS Rating Curve= 0 ,0
Exp/Cntr=0.3,0.1

Type RM Length L Ch R = 1 ,21505   ,353.3,351.1,347.8
XS GIS Cut Line= 2
     2376874.836      395532.289     2377570.148      394829.164
#Sta/Elev= 30
       0  471.52    31.9   467.7    47.8  468.03    63.8  465.96   131.6   462.4
   271.1  459.44   287.1  458.38  296.56455.6586     311  449.86     327     450
  333.07448.5703  345.05  441.17   354.9  440.38   362.8  441.18   370.8  442.35
   382.8  442.05   402.7  443.74  476.11444.2839   502.4  444.87   582.2  443.34
   657.9  445.33  708.87 445.424   745.6  444.93   793.5  445.93   809.4  448.99
   833.4  456.94   877.2  468.39   909.1  471.61   917.1  473.37   988.9  479.66
#Mann= 7 ,-1 , 0
       0     .06       0  296.56    .016       0  333.07     .12       0
  345.05    .045       0   362.8     .12       0  476.11     .06       0
  708.87     .12       0
Bank Sta=345.05,362.8
XS Rating Curve= 0 ,0
Exp/Cntr=0.3,0.1

Type RM Length L Ch R = 1 ,21154   ,202,201.3,200.1
XS GIS Cut Line= 2
      2377133.95      395758.852     2377788.898      395042.706
#Sta/Elev= 30
       0  468.94    63.9   464.9   127.8  465.44   207.7  462.53   255.6   457.9
   291.5  452.97  325.99446.6194   335.5  445.14   355.4  445.98  366.66443.8576
   391.4  441.32   395.4   440.6   410.1  441.28   423.3  441.49   431.3  444.19
   435.3  444.49  452.77443.0616   503.2  444.98   676.2443.6068   726.9  442.03
   742.8  443.96   754.8  444.12   762.8  445.32   774.8  450.51   794.8  456.26
   850.7  468.11   866.6  469.16   902.6  468.14   922.6  469.25   970.5  474.23
#Mann= 7 ,-1 , 0
       0     .06       0  325.99    .016       0  366.66     .12       0
   391.4    .045       0   410.1     .12       0  452.77     .06       0
   676.2     .12       0
Bank Sta=391.4,410.1
XS Rating Curve= 0 ,0
Exp/Cntr=0.3,0.1

Type RM Length L Ch R = 1 ,20952.6 ,290.9,291.8,292.7
XS GIS Cut Line= 3
     2377310.322      395883.043     2377573.432      395569.254
     2377907.388      395165.102
#Sta/Elev= 30
       0  460.96   89.23 455.259  174.82453.9896   314.1  449.99  325.01 448.856
   337.9  445.96   357.8   446.2  366.44444.0818   381.7  442.97   389.6  440.39
   401.6  440.41   417.4  440.03   421.4  440.31   424.9  441.49   433.3  444.59
  447.05444.2305     485  442.85   528.6  443.78   604.1  443.93  647.51442.8851
   683.6  441.09   703.4  441.53   727.2  445.57     755  456.42     763  459.08
   778.9   462.8   818.6  468.01  851.44   469.6     902   472.9   933.8  474.11
#Mann= 10 ,-1 , 0
       0     .06       0   89.23     .12       0  174.82     .06       0
  325.01    .016       0  366.44     .12       0   401.6    .045       0
   424.9     .12       0  447.05     .06       0  647.51     .12       0
  851.44     .06       0
#XS Ineff= 2 , 0
          355.58  447.28
Permanent Ineff=
       F       F
Bank Sta=401.6,424.9
XS Rating Curve= 0 ,0
Exp/Cntr=0.3,0.1

Type RM Length L Ch R = 1 ,20660.8 ,159.9,159.5,159.2
XS GIS Cut Line= 2
       2377542.6      396027.997     2378161.294      395346.092
#Sta/Elev= 30
       0  460.76    15.9  460.52  261.39446.2465  265.97445.6958   298.9  445.32
  319.37442.9406   330.8  441.53  338.13441.6381   386.6  442.67   394.6  441.86
  403.38  439.75   410.6  438.14   430.5  439.75   438.4  442.75   442.4  442.97
   466.4  441.67   478.3  442.33   490.3  441.81   518.2  438.15   546.1   441.7
     558  442.04   645.7  440.51   669.6  441.06   693.6  443.63   725.4  454.49
   749.4   461.4   769.3  464.77  795.05 466.994   900.8   474.4   920.8  475.04
#Mann= 8 ,-1 , 0
       0     .06       0  261.39     .12       0  265.97    .016       0
  319.37     .06       0  338.13     .12       0  403.38    .045       0
   430.5     .12       0  795.05     .06       0
#XS Ineff= 2 , 0
          293.97  446.42
Permanent Ineff=
       F       F
Bank Sta=403.38,430.5
XS Rating Curve= 0 ,0
Exp/Cntr=0.3,0.1

Type RM Length L Ch R = 1 ,20501.3 ,554.9,546.9,506.5
XS GIS Cut Line= 3
     2377649.575      396023.175     2377791.502      395994.529
     2378204.263      395525.779
#Sta/Elev= 30
       0   458.2   15.85 457.035    35.2  456.25   78.98451.5564   101.7   448.7
     137  446.27   188.6  444.53  223.68444.3348   248.2  444.63  268.31442.8232
     284  440.67   351.7  441.97   355.6  441.71   363.6  439.01   367.6  438.29
   383.9  439.22   399.4  441.35   439.2  440.72  462.92 441.888   494.9  442.88
  514.16442.5272   546.6  440.29   634.1  441.24     650  440.46     658  438.56
   665.9  438.54   669.9  439.01   677.9  442.35   721.6  454.82   769.4  462.98
#Mann= 9 ,-1 , 0
       0     .12       0   15.85     .08       0   78.98     .12       0
  223.68    .016       0  268.31     .12       0   363.6    .045       0
   383.9     .12       0  462.92     .06       0  514.16     .12       0
#XS Ineff= 2 , 0
           251.6  445.33
Permanent Ineff=
       F       F
Bank Sta=363.6,383.9
XS Rating Curve= 0 ,0
Exp/Cntr=0.3,0.1

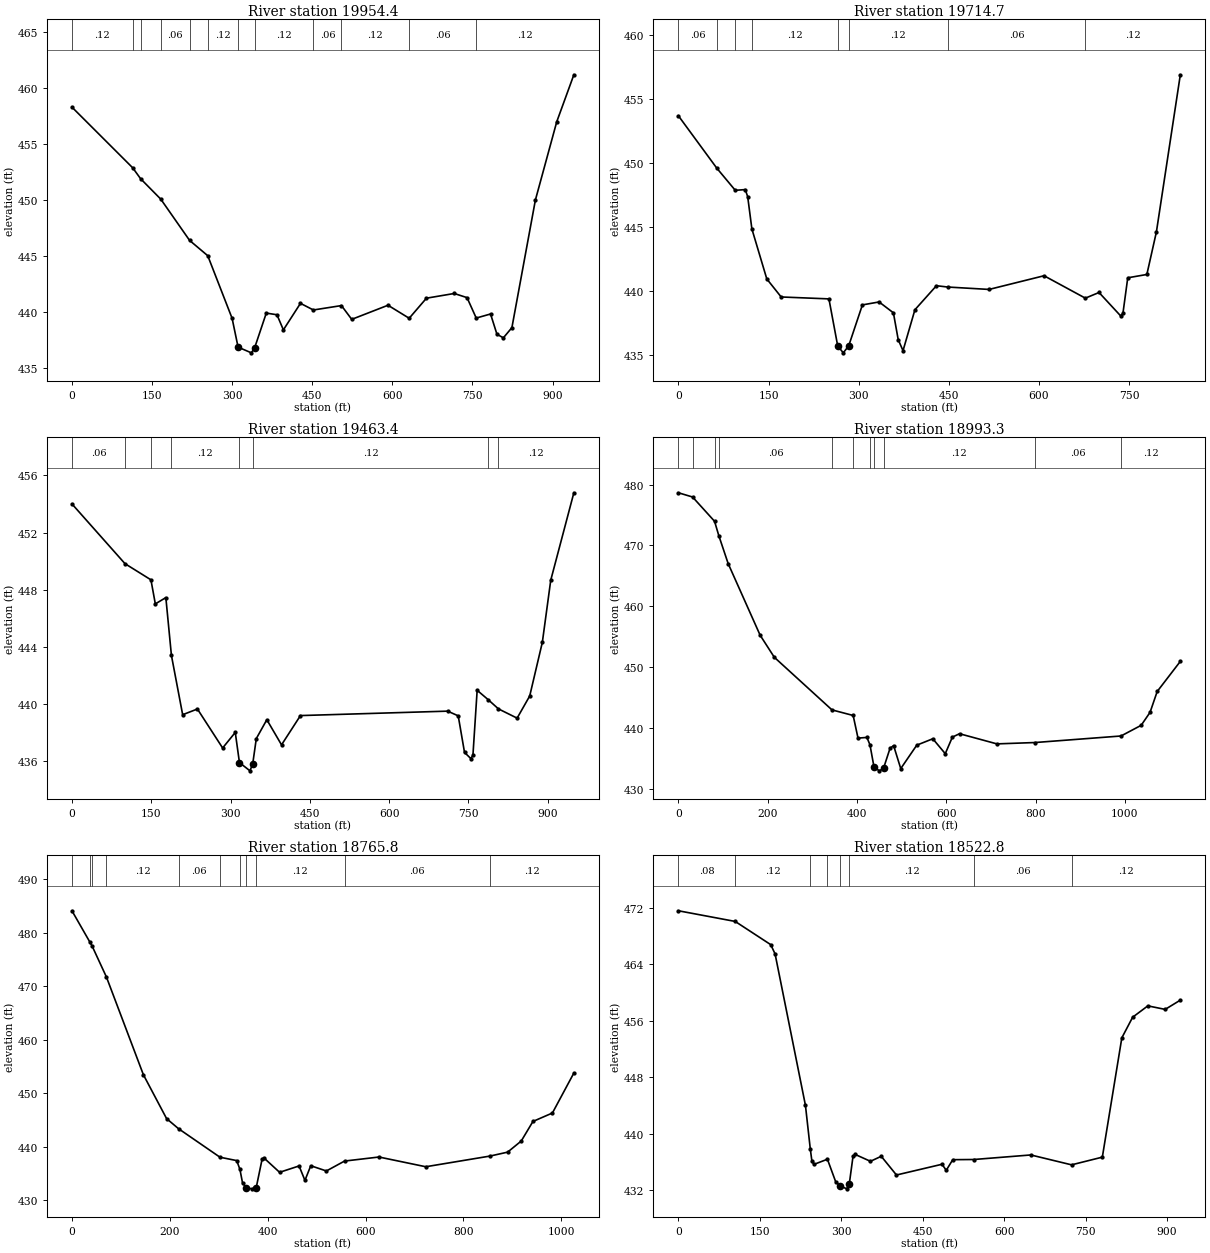
Type RM Length L Ch R = 1 ,19954.4 ,239.7,239.7,265.6
XS GIS Cut Line= 2
     2378118.456      396484.923     2378438.073      395601.184
#Sta/Elev= 30
       0  458.33  113.83452.9077  128.55451.9384   166.4  450.11  220.28446.4301
  254.31445.0617   299.9  439.47  311.08   436.9   335.9  436.39  342.08  436.84
   363.9  439.94   383.9  439.79   395.9  438.44   427.9  440.81  452.09440.2167
  504.62440.6102   523.9  439.38   591.8  440.64  631.47439.4772   663.8  441.27
   715.8  441.69   739.8  441.32     757 439.496   783.8  439.86   795.8  438.05
   807.8  437.73   823.8  438.64   867.8  450.04   907.8  457.03   939.8  461.22
#Mann= 12 ,-1 , 0
       0     .12       0  113.83     .06       0  128.55     .12       0
   166.4     .06       0  220.28    .016       0  254.31     .12       0
  311.08    .045       0  342.08     .12       0  452.09     .06       0
  504.62     .12       0  631.47     .06       0     757     .12       0
Bank Sta=311.08,342.08
XS Rating Curve= 0 ,0
Exp/Cntr=0.3,0.1

Type RM Length L Ch R = 1 ,19714.7 ,250.2,251.3,252.3
XS GIS Cut Line= 3
     2378379.327       396471.66     2378490.845      396069.348
     2378610.039      395668.873
#Sta/Elev= 30
       0  453.71   63.86 449.617   94.63447.8819   111.3  447.94   115.3  447.38
  122.26444.8638   147.1  440.95     171  439.54   250.5  439.39   265.1  435.71
   274.4  435.17  283.42  435.72   306.2  438.92     334  439.15   357.8   438.3
   365.8   436.2   373.8  435.34   393.6  438.54   429.4  440.42  448.21440.3173
     517  440.13   608.5   441.2  677.23439.4474     700  439.89   735.8  438.07
   739.8  438.26   747.8  441.04   779.6   441.3   795.5  444.63   835.3  456.92
#Mann= 8 ,-1 , 0
       0     .06       0   63.86     .12       0   94.63    .016       0
  122.26     .12       0   265.1    .045       0  283.42     .12       0
  448.21     .06       0  677.23     .12       0
Bank Sta=265.1,283.42
XS Rating Curve= 0 ,0
Exp/Cntr=0.3,0.1

Type RM Length L Ch R = 1 ,19463.4 ,483,470.1,457.2
XS GIS Cut Line= 4
     2378578.395      396586.456     2378627.874      396436.717
     2378842.718      395766.144     2378820.582      395681.508
#Sta/Elev= 30
       0  454.01   100.3449.8267  149.39448.6947   157.7  447.01   177.6  447.45
  188.15443.4008   209.4  439.25   237.3  439.65     285  436.92   308.9  438.01
   316.8   435.9   336.7  435.32   341.9  435.81   348.7  437.58   368.6   438.9
   396.4  437.14   432.2  439.19   710.7   439.5   730.6  439.17   742.5  436.61
   754.4  436.18   758.4   436.4   766.4  440.96  787.47 440.296  806.68439.6578
     842  439.01   865.8  440.56   889.7  444.32   905.6  448.67   949.3  454.79
#Mann= 8 ,-1 , 0
       0     .06       0   100.3     .12       0  149.39    .016       0
  188.15     .12       0   316.8    .045       0   341.9     .12       0
  787.47     .06       0  806.68     .12       0
Bank Sta=316.8,341.9
XS Rating Curve= 0 ,0
Exp/Cntr=0.3,0.1

Type RM Length L Ch R = 1 ,18993.3 ,228,227.5,227.1
XS GIS Cut Line= 3
     2379080.775      396761.839     2379136.989      396513.539
     2378916.936      395672.394
#Sta/Elev= 30
       0  478.65    31.7477.9557   80.93473.9667    90.4471.6175   111.4  467.01
     183  455.24   214.8  451.61  343.88442.9668  391.33442.0492   402.2  438.33
   422.1  438.44  428.96437.2307     438  433.58     450  432.95   459.3  433.36
   473.9  436.65   481.9   437.1   497.9  433.32   533.8  437.17   569.7  438.22
   597.6  435.77   613.5  438.49   629.5  439.05   713.2  437.38  798.28437.6008
  991.17438.6777  1036.3  440.43  1056.2  442.56  1072.2  445.99    1124  450.94
#Mann= 11 ,-1 , 0
       0     .12       0    31.7     .06       0   80.93     .12       0
    90.4     .06       0  343.88     .12       0  391.33    .016       0
  428.96     .12       0     438    .045       0   459.3     .12       0
  798.28     .06       0  991.17     .12       0
Bank Sta=438,459.3
XS Rating Curve= 0 ,0
Exp/Cntr=0.3,0.1

Type RM Length L Ch R = 1 ,18765.8 ,242.8,243,242.4
XS GIS Cut Line= 3
      2379464.68      396599.477     2379354.436      396440.623
     2379127.874      395639.842
#Sta/Elev= 30
       0  484.15   36.18478.3663   40.79477.6384   70.48471.7627     146  453.49
   193.4  445.29  217.76443.4082  302.51438.0705   336.7  437.44  343.22435.8057
   348.6  433.26   356.6  432.34   368.6  432.16   376.5  432.37   388.5  437.68
   392.4  437.93   424.3  435.25   464.1  436.44   476.1  433.74     488  436.48
   519.9   435.5  557.01437.3524   627.4  438.11     723  436.29  854.24438.2872
   890.2  439.02   918.1   441.1     942  444.76   981.8  446.34  1025.6  453.81
#Mann= 11 ,-1 , 0
       0     .06       0   36.18     .12       0   40.79     .06       0
   70.48     .12       0  217.76     .06       0  302.51    .016       0
  343.22     .12       0   356.6    .045       0   376.5     .12       0
  557.01     .06       0  854.24     .12       0
Bank Sta=356.6,376.5
XS Rating Curve= 0 ,0
Exp/Cntr=0.3,0.1

Type RM Length L Ch R = 1 ,18522.8 ,317.2,312.6,307.3
XS GIS Cut Line= 3
     2379689.072      396436.608     2379592.718      396383.223
     2379356.281      395604.251
#Sta/Elev= 30
       0  471.61  104.54470.1009     170  466.81     178   465.5   233.9  444.05
  242.79437.9009   245.8  436.14   249.8  435.69  274.37436.4145   289.7   433.2
   297.2  432.69   309.7  432.22  314.57  432.87   321.6  436.87   325.6  437.09
   353.6  436.12   373.5  436.83   401.5  434.18   485.3   435.7   493.2  434.85
   505.2  436.35  543.92436.3752   648.9  437.02  723.95435.6194   780.6  436.71
   816.5  453.61   836.4  456.53   864.4  458.14   896.3  457.64   924.2  458.95
#Mann= 8 ,-1 , 0
       0     .08       0  104.54     .12       0  242.79    .016       0
  274.37     .12       0   297.2    .045       0  314.57     .12       0
  543.92     .06       0  723.95     .12       0
Bank Sta=297.2,314.57
XS Rating Curve= 0 ,0
Exp/Cntr=0.3,0.1

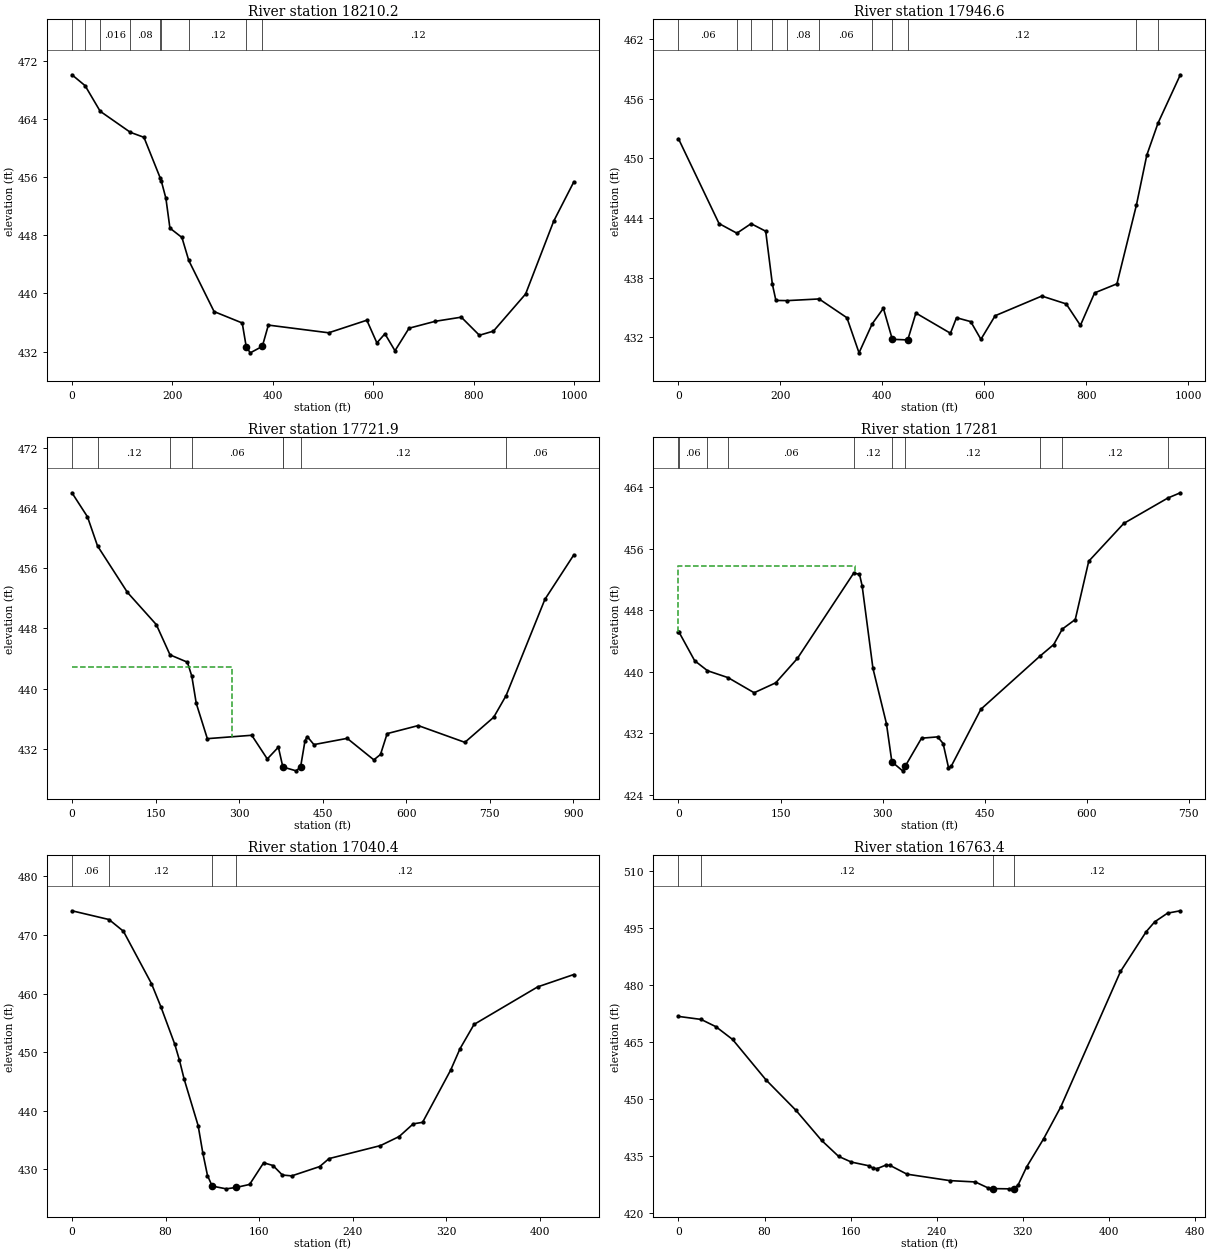
Type RM Length L Ch R = 1 ,18210.2 ,273.4,263.5,254.8
XS GIS Cut Line= 3
     2379879.285      396470.137     2379914.007      396266.144
     2379525.552      395576.039
#Sta/Elev= 30
       0  470.11   26.16468.6131   56.19465.0867  116.25462.1892   143.3   461.5
  175.86455.8737  177.82455.4964     187   453.1     195     449   218.9  447.71
  232.48444.5493   282.9  437.51   338.9  435.94   346.9  432.65   354.9  431.83
   378.9  432.72   390.9  435.65   510.9  434.59   586.9  436.32   606.9   433.2
   622.9  434.45   642.9  432.12   670.9  435.22   722.9  436.17   774.9  436.74
   810.9  434.25   838.9  434.82   902.9  439.93   958.8  449.96   998.8  455.36
#Mann= 9 ,-1 , 0
       0     .08       0   26.16     .06       0   56.19    .016       0
  116.25     .08       0  175.86     .12       0  177.82    .016       0
  232.48     .12       0   346.9    .045       0   378.9     .12       0
Bank Sta=346.9,378.9
XS Rating Curve= 0 ,0
Exp/Cntr=0.3,0.1

Type RM Length L Ch R = 1 ,17946.6 ,229.5,224.8,218.2
XS GIS Cut Line= 4
     2380321.575      396161.241     2379966.148      395919.009
     2379617.542      395640.088     2379584.146      395536.977
#Sta/Elev= 30
       0  451.96    79.6  443.43  114.64442.4608  142.53443.4182   171.2  442.66
  184.29437.3367   191.2   435.7  213.29  435.68  275.93435.8495   330.6  433.96
   354.4  430.43  380.25433.3469   402.2  434.91  419.73  431.79     450  431.73
     466  434.43   533.8   432.4   545.7  433.96   573.6  433.57   593.6  431.79
   621.5  434.16   713.1  436.14     761  435.35   788.9  433.19   816.8  436.46
   860.6  437.37   898.7445.2636   919.2  450.31   941.2453.5292     985  458.39
#Mann= 11 ,-1 , 0
       0     .06       0  114.64     .12       0  142.53    .016       0
  184.29     .06       0  213.29     .08       0  275.93     .06       0
  380.25     .12       0  419.73    .045       0     450     .12       0
   898.7     .06       0   941.2     .12       0
Bank Sta=419.73,450
XS Rating Curve= 0 ,0
Exp/Cntr=0.3,0.1

Type RM Length L Ch R = 1 ,17721.9 ,454.1,440.9,425.4
XS GIS Cut Line= 3
     2380488.212       395904.25     2379755.098      395613.039
     2379696.993      395517.446
#Sta/Elev= 30
       0  466.04    27.9  462.84   45.87458.9757    99.6  452.79   151.4  448.51
  176.04444.4837   207.2  443.51  215.12441.6496   223.1  438.04     243  433.34
   322.7  433.79   350.6  430.64   370.5  432.21  378.34 429.632   378.5  429.57
   402.4  429.06   410.4  429.59   418.3  433.07   422.3  433.62   434.3  432.55
     494  433.38   541.8  430.52   553.8  431.24   565.7  434.01   621.5  435.08
   705.2  432.85     757  436.19  779.22439.0722   848.8  451.86   900.7  457.78
#Mann= 8 ,-1 , 0
       0     .06       0   45.87     .12       0  176.04    .016       0
  215.12     .06       0  378.34     .12       0   378.5    .045       0
   410.4     .12       0  779.22     .06       0
#XS Ineff= 2 , 0
          287.55  442.91
Permanent Ineff=
       F       F
Bank Sta=378.5,410.4
XS Rating Curve= 0 ,0
Exp/Cntr=0.3,0.1

Type RM Length L Ch R = 1 ,17281   ,248.9,240.6,232.1
XS GIS Cut Line= 4
     2380453.286      395461.022      2380205.89      395363.366
      2379970.43      395433.895      2379745.17      395418.921
#Sta/Elev= 30
       0   445.2     .72 445.155    23.8  441.43   42.65440.1336   72.94439.2314
   111.2  437.27   142.9  438.56   174.7  441.72  257.37452.7935     266  452.67
   269.9  451.16   285.8  440.43   305.6  433.27   313.6   428.3   329.4  427.13
   333.4  427.76   357.2  431.37   380.9  431.54   388.9  430.68   396.8  427.56
   400.8  427.72   444.4  435.13   531.3442.0338   551.4  443.53  564.06445.5404
   583.1  446.78   602.9  454.35   654.4  459.26  719.17462.5588   737.5  463.24
#Mann= 10 ,-1 , 0
       0     .08       0     .72     .06       0   42.65     .12       0
   72.94     .06       0  257.37     .12       0   313.6    .045       0
   333.4     .12       0   531.3     .06       0  564.06     .12       0
  719.17     .06       0
#XS Ineff= 2 , 0
          259.82  453.67
Permanent Ineff=
       F       F
Bank Sta=313.6,333.4
XS Rating Curve= 0 ,0
Exp/Cntr=0.3,0.1

Type RM Length L Ch R = 1 ,17040.4 ,262.3,277,291.8
XS GIS Cut Line= 3
      2380113.66       395111.63     2379831.107      395327.776
     2379758.191      395335.588
#Sta/Elev= 30
       0  474.14   31.68472.6464      44  470.65      68  461.71      76  457.78
    87.9  451.37    91.9  448.65    95.9  445.43   107.9  437.47   111.9   432.8
   115.9  428.95   119.9  427.15   131.9  426.68   140.4  426.92   151.9  427.43
   163.9  431.13   171.9  430.66   179.9  429.04   187.9  428.89   211.8  430.48
   219.8  431.84   263.8  434.06   279.8  435.61   291.8  437.77   299.8  438.03
   323.8  446.94   331.8  450.59   343.8  454.74   398.2  461.15   429.1  463.26
#Mann= 4 ,-1 , 0
       0     .06       0   31.68     .12       0   119.9    .045       0
   140.4     .12       0
Bank Sta=119.9,140.4
XS Rating Curve= 0 ,0
Exp/Cntr=0.3,0.1

Type RM Length L Ch R = 1 ,16763.4 ,324,345.4,366.9
XS GIS Cut Line= 3
     2380078.503      395063.453     2380025.118      395007.463
     2379636.229      395013.974
#Sta/Elev= 30
       0  471.82   21.02471.0274    34.8  469.11    50.3  465.75    81.3  455.12
   109.1  447.12   132.9  439.21   148.8  434.98   160.7  433.48   176.6  432.53
   180.6  431.92   184.5  431.74   192.5  432.67   196.4  432.63   212.3   430.3
     252  428.61   275.8  428.25   287.7  426.68   292.2   426.5   307.2  426.44
   311.5  426.52   315.5  427.41   323.4  432.16   339.3  439.62   355.2  447.99
   410.7  483.64   434.6  494.12   442.5  496.71   454.4  498.99   466.3  499.62
#Mann= 4 ,-1 , 0
       0     .06       0   21.02     .12       0   292.2    .045       0
   311.5     .12       0
Bank Sta=292.2,311.5
XS Rating Curve= 0 ,0
Exp/Cntr=0.3,0.1

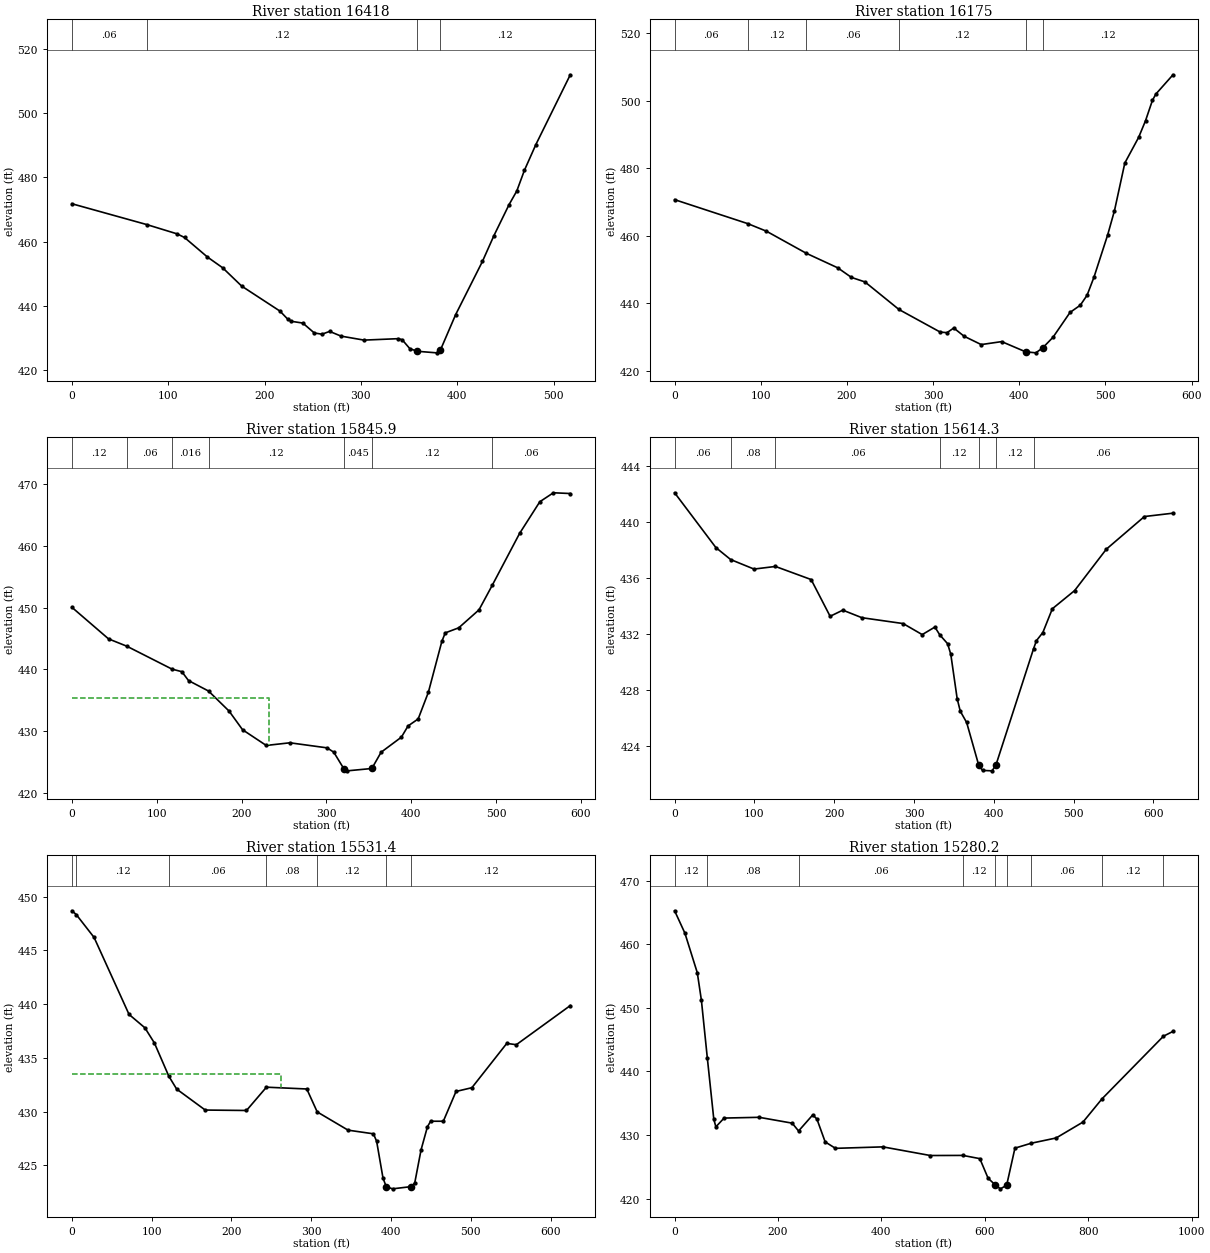
Type RM Length L Ch R = 1 ,16418   ,233.1,243,252.9
XS GIS Cut Line= 3
     2380108.451      395051.734      2380120.17      394931.508
     2379883.856      394613.165
#Sta/Elev= 30
       0  471.83   77.57 465.362   109.1  462.47   116.9  461.33   140.6  455.27
   156.5   451.9   176.3  446.19     216  438.42   223.9  435.96   227.8  435.25
   239.7   434.7   251.6  431.62   259.6  431.24   267.5  432.11   279.4  430.64
   303.2   429.4   338.8  429.85   342.8  429.52   350.8  426.73   358.7  425.92
   378.5  425.44   382.5   426.3   398.3  437.32   426.1  453.87     438  461.88
   453.8  471.58   461.8  475.81   469.7  482.24   481.6  490.26   517.3  511.96
#Mann= 4 ,-1 , 0
       0     .06       0   77.57     .12       0   358.7    .045       0
   382.5     .12       0
Bank Sta=358.7,382.5
XS Rating Curve= 0 ,0
Exp/Cntr=0.3,0.1

Type RM Length L Ch R = 1 ,16175   ,320.6,329.1,337.5
XS GIS Cut Line= 4
     2380164.441      395059.546     2380237.791      394842.793
     2380184.204      394578.443     2380130.384      394519.415
#Sta/Elev= 30
       0  470.69   84.97463.5684   106.5  461.34   152.8454.7867   189.4  450.46
   205.2  447.63   220.9  446.29  260.36 438.118   308.2  431.42   316.1  431.24
     324  432.62   335.9  430.19   355.8  427.71   379.6  428.59   407.3  425.57
   419.2  425.26   427.2  426.74   439.1  429.86   458.9  437.24   470.8  439.38
   478.7  442.34   486.7   447.7   502.6  460.24   510.5  467.44   522.5  481.56
   538.5  489.14   546.5  494.08   554.5  500.11   558.5     502   578.4  507.72
#Mann= 6 ,-1 , 0
       0     .06       0   84.97     .12       0   152.8     .06       0
  260.36     .12       0   407.3    .045       0   427.2     .12       0
Bank Sta=407.3,427.2
XS Rating Curve= 0 ,0
Exp/Cntr=0.3,0.1

Type RM Length L Ch R = 1 ,15845.9 ,230.2,231.5,232.8
XS GIS Cut Line= 4
     2380377.114      394981.655     2380476.941       394912.21
     2380537.083      394558.984     2380456.787      394487.369
#Sta/Elev= 30
       0  450.06    43.2  444.95    64.8443.7613  118.07440.0524   129.6  439.64
   137.5   438.2  161.08436.5068   185.3  433.26   201.2  430.24   229.1   427.7
     257  428.13   300.8  427.31   308.7  426.61   320.7   423.9   324.6  423.59
  353.59  423.97   364.5   426.6   388.4  429.04   396.3  430.86   408.2  431.99
   420.2   436.3   436.1  444.54   440.1  445.92     456  446.74   479.9  449.65
  495.67 453.666   527.7  462.01   551.6  467.15   567.6   468.6   587.5  468.48
#Mann= 7 ,-1 , 0
       0     .12       0    64.8     .06       0  118.07    .016       0
  161.08     .12       0   320.7    .045       0  353.59     .12       0
  495.67     .06       0
#XS Ineff= 2 , 0
          232.61  435.31
Permanent Ineff=
       F       F
Bank Sta=320.7,353.59
XS Rating Curve= 0 ,0
Exp/Cntr=0.3,0.1

Type RM Length L Ch R = 1 ,15614.3 ,83,82.9,82.9
XS GIS Cut Line= 2
     2380657.062      395082.783     2380795.083      394473.625
#Sta/Elev= 30
       0   442.1    51.7  438.18    70.2 437.322    99.5  436.64  126.37436.8277
   171.1  435.89   194.9  433.26   210.8   433.7   234.7  433.16   286.4  432.74
   310.3  431.95   326.2  432.49  332.25431.9365   342.1   431.3   346.1  430.55
   354.1  427.37     358  426.47     366  425.66   381.1  422.61   385.9  422.23
   397.8   422.2   402.6   422.6  449.92430.9509   453.5  431.52   461.5   432.1
   473.4   433.8   501.3   435.1     541  438.06   588.8   440.4   624.6  440.64
#Mann= 7 ,-1 , 0
       0     .06       0    70.2     .08       0  126.37     .06       0
  332.25     .12       0   381.1    .045       0   402.6     .12       0
  449.92     .06       0
Bank Sta=381.1,402.6
XS Rating Curve= 0 ,0
Exp/Cntr=0.3,0.1

Type RM Length L Ch R = 1 ,15531.4 ,252.2,251.2,250
XS GIS Cut Line= 2
     2380735.187      395105.353     2380873.208      394496.195
#Sta/Elev= 30
       0  448.68    5.47448.3281    27.8   446.2    71.6  439.04    91.5  437.79
   103.4  436.38  121.51433.2841   131.3  432.09   167.1  430.14   218.8   430.1
   243.8432.2678   294.4   432.1  307.44 429.966   346.1  428.27   377.9  427.93
   381.9  427.24   389.9  423.81   393.9  423.02   401.8  422.81   425.6  423.02
   429.7  423.37   437.6  426.44   445.6  428.59   449.6   429.1   465.5   429.1
   481.4  431.87   501.3  432.22     545  436.34     557  436.22   624.6  439.86
#Mann= 7 ,-1 , 0
       0     .06       0    5.47     .12       0  121.51     .06       0
   243.8     .08       0  307.44     .12       0   393.9    .045       0
   425.6     .12       0
#XS Ineff= 2 , 0
          261.49  433.47
Permanent Ineff=
       F       F
Bank Sta=393.9,425.6
XS Rating Curve= 0 ,0
Exp/Cntr=0.3,0.1

Type RM Length L Ch R = 1 ,15280.2 ,368,365.6,362.3
XS GIS Cut Line= 3
     2380966.958      395291.334     2381104.111      394513.556
     2381076.333      394341.681
#Sta/Elev= 30
       0  465.27    19.9  461.75    43.9  455.52    51.8   451.2   63.19442.1797
    75.8  432.48    79.8  431.29    95.7  432.67   163.5  432.79   227.4  431.87
  239.74 430.638   267.2  433.17   275.2  432.52   291.2  428.92   311.1  427.91
   402.9  428.14   494.6  426.78  557.49426.7968   590.3  426.29   606.3  423.21
     620  422.17   630.2  421.54   642.2  422.11   658.2  427.94  689.29428.7037
   737.9  429.54   789.8  432.04  826.45435.6786  945.43 445.543   963.9   446.3
#Mann= 9 ,-1 , 0
       0     .12       0   63.19     .08       0  239.74     .06       0
  557.49     .12       0     620    .045       0   642.2     .12       0
  689.29     .06       0  826.45     .12       0  945.43     .06       0
Bank Sta=620,642.2
XS Rating Curve= 0 ,0
Exp/Cntr=0.3,0.1

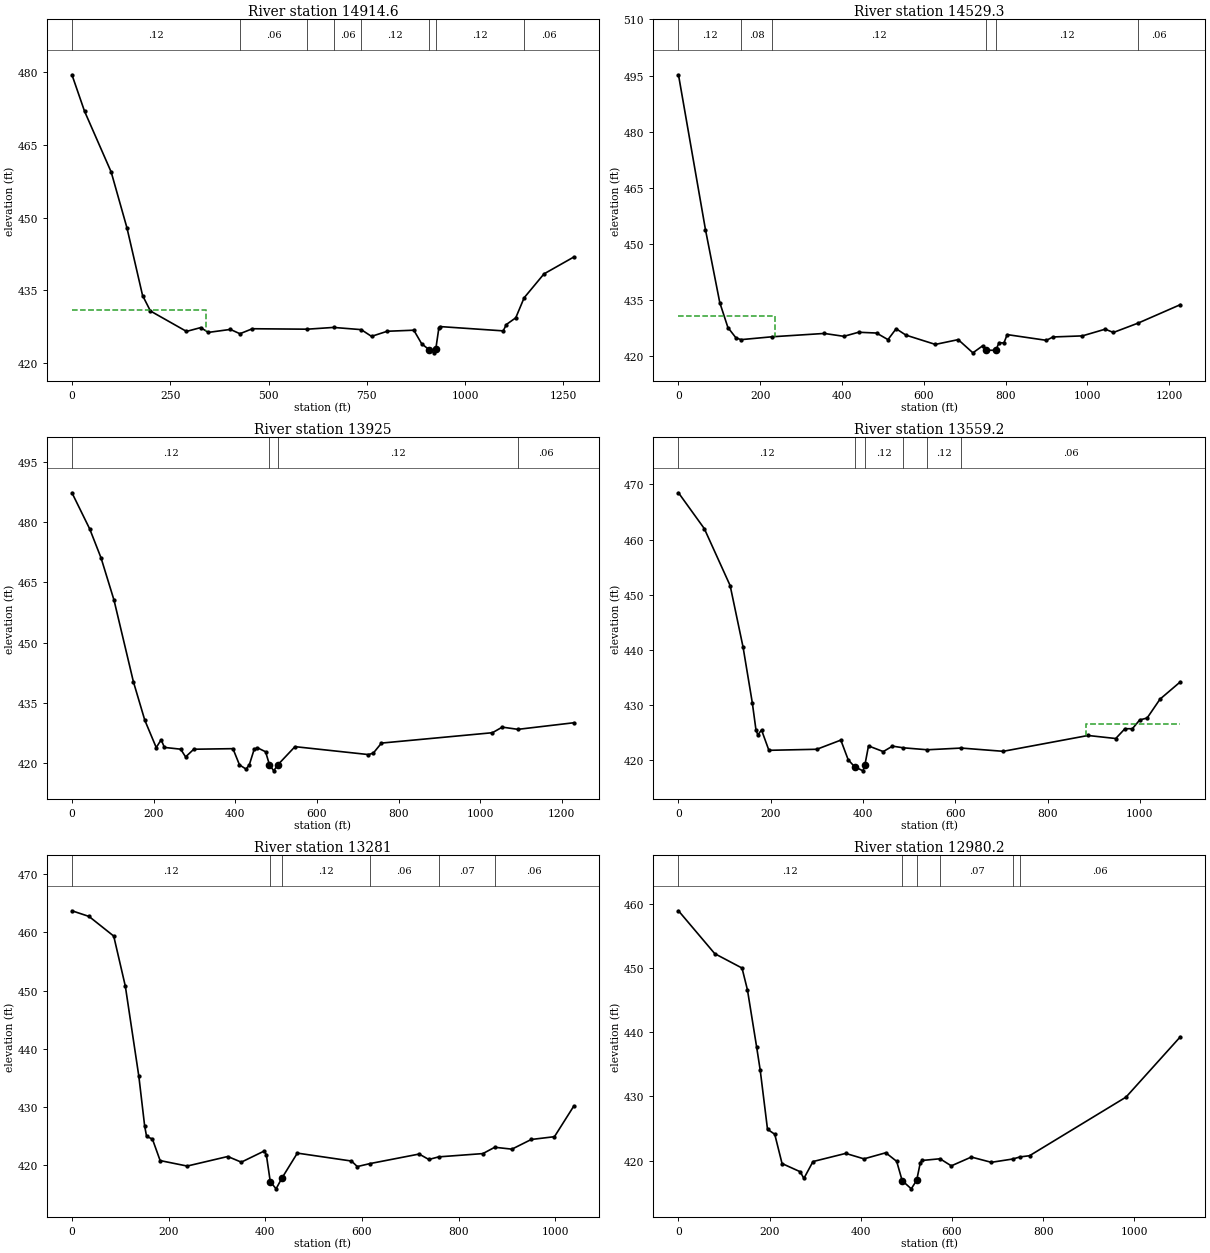
Type RM Length L Ch R = 1 ,14914.6 ,387.9,385.2,382.6
XS GIS Cut Line= 3
     2381462.828      395576.146     2381402.064      395450.278
     2381458.487      394315.295
#Sta/Elev= 30
       0  479.38      32  471.88    99.8  459.36   139.8   447.9   179.6  433.95
   199.6  430.76   291.3  426.56   327.2  427.34   347.1  426.36   402.9  426.97
  427.17426.0826   458.8  427.11  598.55427.0181  665.21427.3811  735.65426.9244
   761.8  425.54   801.7  426.59   869.4  426.81   889.4  424.01   908.4  422.79
   921.3  422.15   925.3  422.97   933.2  427.34   937.2  427.55  1096.7  426.67
  1104.7  427.98  1128.6  429.36 1149.88433.4776  1200.4   438.4  1276.2  441.87
#Mann= 8 ,-1 , 0
       0     .12       0  427.17     .06       0  598.55     .12       0
  665.21     .06       0  735.65     .12       0   908.4    .045       0
   925.3     .12       0 1149.88     .06       0
#XS Ineff= 2 , 0
          341.46  430.94
Permanent Ineff=
       F       F
Bank Sta=908.4,925.3
XS Rating Curve= 0 ,0
Exp/Cntr=0.3,0.1

Type RM Length L Ch R = 1 ,14529.3 ,602.3,604.4,606.2
XS GIS Cut Line= 3
     2381872.984      395565.295     2381829.581      395469.809
     2381774.539      394348.719
#Sta/Elev= 30
       0  495.21      66  453.84     101  434.35   120.9  427.69   140.8   424.9
  153.29424.4576  227.96425.2115   356.5  426.11   404.5  425.34   440.4  426.43
   484.4  426.22   512.3  424.46   532.3  427.37   556.3  425.66   628.2  423.18
   684.1  424.46     720  420.93     744  422.82     752  421.63     776  421.61
   783.9  423.64   795.9  423.57   803.9   425.8   899.8  424.27   915.8  425.17
   987.7  425.46  1043.6  427.25  1063.6  426.37 1124.26428.8818  1227.3   433.8
#Mann= 6 ,-1 , 0
       0     .12       0  153.29     .08       0  227.96     .12       0
     752    .045       0     776     .12       0 1124.26     .06       0
#XS Ineff= 2 , 0
          235.43  430.71
Permanent Ineff=
       F       F
Bank Sta=752,776
XS Rating Curve= 0 ,0
Exp/Cntr=0.3,0.1

Type RM Length L Ch R = 1 ,13925   ,366.9,365.8,364.5
XS GIS Cut Line= 4
     2382344.338      395454.184     2382281.404      395317.466
     2382313.088      394410.492     2382365.171      394247.298
#Sta/Elev= 30
       0  487.28    43.6  478.26    71.3  471.06     103  460.57   150.5  440.25
   178.5  430.65   206.5  423.85   218.5   425.8   226.5  423.89   266.4  423.45
   278.4  421.52   298.4  423.44   394.4  423.58   410.4  419.54   426.4   418.5
   434.4  419.54   446.4  423.43   454.4   423.8   474.3  422.81   483.8  419.58
   494.3  418.06   504.3  419.56   546.3  424.08   726.2  422.11   738.2  422.47
   758.2  424.97    1030  427.55    1054  428.94 1092.51428.3904  1229.3  430.03
#Mann= 4 ,-1 , 0
       0     .12       0   483.8    .045       0   504.3     .12       0
 1092.51     .06       0
Bank Sta=483.8,504.3
XS Rating Curve= 0 ,0
Exp/Cntr=0.3,0.1

Type RM Length L Ch R = 1 ,13559.2 ,281.5,278.2,274.9
XS GIS Cut Line= 2
     2382665.569      395373.075     2382646.421      394285.492
#Sta/Elev= 30
       0  468.48      56  461.98     112  451.65     140   440.5     160  430.43
     168  425.48     172  424.58     180  425.48     196  421.79   299.9  421.98
   351.9  423.64   367.9  420.07   381.7  418.82   399.9  418.07   403.9  419.06
   411.9  422.59   443.9  421.56   463.9  422.55  487.16422.2459  539.52421.8896
  612.94422.1996   703.8  421.61   887.8  424.48   947.8  423.93   967.8  425.71
   983.8   425.7   999.8   427.3  1015.8  427.64  1043.8  431.07  1087.8   434.2
#Mann= 6 ,-1 , 0
       0     .12       0   381.7    .045       0   403.9     .12       0
  487.16     .06       0  539.52     .12       0  612.94     .06       0
#XS Ineff= 2 , 0
                          884.21          426.61
Permanent Ineff=
       F       F
Bank Sta=381.7,403.9
XS Rating Curve= 0 ,0
Exp/Cntr=0.3,0.1

Type RM Length L Ch R = 1 ,13281   ,292,300.8,309.6
XS GIS Cut Line= 3
     2382928.829      395343.652     2382987.423      395291.569
     2382830.934      394344.864
#Sta/Elev= 30
       0  463.69    35.3  462.72    86.4  459.35   110.4  450.76   138.4  435.26
   150.4  426.74   154.4  424.96   166.4  424.52   182.4  420.82   238.3  419.88
   322.3  421.52   350.3  420.55   398.2  422.48   402.2  421.75   410.2  417.21
   422.2  415.97   434.2   417.8   466.2   422.1   578.2  420.74   590.2  419.79
  616.31 420.301   718.1  421.94   738.1  421.01  758.57421.4559     850  422.02
  874.47423.1053     910  422.78     950  424.44     998  424.92    1038  430.17
#Mann= 6 ,-1 , 0
       0     .12       0   410.2    .045       0   434.2     .12       0
  616.31     .06       0  758.57     .07       0  874.47     .06       0
Bank Sta=410.2,434.2
XS Rating Curve= 0 ,0
Exp/Cntr=0.3,0.1

Type RM Length L Ch R = 1 ,12980.2 ,216.5,223.9,231
XS GIS Cut Line= 4
     2383000.349      395286.487     2383121.877      395236.574
     2383296.595      394396.169     2383300.067      394285.058
#Sta/Elev= 30
       0   458.9    79.6  452.22   139.4  449.98   151.3  446.58   171.3  437.75
   179.3  434.08   195.3  424.87   211.2  424.09   227.2  419.53   267.1  418.25
   275.1  417.21   295.1  419.84   366.9  421.11   406.9  420.26   454.8  421.21
   478.7  419.87   490.7  416.87   510.7  415.59   522.6  416.94   530.6  419.69
   534.6  420.01  573.75420.2746   598.5  419.17   642.4  420.54   686.3  419.72
  733.85420.2421  749.01420.5583   770.2  420.75   981.8  429.88  1100.9  439.27
#Mann= 6 ,-1 , 0
       0     .12       0   490.7    .045       0   522.6     .12       0
  573.75     .07       0  733.85     .12       0  749.01     .06       0
Bank Sta=490.7,522.6
XS Rating Curve= 0 ,0
Exp/Cntr=0.3,0.1