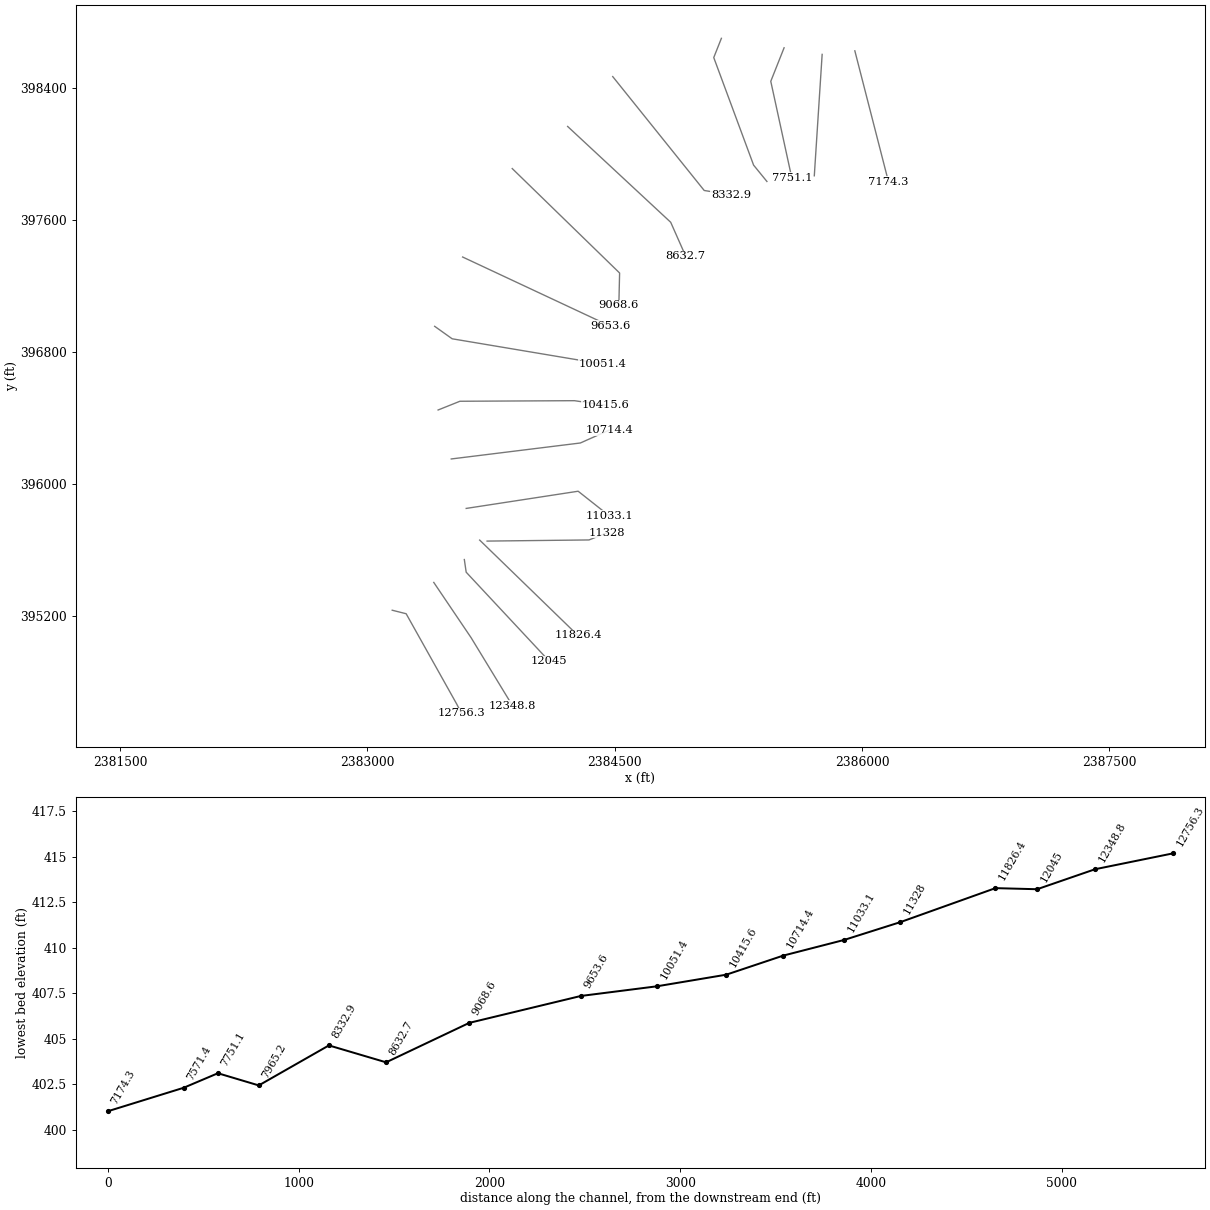
HEC-RAS study TILHANCECK.prj: TILHANCECK

--- TILHANCECK.g01 (geometry) --- (continued)

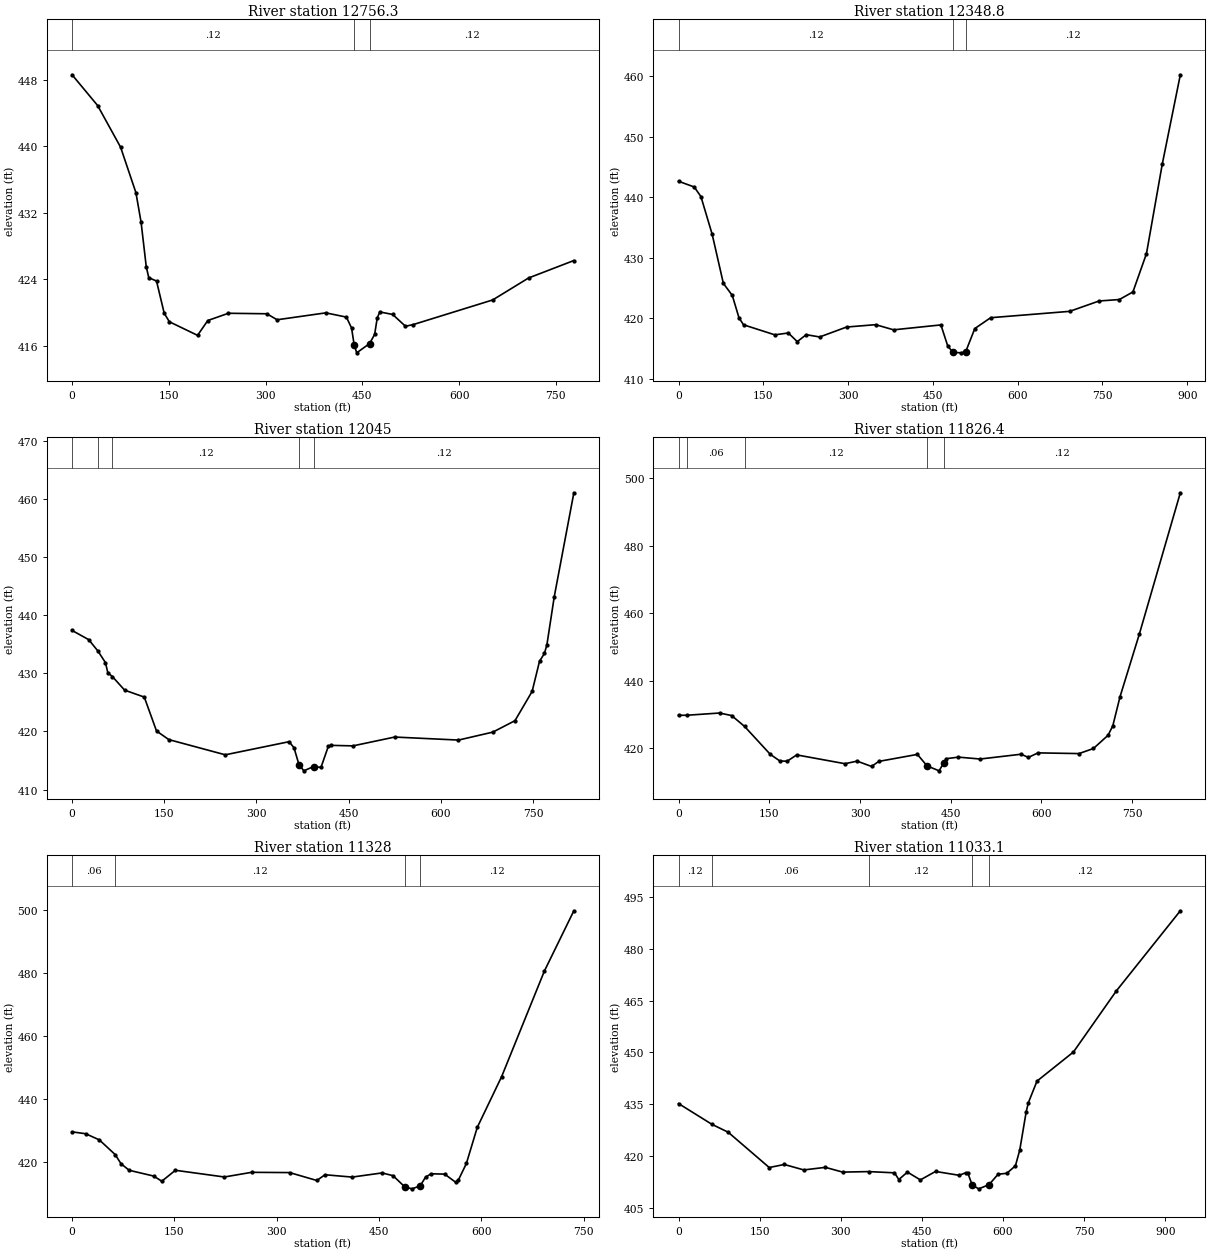
Type RM Length L Ch R = 1 ,12756.3 ,406.7,407.5,408.3
XS GIS Cut Line= 4
     2383151.174      395235.489      2383235.63      395214.164
     2383542.884      394665.827     2383571.096      394610.489
#Sta/Elev= 30
       0  448.57    39.6  444.88    75.2  439.88      99  434.41     107  430.86
     115  425.52   118.9  424.21   130.9  423.81   142.8  419.95   150.8  418.92
   194.5  417.29   210.4  419.07   242.3  419.94   301.9  419.88   317.8  419.16
   393.4  419.99   425.2  419.48   433.2  418.18   437.2  416.18   441.2  415.19
   461.1   416.3     469   417.4     473  419.37     477   420.1   496.9   419.8
   516.8  418.38   528.7  418.58     652  421.54   707.7  424.18   777.8  426.27
#Mann= 3 ,-1 , 0
       0     .12       0   437.2    .045       0   461.1     .12       0
Bank Sta=437.2,461.1
XS Rating Curve= 0 ,0
Exp/Cntr=0.3,0.1

Type RM Length L Ch R = 1 ,12348.8 ,298.3,303.8,309.3
XS GIS Cut Line= 3
     2383403.149      395403.868     2383629.571      395068.925
     2383881.125      394656.002
#Sta/Elev= 30
       0  442.65    27.8   441.7    39.6  440.12    59.5   433.9    79.3  425.79
    95.1   423.8     107  420.09     115  418.95   170.4  417.29   194.2   417.6
   210.1  416.17   225.9  417.32   249.7  416.94   297.3  418.58   348.8  418.97
   380.5  418.12   464.2  418.93   476.2  415.48   485.2  414.41   500.2  414.32
   508.2  414.54   524.2  418.33   552.2  420.12     692  421.17     744  422.88
   779.9  423.12   803.9  424.37   827.9   430.7   855.8  445.46   887.8  460.23
#Mann= 3 ,-1 , 0
       0     .12       0   485.2    .045       0   508.2     .12       0
Bank Sta=485.2,508.2
XS Rating Curve= 0 ,0
Exp/Cntr=0.3,0.1

Type RM Length L Ch R = 1 ,12045   ,216.9,218.5,219.9
XS GIS Cut Line= 3
     2383588.457      395542.563     2383599.636       395465.83
     2384104.096      394925.951
#Sta/Elev= 30
       0   437.4    27.1  435.81    42.1433.8492    54.3  431.86    58.2  430.11
   65.72429.4409    85.5  427.12   117.5  425.92   137.4  420.08   157.4   418.6
   249.3  415.98   353.1  418.24   361.1  417.19   369.1  414.31   377.1  413.22
   392.9  413.96     405  413.81     417  417.47     421  417.61     457  417.52
   524.9  419.04   628.7  418.52   684.6  419.89   720.6  421.86   748.5   426.9
   760.5  432.08   768.5  433.44   772.5   434.9   784.5  443.21   816.4  461.11
#Mann= 5 ,-1 , 0
       0     .12       0    42.1    .016       0   65.72     .12       0
   369.1    .045       0   392.9     .12       0
Bank Sta=369.1,392.9
XS Rating Curve= 0 ,0
Exp/Cntr=0.3,0.1

Type RM Length L Ch R = 1 ,11826.4 ,478.3,498.5,518.2
XS GIS Cut Line= 2
     2383681.409      395660.454     2384276.933      395082.863
#Sta/Elev= 30
       0  429.73   13.24429.7362    67.8   430.4    87.8  429.65  109.19 426.429
   151.6  418.18   167.5   416.2   179.5  416.13   195.4     418   275.2  415.39
   295.2  416.16   319.1  414.58     331  416.07   394.9  418.15   410.8  414.76
   430.8  413.28   438.7  415.72   442.7  416.88   462.7  417.34   498.6  416.78
   566.4   418.2   578.3  417.25   594.3   418.6   662.1  418.39     686   419.9
     710  423.79   717.9  426.57   729.9  435.22   761.8  453.75   829.6  495.62
#Mann= 5 ,-1 , 0
       0    .016       0   13.24     .06       0  109.19     .12       0
   410.8    .045       0   438.7     .12       0
Bank Sta=410.8,438.7
XS Rating Curve= 0 ,0
Exp/Cntr=0.3,0.1

Type RM Length L Ch R = 1 ,11328   ,291.2,294.8,298.2
XS GIS Cut Line= 3
     2383726.478      395654.398     2384344.533      395661.342
     2384453.908      395704.745
#Sta/Elev= 30
       0  429.49    19.9   428.9    39.9  426.96   63.19 422.286    71.8  419.38
    83.7   417.3   119.6  415.47   131.6  413.83   151.5   417.3   223.3  415.17
   263.2  416.65     319  416.57   358.9  414.06   370.9  415.88   410.7  415.14
   454.6  416.46   470.6  415.59     488  412.01   498.5  411.41   510.4  412.36
   518.4  415.14   526.4  416.18   546.3  416.09   562.3  413.52   566.2  414.08
   578.2  419.46   594.2  430.93   629.9  447.03   692.6  480.54   735.8  499.66
#Mann= 4 ,-1 , 0
       0     .06       0   63.19     .12       0     488    .045       0
   510.4     .12       0
Bank Sta=488,510.4
XS Rating Curve= 0 ,0
Exp/Cntr=0.3,0.1

Type RM Length L Ch R = 1 ,11033.1 ,318.8,318.8,318.4
XS GIS Cut Line= 3
     2383599.742      395852.314     2384278.561      395956.481
     2384467.797      395807.176
#Sta/Elev= 30
       0  435.15   61.87429.1172    91.8  426.84   167.7  416.61   195.6  417.49
   231.6  415.91   271.5  416.66   303.4  415.28   351.8 415.427   399.3  415.07
   407.3  413.12   423.2  415.28   447.2  413.02   475.2  415.47   519.1  414.35
     531   415.1     535  414.94     543  411.54     555  410.43  574.01  411.63
   590.9  414.67   606.9  414.93   622.9   417.1   630.9  421.67   642.8  432.75
   646.8  435.39   662.8  441.66   730.2   450.1   809.3  467.76   927.8  491.03
#Mann= 5 ,-1 , 0
       0     .12       0   61.87     .06       0   351.8     .12       0
     543    .045       0  574.01     .12       0
Bank Sta=543,574.01
XS Rating Curve= 0 ,0
Exp/Cntr=0.3,0.1

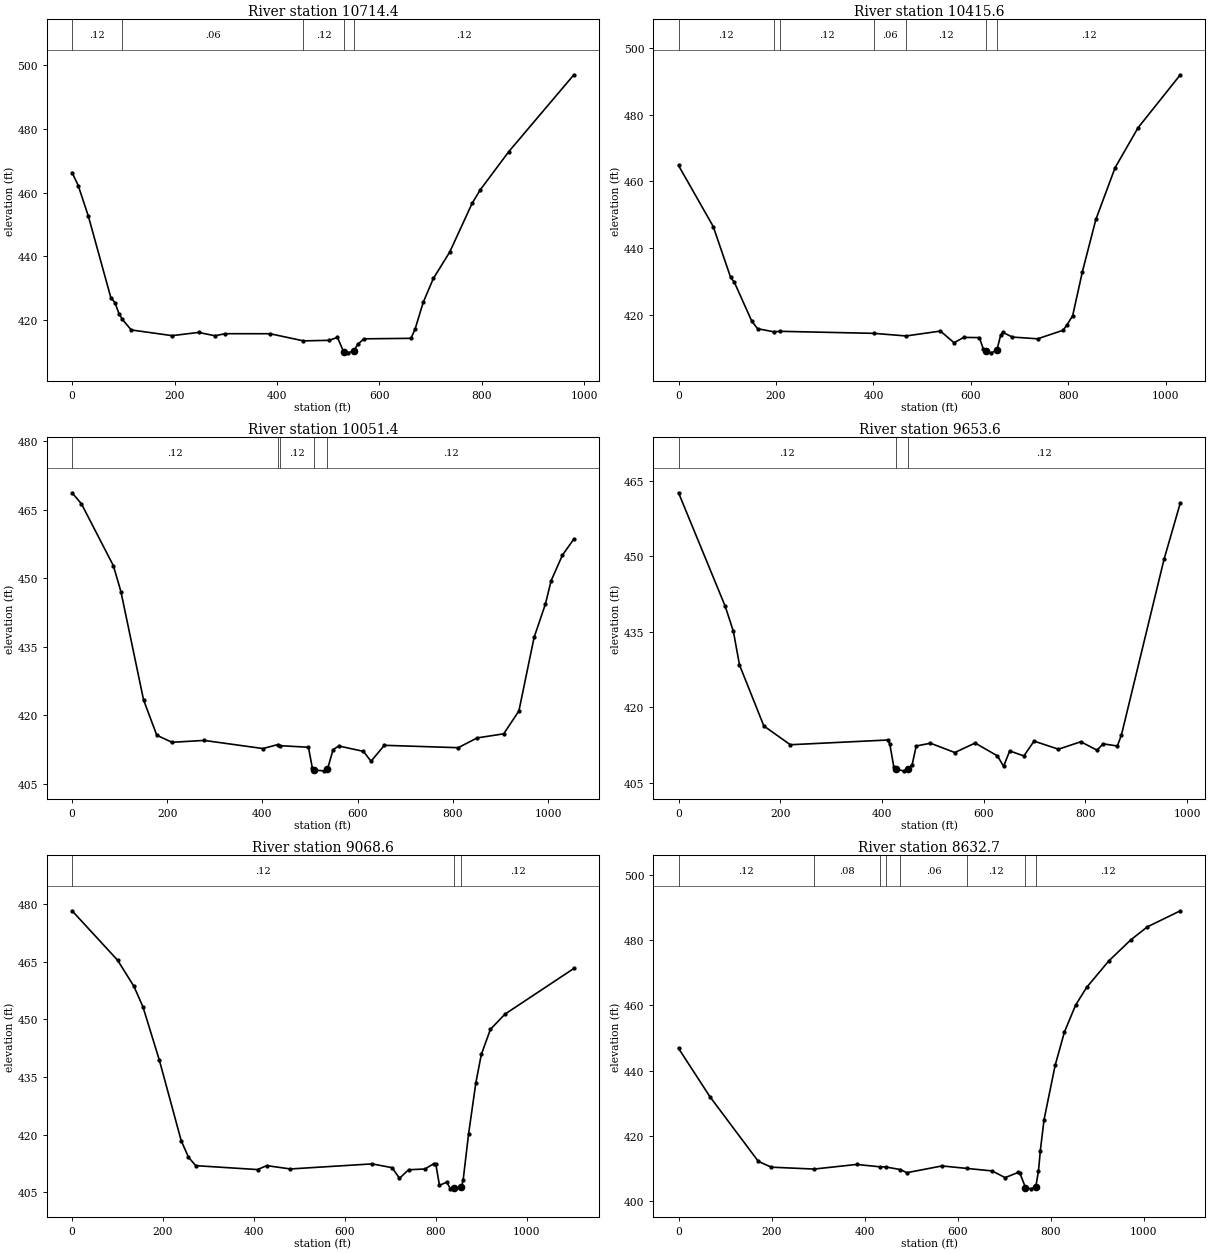
Type RM Length L Ch R = 1 ,10714.4 ,301.8,298.8,295.6
XS GIS Cut Line= 3
     2383509.089      396152.002     2384292.019      396248.788
     2384466.061      396326.273
#Sta/Elev= 30
       0  466.29      12  462.19    31.9  452.49    75.7  426.91    83.7  425.38
    91.6  421.87   98.26420.0714   115.5  416.77   195.2  414.98     247  415.99
   278.9  414.94   298.8  415.59   386.5  415.58  451.66413.3336     502  413.51
     518  414.45   529.9  409.92   537.9  409.57   549.8  410.17   557.8  412.29
   569.8  413.98   661.4  414.13   669.4  416.98   685.3  425.42   705.2  432.98
   737.1  441.27   780.9  456.62   796.8  460.86   852.4  472.86   979.4  497.03
#Mann= 5 ,-1 , 0
       0     .12       0   98.26     .06       0  451.66     .12       0
   529.9    .045       0   549.8     .12       0
Bank Sta=529.9,549.8
XS Rating Curve= 0 ,0
Exp/Cntr=0.3,0.1

Type RM Length L Ch R = 1 ,10415.6 ,368,364.2,360.4
XS GIS Cut Line= 4
     2383429.408      396448.687     2383561.547       396501.62
     2384255.992      396505.092     2384446.964      396477.314
#Sta/Elev= 30
       0  464.71    71.2  446.41   106.8  431.19   114.7  429.64   150.3  418.01
   162.3  415.76  195.16414.8404  209.17 414.974  400.91414.3645  467.03413.5844
   537.5  415.05   565.4  411.55   585.4  413.15   617.3  413.09   625.3  409.78
   630.6  409.07   641.2  408.52   653.2  409.26   661.2  413.88   665.2  414.68
   685.1  413.25     737  412.73   788.9  415.28   796.9  416.81   808.9  419.69
   828.8  432.85   856.5  448.54   895.9  464.04   943.1  476.04  1029.8  491.92
#Mann= 7 ,-1 , 0
       0     .12       0  195.16     .06       0  209.17     .12       0
  400.91     .06       0  467.03     .12       0   630.6    .045       0
   653.2     .12       0
Bank Sta=630.6,653.2
XS Rating Curve= 0 ,0
Exp/Cntr=0.3,0.1

Type RM Length L Ch R = 1 ,10051.4 ,402.9,397.8,392.7
XS GIS Cut Line= 3
     2383408.574      396955.631     2383514.672      396880.092
     2384426.131      396727.314
#Sta/Elev= 30
       0  468.66    19.7  466.24    86.8  452.72   102.6  447.08   150.2   423.4
     178  415.66   209.9  414.12   277.6  414.53   401.1  412.75  432.84413.6368
  437.63413.3737   496.7  413.04   504.7  408.58   508.7  408.05   528.6  407.88
   536.6   408.2   548.5  412.52   560.5  413.31   612.2  412.14   628.2  409.97
   656.1  413.46   811.4  412.94   851.3  415.08     907  415.97   938.9  420.96
   970.8  437.03   994.7  444.36  1006.6  449.43  1030.5  455.05  1054.4  458.55
#Mann= 5 ,-1 , 0
       0     .12       0  432.84     .06       0  437.63     .12       0
   508.7    .045       0   536.6     .12       0
Bank Sta=508.7,536.6
XS Rating Curve= 0 ,0
Exp/Cntr=0.3,0.1

Type RM Length L Ch R = 1 ,9653.6  ,593.2,585,576.5
XS GIS Cut Line= 2
     2383578.124      397375.608     2384472.005      396957.408
#Sta/Elev= 30
       0  462.63    91.9  440.04   107.9  435.06   119.9   428.4   167.8  416.27
   219.8  412.54   411.5  413.48   415.5  412.68   423.5  408.06   427.5  407.63
   443.5  407.35   451.5  407.71   459.5  408.59   467.5  412.29   495.4  412.84
   543.4  410.99   583.3  412.88   627.3  410.32   639.3  408.24   651.3  411.31
   679.2  410.31   699.2  413.26   747.2  411.65   791.1  413.13   823.1  411.46
     835  412.72     863  412.29     871  414.45   954.9  449.41   986.9  460.62
#Mann= 3 ,-1 , 0
       0     .12       0   427.5    .045       0   451.5     .12       0
Bank Sta=427.5,451.5
XS Rating Curve= 0 ,0
Exp/Cntr=0.3,0.1

Type RM Length L Ch R = 1 ,9068.6  ,435.3,435.9,436.5
XS GIS Cut Line= 3
     2383878.908      397911.516      2384529.95      397278.703
     2384525.328      397083.235
#Sta/Elev= 30
       0  478.32     100  465.46     136  458.64     156  453.24     192  439.37
     240   418.4     256   414.1     272  411.91     408  410.89     428  411.92
     480  411.05   659.9  412.37   703.9  411.38   719.9  408.61   739.9  410.84
   775.9  411.04   795.9  412.45   799.9  412.24   807.9  406.78   823.9  407.62
   831.9  405.87   839.9  406.06   856.1  406.36   859.9   408.1   871.9  420.19
   887.9   433.5   899.9  440.88   919.9  447.42   951.8  451.38  1103.4  463.29
#Mann= 3 ,-1 , 0
       0     .12       0   839.9    .045       0   856.1     .12       0
Bank Sta=839.9,856.1
XS Rating Curve= 0 ,0
Exp/Cntr=0.3,0.1

Type RM Length L Ch R = 1 ,8632.7  ,302.9,299.8,296.7
XS GIS Cut Line= 3
     2384214.846      398166.724     2384839.846      397585.995
     2384930.992      397380.266
#Sta/Elev= 30
       0  446.83    67.8  431.91   171.4  412.14   199.3  410.35  291.25409.7706
   382.7  411.19  432.67410.4625  445.57410.4093  476.83409.6117   490.4  408.65
   566.1  410.73  620.46409.9544   673.8   409.2   701.7  407.15   729.6  408.72
   733.6  408.45   745.5  404.09   757.5   403.7  767.71   404.4   773.4  409.11
   777.4  415.44   785.4  424.96   809.3  441.65   829.2  451.86   853.2  460.09
   876.8  465.52   924.2  473.62   971.6  480.11  1007.1   484.1  1078.2  489.06
#Mann= 8 ,-1 , 0
       0     .12       0  291.25     .08       0  432.67     .06       0
  445.57     .12       0  476.83     .06       0  620.46     .12       0
   745.5    .045       0  767.71     .12       0
Bank Sta=745.5,767.71
XS Rating Curve= 0 ,0
Exp/Cntr=0.3,0.1

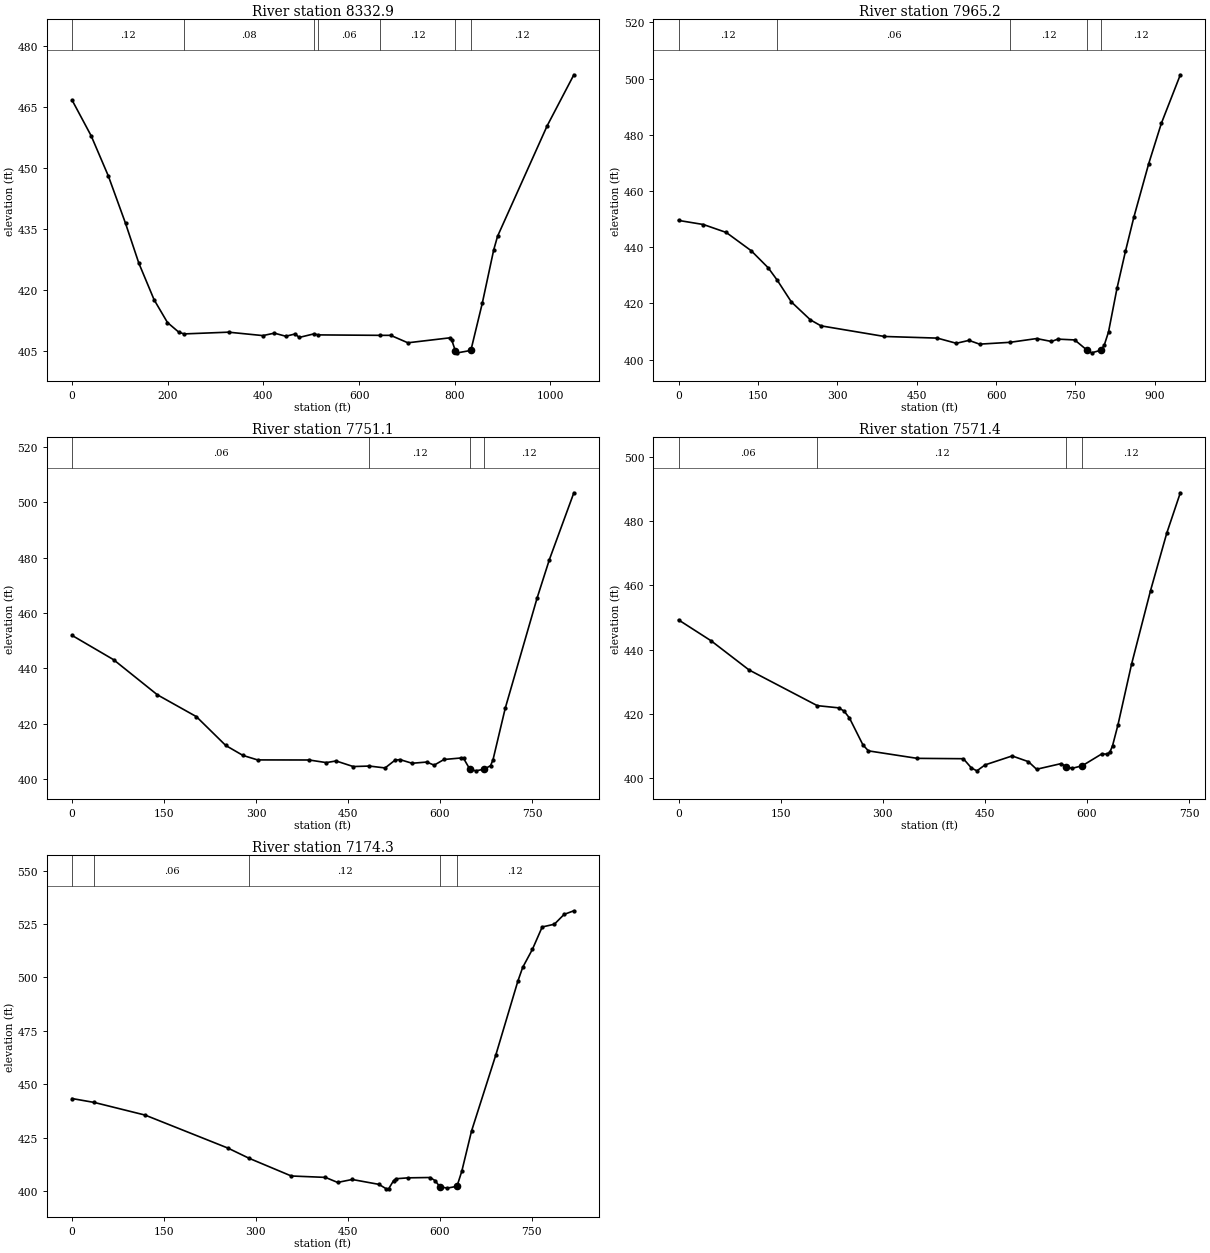
Type RM Length L Ch R = 1 ,8332.9  ,375.3,367.6,359.5
XS GIS Cut Line= 3
     2384488.283      398468.807     2385042.971      397778.703
     2385204.429      397752.662
#Sta/Elev= 30
       0  466.75    39.9  457.98    75.8  448.11   111.7  436.48   139.6  426.66
   171.5  417.67   199.4  412.08   223.3  409.69  234.15409.2819     327  409.71
   398.8  408.87   422.8  409.47   446.7  408.71   466.6  409.28   474.6  408.41
  506.18409.3088  514.06409.0398  643.77408.9317     666  408.93   701.9   407.1
   789.7  408.32   793.7  407.76  801.06  405.17   805.6  404.63   833.6  405.22
   857.5  416.84   881.4  429.96   889.4  433.28   993.1  460.44  1048.9  472.98
#Mann= 7 ,-1 , 0
       0     .12       0  234.15     .08       0  506.18     .12       0
  514.06     .06       0  643.77     .12       0  801.06    .045       0
   833.6     .12       0
Bank Sta=801.06,833.6
XS Rating Curve= 0 ,0
Exp/Cntr=0.3,0.1

Type RM Length L Ch R = 1 ,7965.2  ,217.5,214.2,211.1
XS GIS Cut Line= 4
     2385147.138      398700.578     2385100.848      398584.103
      2385342.45      397932.349     2385423.179      397833.391
#Sta/Elev= 30
       0  449.53      47  448.07    90.1  445.25   137.3  438.75   169.3   432.7
  186.43428.2918   213.2  420.53   249.2  414.15   269.2  412.03     389  408.25
   488.9  407.67   524.8  405.83   548.8  406.86   568.8  405.52   626.5 406.175
   676.6  407.51   704.6  406.47   716.6  407.31   748.5  407.02   772.5  403.28
   780.5  402.43     798  403.36   804.4  405.19   812.4  409.85   828.4  425.34
   844.4  438.53   860.3  450.68   888.3  469.68   912.2  484.03   948.1  501.33
#Mann= 5 ,-1 , 0
       0     .12       0  186.43     .06       0   626.5     .12       0
   772.5    .045       0     798     .12       0
Bank Sta=772.5,798
XS Rating Curve= 0 ,0
Exp/Cntr=0.3,0.1

Type RM Length L Ch R = 1 ,7751.1  ,186,179.7,173.4
XS GIS Cut Line= 3
     2385527.346      398643.287     2385446.617      398440.162
     2385574.221      397854.224
#Sta/Elev= 30
       0  451.92    67.6  443.18   139.1  430.51   202.7  422.64   250.6  412.24
   278.6  408.66   302.5  407.04   386.5  407.01   414.5  406.07   430.5  406.66
   458.4  404.65  484.85404.8229   510.4  404.14   526.4  406.91   534.4  407.17
   554.4  405.83   578.4  406.27   590.4  405.14   606.4  407.19   634.4  407.74
   638.4  407.58   648.5  403.73   658.3   403.1   671.9  403.69   682.3  404.96
   686.3  407.03   706.3  425.66   758.3  465.42   778.3  479.26   818.2  503.34
#Mann= 4 ,-1 , 0
       0     .06       0  484.85     .12       0   648.5    .045       0
   671.9     .12       0
Bank Sta=648.5,671.9
XS Rating Curve= 0 ,0
Exp/Cntr=0.3,0.1

Type RM Length L Ch R = 1 ,7571.4  ,389.9,397.1,404.3
XS GIS Cut Line= 2
     2385758.122      398603.417     2385710.532      397867.623
#Sta/Elev= 30
       0  449.22    47.8  442.73   103.6  433.66  203.87422.5645   235.2  421.88
   243.1   420.9   251.1  418.74     271  410.34     279  408.51   350.7  406.18
   418.5  406.07   430.4  403.18   438.4   402.3   450.4  404.15   490.2  406.93
   514.1  405.15   526.1  402.79     562  404.54   569.9  403.64   577.9  403.06
   593.2  403.88   621.8  407.55   629.7   407.5   633.7  408.07   637.7  410.09
   645.7  416.62   665.6  435.41   693.5   458.3   717.4  476.21   737.3  488.73
#Mann= 4 ,-1 , 0
       0     .06       0  203.87     .12       0   569.9    .045       0
   593.2     .12       0
Bank Sta=569.9,593.2
XS Rating Curve= 0 ,0
Exp/Cntr=0.3,0.1

Type RM Length L Ch R = 1 ,7174.3  ,341.3,342,342.7
XS GIS Cut Line= 3
     2385956.322      398624.967     2386058.305       398228.37
     2386160.288      397831.772
#Sta/Elev= 30
       0  443.29   36.56441.4449   119.3  435.54   254.4  420.09  289.17415.2868
   357.8  407.03   413.5  406.37   433.4  404.01   457.2  405.39   500.9   403.1
   512.9  401.01   516.8  401.07   524.8  404.88   528.8  405.74   548.6  406.16
   584.4  406.32   592.4  404.88   600.3     402   612.3  401.35   628.2  402.19
   636.1  409.26     652  428.08   691.8  463.87   727.6  498.27   735.5  504.72
   751.4   513.2   767.3  523.63   787.2  524.93   803.1  529.53     819  531.22
#Mann= 5 ,-1 , 0
       0     .08       0   36.56     .06       0  289.17     .12       0
   600.3    .045       0   628.2     .12       0
Bank Sta=600.3,628.2
XS Rating Curve= 0 ,0
Exp/Cntr=0.3,0.1