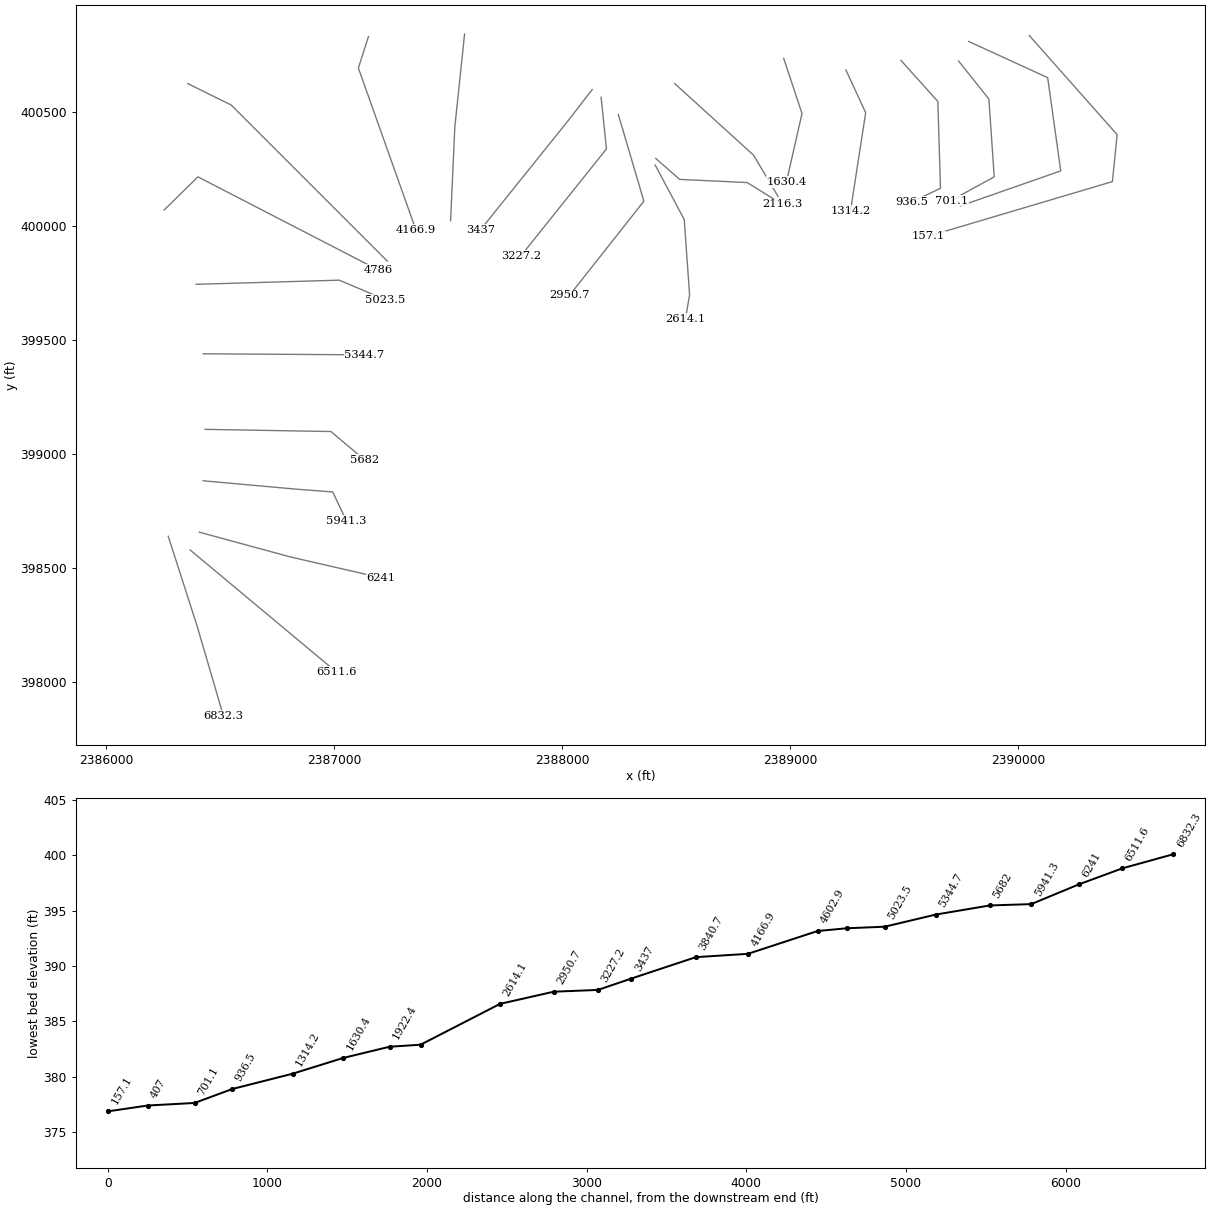
HEC-RAS study TILHANCECK.prj: TILHANCECK

--- TILHANCECK.g01 (geometry) --- (continued)

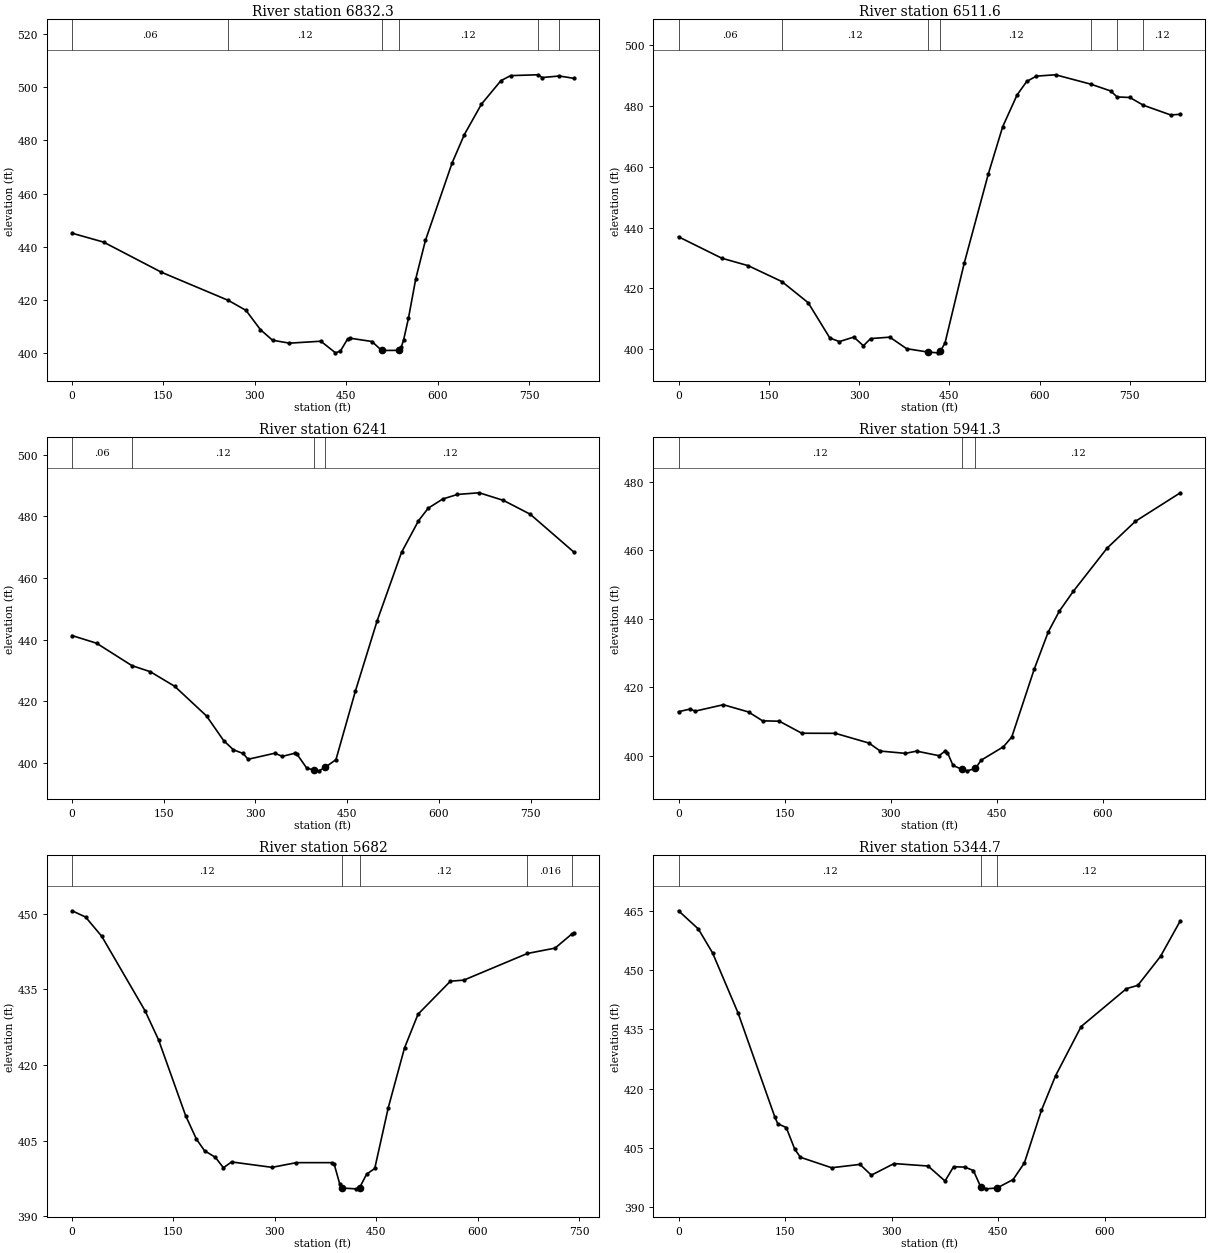
Type RM Length L Ch R = 1 ,6832.3  ,307,320.7,333.9
XS GIS Cut Line= 3
     2386272.145      398637.501     2386398.537      398244.939
     2386513.933      397850.149
#Sta/Elev= 30
       0  445.08    51.6  441.74   146.7   430.4  256.71419.7936   285.5  416.06
   309.3  408.78   329.1  404.83   356.9  403.73   408.4  404.46   432.4  400.09
   440.4  400.73   452.3   405.3   456.3   405.6   492.3  404.35   508.2  400.98
   536.2  401.02   540.2  402.11   544.2  404.92   552.2  413.12   564.2  427.96
   580.1   442.4     624   471.6     644  482.18     672  493.61   703.9  502.42
   719.9  504.34  764.34504.6536   771.8  503.62  799.73504.1891   823.7  503.32
#Mann= 6 ,-1 , 0
       0     .06       0  256.71     .12       0   508.2    .045       0
   536.2     .12       0  764.34    .016       0  799.73     .12       0
Bank Sta=508.2,536.2
XS Rating Curve= 0 ,0
Exp/Cntr=0.3,0.1

Type RM Length L Ch R = 1 ,6511.6  ,261,270.6,281
XS GIS Cut Line= 2
     2386368.183      398577.376     2387008.519      398043.295
#Sta/Elev= 30
       0     437    71.8  429.96   115.7   427.5  171.78422.2596   215.4  415.31
   251.4   403.7   267.3  402.51   291.2     404   307.2  401.14   319.2   403.5
   351.1  403.97     379  400.18   414.9  399.05   430.9  398.81   434.9   399.3
   442.8  402.06   474.8  428.37   514.7  457.65   538.6  473.22   562.5  483.66
   578.5  488.12   594.4  489.87   626.4  490.32  685.42487.2107   718.1  484.99
  728.75483.0229     750  482.85  772.47480.2839   817.9  477.09   833.8  477.32
#Mann= 7 ,-1 , 0
       0     .06       0  171.78     .12       0   414.9    .045       0
   434.9     .12       0  685.42     .06       0  728.75    .016       0
  772.47     .12       0
Bank Sta=414.9,434.9
XS Rating Curve= 0 ,0
Exp/Cntr=0.3,0.1

Type RM Length L Ch R = 1 ,6241    ,295.6,299.7,303.2
XS GIS Cut Line= 3
     2386408.602      398655.232     2386805.982      398547.248
     2387204.497      398455.437
#Sta/Elev= 30
       0  441.29      40  438.81   97.89431.5285   127.9  429.56   167.9  424.81
   219.9  415.19   247.9   407.2   263.9  404.19   279.9     403   287.8  401.12
   331.8   403.1   343.8  402.06   363.8  403.06   367.8   402.8   383.8  398.26
   395.8  397.63   403.8  397.37   414.1  398.52   431.6  401.01   463.4  423.26
   499.1  446.16   538.8  468.28   566.6  478.56   582.5  482.65   606.3  485.63
   630.2  487.11   665.9  487.65   705.6  485.17   749.3  480.69   820.7   468.4
#Mann= 4 ,-1 , 0
       0     .06       0   97.89     .12       0   395.8    .045       0
   414.1     .12       0
Bank Sta=395.8,414.1
XS Rating Curve= 0 ,0
Exp/Cntr=0.3,0.1

Type RM Length L Ch R = 1 ,5941.3  ,257.6,259.3,260.6
XS GIS Cut Line= 4
     2386425.286      398880.805     2386831.722       398844.06
     2386993.562      398831.712     2387053.388      398705.787
#Sta/Elev= 30
       0  412.86    15.8  413.61    23.8  413.04    63.4   414.9      99  412.78
   118.9  410.19   142.6  410.08   174.3  406.57   221.9  406.54   269.4   403.7
   285.3  401.36   320.9  400.69   336.8  401.34   368.5     400   376.4  401.25
   380.4   400.9   388.3  397.15   400.6  396.05   408.1  395.58     420  396.27
   427.9  398.67   459.6  402.62   471.4  405.47   503.1  425.27   522.9  436.13
   538.7  442.26   558.5  448.06   606.2  460.65   646.1  468.47   709.8  476.83
#Mann= 3 ,-1 , 0
       0     .12       0   400.6    .045       0     420     .12       0
Bank Sta=400.6,420
XS Rating Curve= 0 ,0
Exp/Cntr=0.3,0.1

Type RM Length L Ch R = 1 ,5682    ,337.2,337.3,337.6
XS GIS Cut Line= 3
     2386434.097       399106.21     2386985.684      399096.681
     2387131.513      398974.016
#Sta/Elev= 30
       0  450.57      20  449.33      44  445.49   107.9  430.76   127.9     425
   167.9  409.99   183.9  405.32   195.9  403.02   211.9  401.71   223.9  399.64
   235.9  400.79   295.8  399.72   331.8  400.65   383.8  400.65   387.8   400.3
   395.8  396.48   399.8  395.61   419.8  395.46  425.15  395.66   435.7  398.37
   447.7   399.5   467.7  411.54   491.7  423.38   511.7  430.07   559.6  436.61
   579.5  436.83  673.45442.1087   714.4  443.17  739.25445.9728   742.2  446.23
#Mann= 5 ,-1 , 0
       0     .12       0   399.8    .045       0  425.15     .12       0
  673.45    .016       0  739.25     .12       0
Bank Sta=399.8,425.15
XS Rating Curve= 0 ,0
Exp/Cntr=0.3,0.1

Type RM Length L Ch R = 1 ,5344.7  ,320.4,321.2,322
XS GIS Cut Line= 2
     2386425.783      399437.557     2387132.098      399433.062
#Sta/Elev= 30
       0  465.05    27.9  460.44    47.9  454.38    83.8  439.17   135.7  412.75
   139.7  411.12   151.6  410.17   163.6  404.67   171.6  402.63   215.5  399.98
   255.4  400.83   271.4   398.1   303.3  401.04   351.2  400.42   375.1  396.62
   387.1  400.23     403  400.14     415  399.28  425.36  395.13   433.4  394.64
   448.4  394.86   470.9  396.99   486.8   401.2   510.8  414.52   530.7  423.28
   566.7  435.74   630.5  445.33   646.5  446.17   678.4   453.5   706.3  462.52
#Mann= 3 ,-1 , 0
       0     .12       0  425.36    .045       0   448.4     .12       0
Bank Sta=425.36,448.4
XS Rating Curve= 0 ,0
Exp/Cntr=0.3,0.1

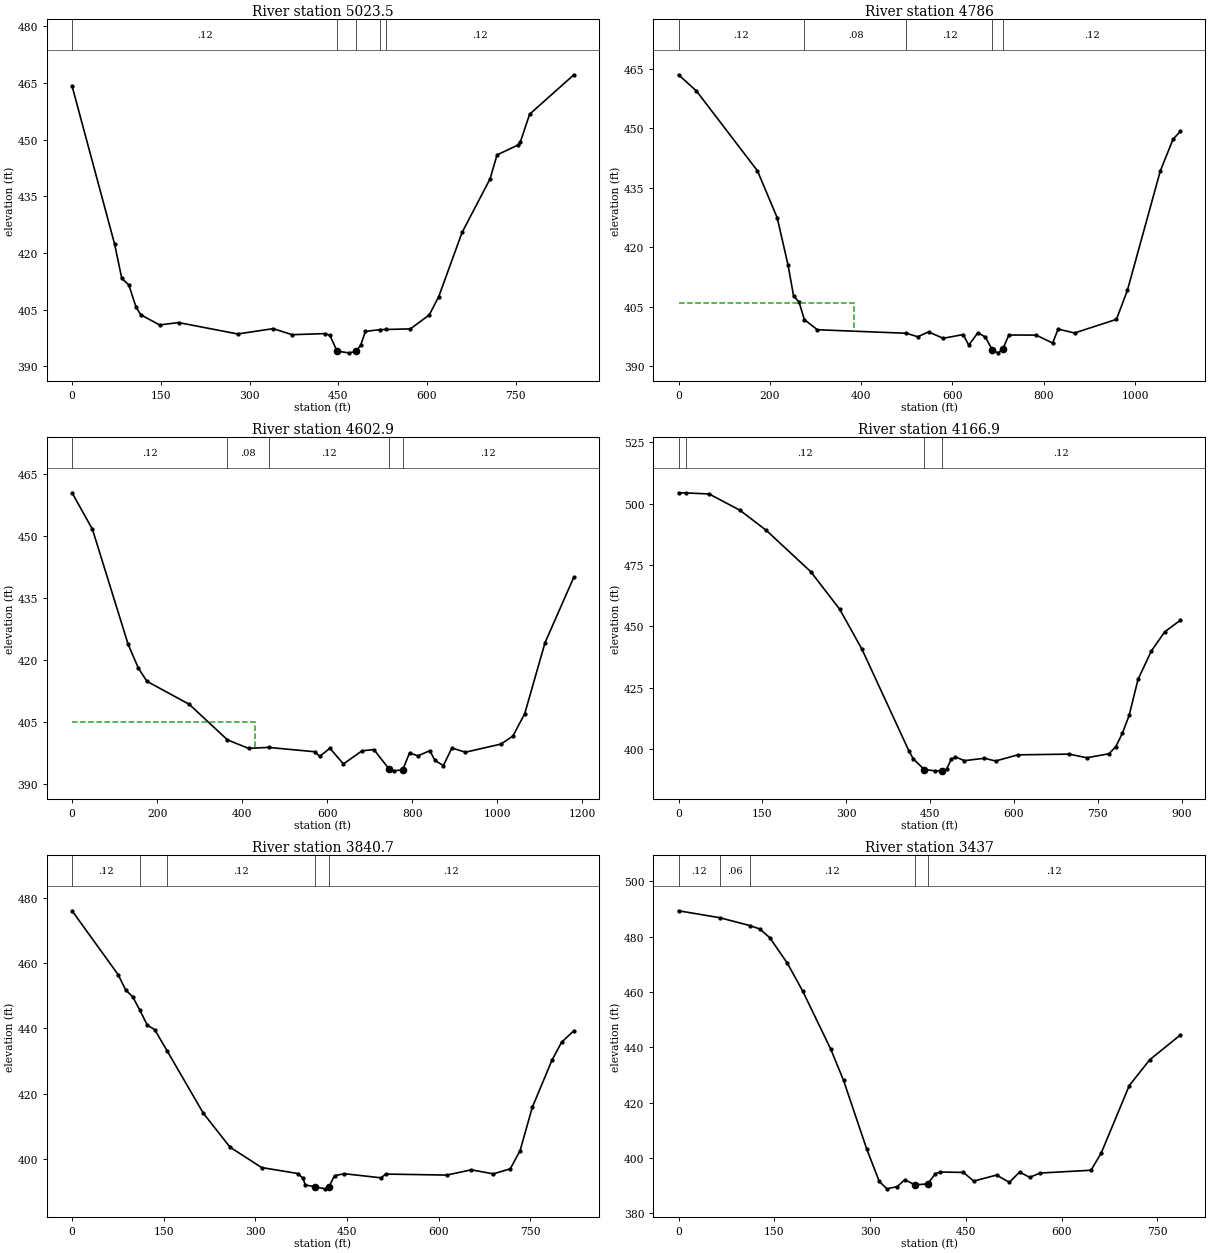
Type RM Length L Ch R = 1 ,5023.5  ,248.9,237.5,226
XS GIS Cut Line= 3
     2386394.533      399742.245     2387022.213      399760.469
     2387225.263      399674.537
#Sta/Elev= 30
       0  464.21      72  422.29      84  413.29      96  411.52     108  405.71
     116  403.64     148  400.93     180  401.56     280  398.54     340  399.95
     372  398.35     428  398.64     436  398.17     448  393.98     468  393.54
     480   393.9     488  395.58     496  399.22  520.57399.6872  530.75399.7244
     572  399.89     604  403.59     620  408.46   659.4  425.43   706.7  439.61
   718.5  445.98   753.9  448.57   757.9  449.37   773.6  456.75   848.4   467.2
#Mann= 5 ,-1 , 0
       0     .12       0     448    .045       0     480     .12       0
  520.57     .06       0  530.75     .12       0
Bank Sta=448,480
XS Rating Curve= 0 ,0
Exp/Cntr=0.3,0.1

Type RM Length L Ch R = 1 ,4786    ,189.5,183.1,175.5
XS GIS Cut Line= 3
     2386253.908      400067.766     2386402.346      400213.599
     2387194.013      399804.745
#Sta/Elev= 30
       0  463.55    39.3  459.45   172.8  439.33   216.1  427.49     240  415.47
     252  407.74     264   406.2  275.45401.8078     304  399.23  499.29398.3357
   523.7  397.46   547.7  398.68   579.7  397.07   623.6  398.01   635.6  395.33
   655.6  398.46   671.6  397.42   687.6  394.11   699.5   393.4  709.97  394.29
   723.5   397.9   783.4  397.87   819.4  395.87   831.4  399.39   867.4  398.41
   959.2  401.85   983.2  409.18  1055.2  439.27  1083.1  447.28  1099.1  449.28
#Mann= 5 ,-1 , 0
       0     .12       0  275.45     .08       0  499.29     .12       0
   687.6    .045       0  709.97     .12       0
#XS Ineff= 2 , 0
          383.57  406.02
Permanent Ineff=
       F       F
Bank Sta=687.6,709.97
XS Rating Curve= 0 ,0
Exp/Cntr=0.3,0.1

Type RM Length L Ch R = 1 ,4602.9  ,446,436,426
XS GIS Cut Line= 3
     2386358.075      400622.453     2386548.179      400528.703
     2387233.075      399843.807
#Sta/Elev= 30
       0   460.4      48  451.55     132  423.72     156  417.99     176  414.81
   275.7  409.24   365.5400.6468   415.2  398.58  462.23398.8204   570.7  397.77
   582.7  396.65   606.6  398.61   638.5  394.82   682.3     398   710.2  398.29
   746.1  393.55     758  393.15     778  393.41   793.9  397.47   813.8  396.79
   841.8  398.03   853.7  395.66   873.6  394.43   893.6  398.68   925.4  397.65
  1009.2  399.63  1037.1  401.56    1065  406.97  1112.8  424.16  1180.6     440
#Mann= 5 ,-1 , 0
       0     .12       0   365.5     .08       0  462.23     .12       0
   746.1    .045       0     778     .12       0
#XS Ineff= 2 , 0
          429.78   404.9
Permanent Ineff=
       F       F
Bank Sta=746.1,778
XS Rating Curve= 0 ,0
Exp/Cntr=0.3,0.1

Type RM Length L Ch R = 1 ,4166.9  ,335.6,326.2,317
XS GIS Cut Line= 3
     2387150.328      400828.895     2387106.057      400690.874
     2387358.075      399981.828
#Sta/Elev= 30
       0  504.37   13.39504.3122    54.8  503.88   109.7  497.27   156.9  489.06
   236.5  472.22   288.3  456.89   328.1   440.6   411.7  399.37   419.7  395.99
   439.6   391.6   459.5  391.09     472   391.1   479.4  391.74   487.4  395.71
   495.3  396.74   511.2  395.24   547.1  396.21     567   395.1   606.8   397.6
   698.4   397.9   730.2  396.42     770  398.06     782  400.96   793.9  406.47
   805.9  413.72   821.8  428.39   845.7  439.97   869.6  447.75   897.4  452.43
#Mann= 4 ,-1 , 0
       0     .06       0   13.39     .12       0   439.6    .045       0
     472     .12       0
Bank Sta=439.6,472
XS Rating Curve= 0 ,0
Exp/Cntr=0.3,0.1

Type RM Length L Ch R = 1 ,3840.7  ,416.5,403.7,389
XS GIS Cut Line= 3
     2387571.835      400839.667     2387529.026      400432.347
     2387510.483      400021.183
#Sta/Elev= 30
       0  476.07    75.6  456.42    87.5  451.85    99.4  449.63  110.62445.6941
   123.3  440.94   135.2  439.63  155.75 433.055   214.7  414.01   258.5  403.57
   310.2  397.32   369.8  395.48   377.8  394.03   381.7  391.96   397.6  391.46
   413.6  390.79   420.1  391.36   429.5  394.82   445.5  395.43   505.5  394.17
   513.5  395.32   613.4  395.01   653.3  396.62   689.3  395.38   717.2  396.94
   733.2  402.51   753.2  415.81   785.2  430.17   801.2  435.77   821.2  439.29
#Mann= 5 ,-1 , 0
       0     .12       0  110.62     .06       0  155.75     .12       0
   397.6    .045       0   420.1     .12       0
Bank Sta=397.6,420.1
XS Rating Curve= 0 ,0
Exp/Cntr=0.3,0.1

Type RM Length L Ch R = 1 ,3437    ,209.7,209.8,209.9
XS GIS Cut Line= 3
     2388131.513      400596.412     2388024.742      400458.391
     2387641.929      399981.828
#Sta/Elev= 30
       0  489.31   64.62486.8055  111.49 483.972   126.9  482.77   142.8  479.62
   170.5  470.32   194.5  460.28   238.4   439.3   258.4  428.04   294.4  403.43
   314.3  391.56   326.3  388.86   342.3  389.66   354.3  392.15     370  390.32
   390.2  390.63   402.2  394.38   410.2  394.93   446.2  394.79   462.2  391.66
   498.1  393.84   518.1   391.2   534.1  394.91     550  393.01     566  394.56
   645.9  395.58   661.9  401.78   705.9  426.18   737.8  435.47   785.8  444.43
#Mann= 5 ,-1 , 0
       0     .12       0   64.62     .06       0  111.49     .12       0
     370    .045       0   390.2     .12       0
Bank Sta=370,390.2
XS Rating Curve= 0 ,0
Exp/Cntr=0.3,0.1

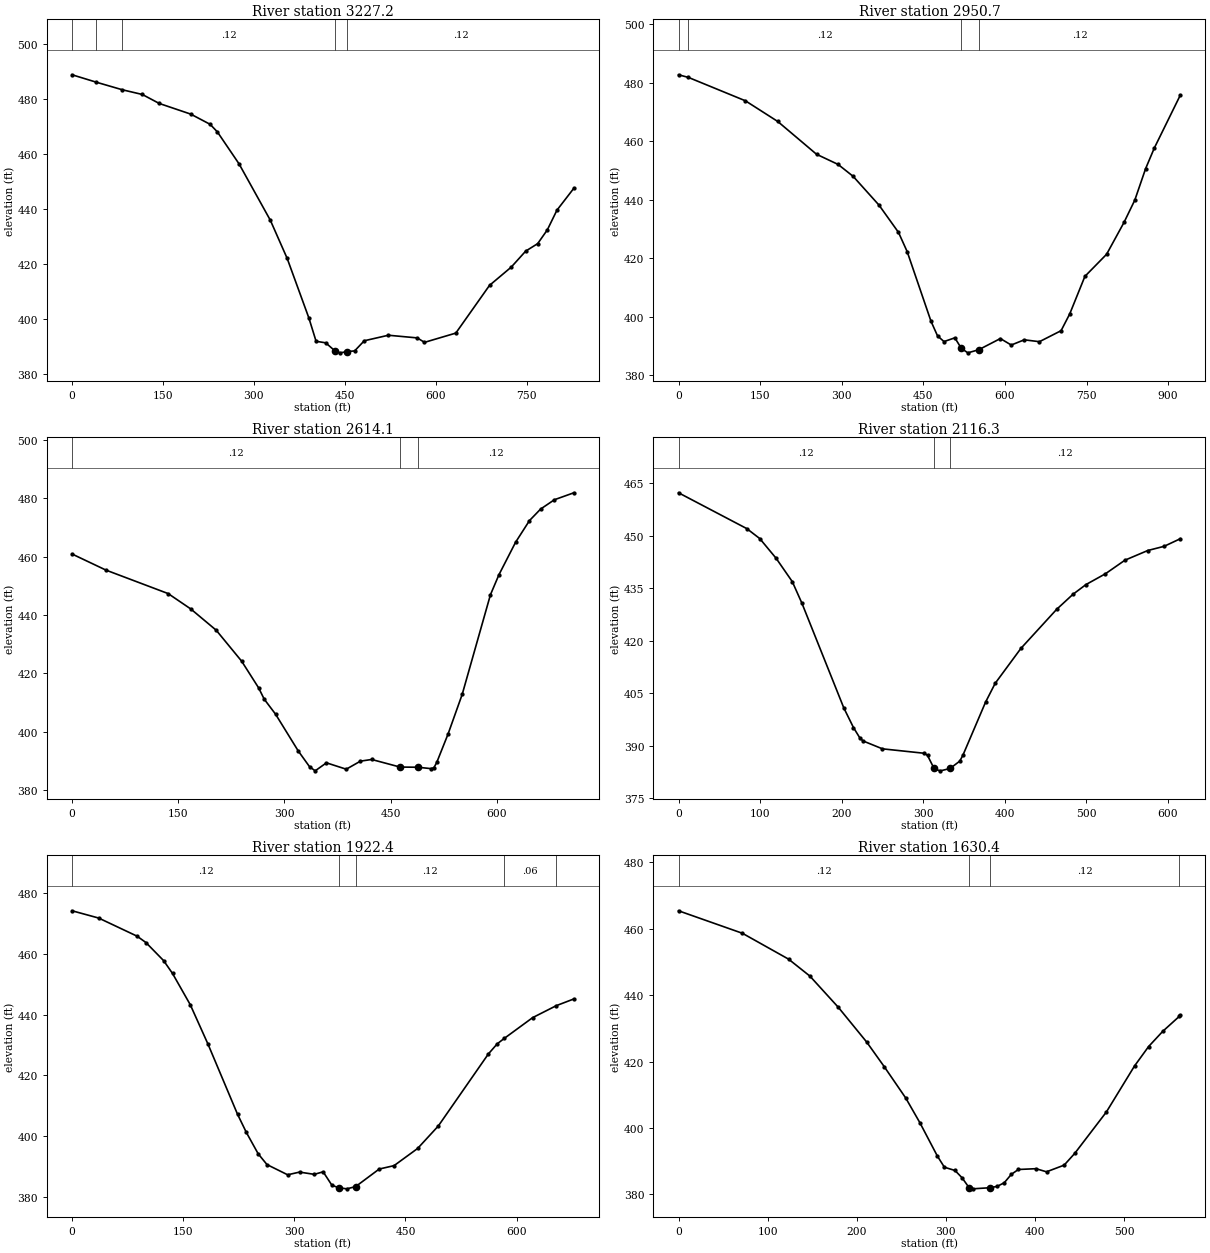
Type RM Length L Ch R = 1 ,3227.2  ,276.3,276.5,276.7
XS GIS Cut Line= 3
     2388170.575      400562.557     2388194.013      400335.995
     2387819.013      399867.245
#Sta/Elev= 30
       0  488.94   40.17486.2307    83.1 483.478   115.9  481.78   143.9  478.51
   195.8  474.64   227.8  470.93   239.7   468.2   275.5  456.57   327.2  436.04
     355  422.16   390.8  400.51   402.7  392.03   418.6  391.47   434.5  388.41
   442.4  387.83   454.4   388.3   466.3  388.53   482.2  392.22     522  394.23
   569.7  393.26   581.6  391.64   633.3  395.01   688.9  412.36   724.7  418.99
   748.6  424.82   768.4  427.54   784.3  432.54   800.2  439.71   828.1  447.68
#Mann= 5 ,-1 , 0
       0     .12       0   40.17     .06       0    83.1     .12       0
   434.5    .045       0   454.4     .12       0
Bank Sta=434.5,454.4
XS Rating Curve= 0 ,0
Exp/Cntr=0.3,0.1

Type RM Length L Ch R = 1 ,2950.7  ,319.6,336.6,353.5
XS GIS Cut Line= 3
     2388246.096      400487.037     2388358.075      400106.828
      2388032.02      399694.043
#Sta/Elev= 30
       0  482.71   18.12481.8124   122.9  473.82   182.3  466.76   253.7  455.54
   293.3  452.07     321  447.99   368.6  438.14   404.3  428.85   420.3  422.26
   464.1  398.46   476.1  393.46     488  391.52   507.9   392.8   519.9  389.19
   531.8  387.67   551.8  388.73   591.6  392.55   611.6  390.34   635.5  392.12
   663.4  391.48   703.2  395.24   719.1  400.97     747  413.81   786.9  421.37
   818.8  432.22   838.7  439.86   858.6  450.63   874.6  457.68   922.4  475.76
#Mann= 4 ,-1 , 0
       0     .06       0   18.12     .12       0   519.9    .045       0
   551.8     .12       0
Bank Sta=519.9,551.8
XS Rating Curve= 0 ,0
Exp/Cntr=0.3,0.1

Type RM Length L Ch R = 1 ,2614.1  ,463.5,497.8,531.8
XS GIS Cut Line= 4
     2388407.554      400265.682     2388535.158      400026.099
     2388558.596       399695.37     2388540.367      399591.203
#Sta/Elev= 30
       0  460.95    47.9  455.43   135.7  447.38   167.7   442.1   203.6  434.81
   239.5   424.2   263.5  415.04   271.4  411.16   287.4  406.02   319.4  393.42
   335.4     388   343.4  386.57   359.3  389.32   387.3  387.13   407.3  389.89
   423.2  390.47   463.2  387.87   488.5   387.8   507.1  387.33   511.1  387.63
   515.1  389.44   531.1  399.19   551.1  412.82     591     447     603  453.86
   626.5  464.99   646.1  472.42   661.8  476.37   681.3  479.57   708.8  481.96
#Mann= 3 ,-1 , 0
       0     .12       0   463.2    .045       0   488.5     .12       0
Bank Sta=463.2,488.5
XS Rating Curve= 0 ,0
Exp/Cntr=0.3,0.1

Type RM Length L Ch R = 1 ,2116.3  ,209.3,193.9,177.6
XS GIS Cut Line= 4
     2388410.158      400294.328      2388515.07      400202.376
     2388811.077      400188.487     2388963.855      400093.869
#Sta/Elev= 30
       0  462.22    83.7     452    99.6  449.16   119.6  443.56   139.5  436.88
   151.4  430.68   202.7  400.85   214.6  395.22   222.5  392.23   226.4   391.4
   250.1  389.16   301.5  387.89   305.4  387.28  313.03  383.74   313.4  383.38
   321.3  382.88   333.1  383.56     345  385.66   348.9  387.38   376.6  402.48
   388.4  407.85     420  417.83   463.8  428.96   483.8  433.25   499.7  436.02
   523.7  439.12   547.6  442.99   575.6  445.75   595.6  446.94   615.5  449.11
#Mann= 3 ,-1 , 0
       0     .12       0  313.03    .045       0   333.1     .12       0
Bank Sta=313.03,333.1
XS Rating Curve= 0 ,0
Exp/Cntr=0.3,0.1

Type RM Length L Ch R = 1 ,1922.4  ,315.8,292,267.9
XS GIS Cut Line= 3
     2388493.492      400622.453     2388838.855       400308.93
     2388946.617      400127.662
#Sta/Elev= 30
       0  474.19    35.9   471.8    87.7  465.84    99.7  463.74   123.6  457.78
   135.6  453.56   159.5   443.3   183.4  430.35   223.3  407.26   235.2  401.28
   251.2  394.23   263.1  390.68     291  387.32     307  388.21   326.9  387.47
   338.9   388.3   350.8  383.86   360.1  383.06   370.8   382.7   382.7  383.43
   414.6  389.22   434.6  390.33   466.4  395.98   494.3  403.37   561.9  427.08
   573.9  430.42   583.4 432.204   621.6  439.02   653.7442.9825   677.3  445.18
#Mann= 5 ,-1 , 0
       0     .12       0   360.1    .045       0   382.7     .12       0
   583.4     .06       0   653.7     .12       0
Bank Sta=360.1,382.7
XS Rating Curve= 0 ,0
Exp/Cntr=0.3,0.1

Type RM Length L Ch R = 1 ,1630.4  ,313.6,316.2,317.8
XS GIS Cut Line= 3
     2388971.233      400733.192     2389051.528      400491.221
     2388983.169      400190.657
#Sta/Elev= 30
       0  465.45    71.7  458.67   123.5  450.88   147.4  445.78   179.3  436.38
   211.1  425.93     231  418.44     255  409.04   270.8  401.64   290.5  391.56
   298.4  388.19   310.3  387.21   318.2  385.02   326.1  382.04     330  381.68
   349.8  382.02   357.7  382.43   365.6  383.52   373.5  386.04   381.4  387.51
   401.2  387.75     413  386.81   432.8  388.82   444.6  392.33   480.2  404.83
   511.8   418.7   527.6  424.55   543.4  429.11  562.24433.6876   563.2  433.93
#Mann= 4 ,-1 , 0
       0     .12       0   326.1    .045       0   349.8     .12       0
  562.24     .06       0
Bank Sta=326.1,349.8
XS Rating Curve= 0 ,0
Exp/Cntr=0.3,0.1

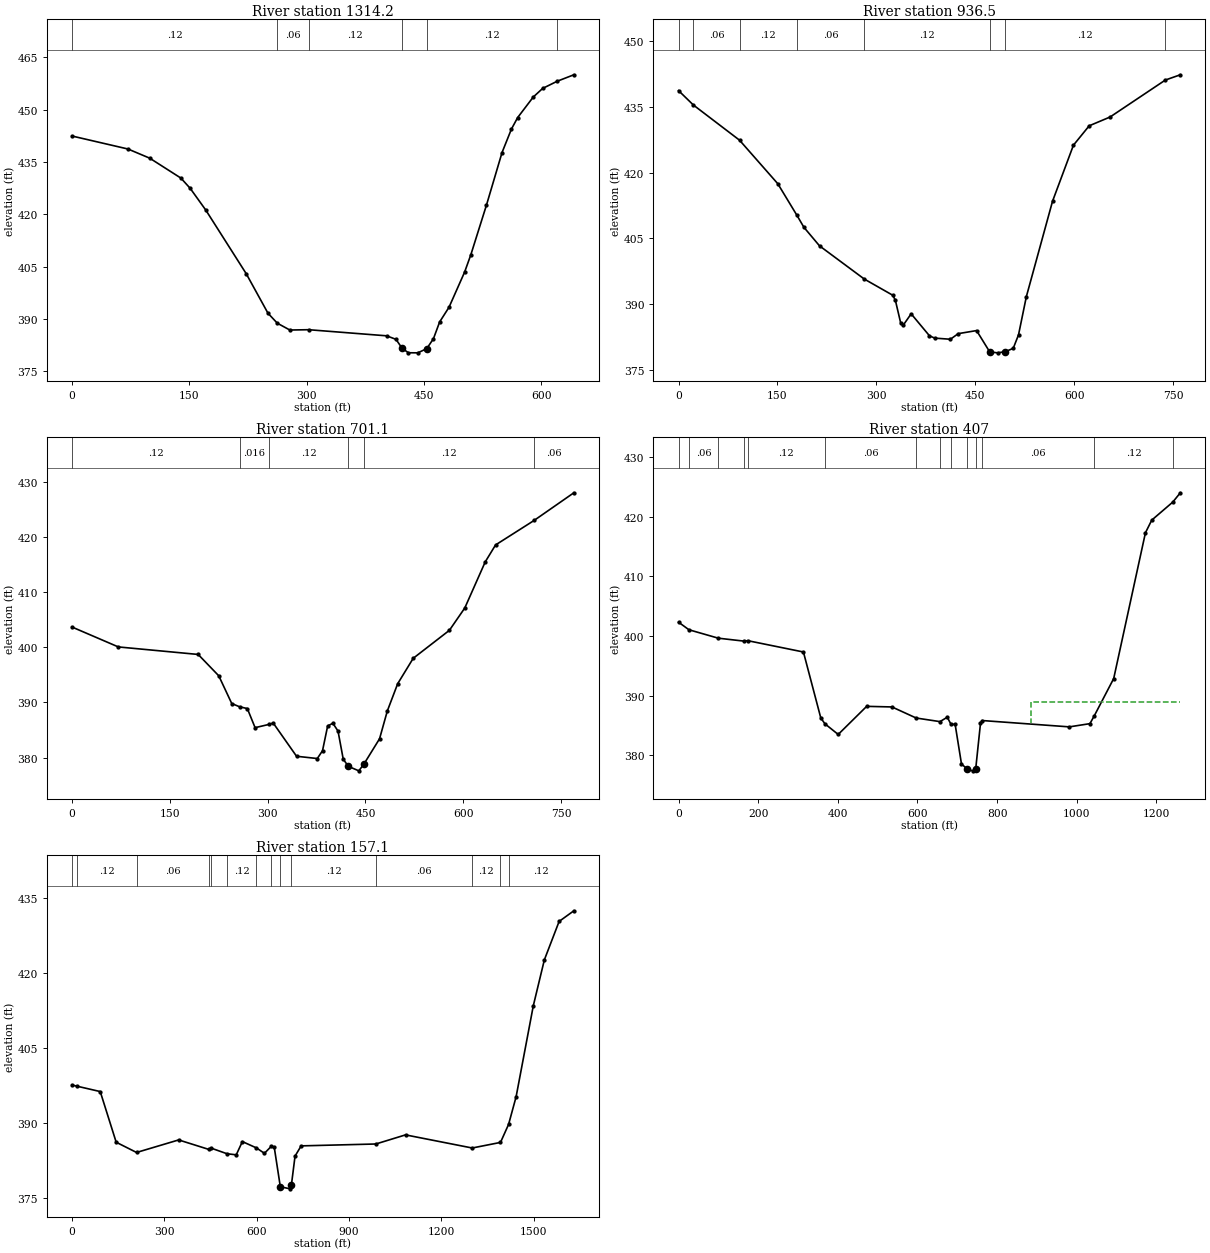
Type RM Length L Ch R = 1 ,1314.2  ,373,377.7,381.5
XS GIS Cut Line= 3
     2389243.947      400682.411     2389330.753      400494.911
     2389264.325      400065.162
#Sta/Elev= 30
       0  442.41    71.5  438.69    99.3  436.06   139.1  430.36     151  427.42
   170.9   421.2   222.6  402.96   250.5   391.6  262.41388.7542   278.4   386.8
  302.41386.8901   402.1  385.14   414.1  384.13     422  381.55     430  380.28
     442  380.26   453.4  381.46     462  384.31   469.9  389.11   481.9  393.33
   501.8  403.39   509.8  408.38   529.8  422.63   549.7  437.69   561.7  444.41
   569.7  447.72   589.6  453.59   601.6  456.06  620.29 458.126   641.5  459.97
#Mann= 6 ,-1 , 0
       0     .12       0  262.41     .06       0  302.41     .12       0
     422    .045       0   453.4     .12       0  620.29     .06       0
Bank Sta=422,453.4
XS Rating Curve= 0 ,0
Exp/Cntr=0.3,0.1

Type RM Length L Ch R = 1 ,936.5   ,234.8,235.5,236.8
XS GIS Cut Line= 4
     2389485.679      400724.016     2389647.138      400544.328
     2389658.878      400163.313     2389533.878      400104.286
#Sta/Elev= 30
       0  438.71   22.48435.4249   92.46427.4022   150.5  417.47  179.65410.2306
   190.1  407.53   213.8  403.29  281.69 395.716     325  392.01   328.9  390.84
   336.9   385.7   340.8   385.2   352.8  387.78   380.6  382.76   388.5  382.24
   412.3  381.98   424.2  383.26     452  383.96   471.9   379.1   483.8  378.88
   495.7  379.15   507.6  379.91   515.6  382.98   527.5  391.71   567.2  413.47
   598.9  426.26   622.8  430.68   654.4  432.68  738.32441.1197     761  442.32
#Mann= 8 ,-1 , 0
       0     .12       0   22.48     .06       0   92.46     .12       0
  179.65     .06       0  281.69     .12       0   471.9    .045       0
   495.7     .12       0  738.32     .06       0
Bank Sta=471.9,495.7
XS Rating Curve= 0 ,0
Exp/Cntr=0.3,0.1

Type RM Length L Ch R = 1 ,701.1   ,292.4,294.1,295.5
XS GIS Cut Line= 5
     2389738.283      400721.412     2389871.096      400554.745
     2389894.533      400213.599     2389756.513      400138.078
     2389707.033      400109.432
#Sta/Elev= 30
       0  403.66      71  400.06   193.4   398.7     225  394.83   244.9  389.81
  256.89389.2225   268.8   388.9   280.7  385.44  302.18 386.032   308.5  386.28
   344.3  380.26   376.1  379.85   384.1  381.26     392  385.75     400  386.24
   407.9  384.82   415.9  379.73   423.8  378.43   439.8  377.62   447.7  378.86
   471.6  383.43   483.5  388.46   499.4   393.4   523.2     398   578.7  403.07
   602.3  407.11   633.7  415.47   649.5  418.53  708.56422.9648   769.6  427.98
#Mann= 6 ,-1 , 0
       0     .12       0  256.89    .016       0  302.18     .12       0
   423.8    .045       0   447.7     .12       0  708.56     .06       0
Bank Sta=423.8,447.7
XS Rating Curve= 0 ,0
Exp/Cntr=0.3,0.1

Type RM Length L Ch R = 1 ,407     ,255.4,250,243.2
XS GIS Cut Line= 4
     2389782.554      400807.349     2390128.908      400648.495
       2390186.2      400239.641     2389746.096      400085.995
#Sta/Elev= 30
       0  402.31   26.13401.0376   99.92399.6256  163.97399.1368  173.97399.2071
   313.6  397.31   357.2  386.26  367.55385.2753   400.9  383.49   472.4   388.2
   535.9   388.1  596.72386.2441  656.47385.6402   674.8  386.38  683.88385.2206
   694.6  385.16   710.5  378.53   725.4  377.68   738.3  377.39   746.3  377.78
   758.2  385.35  762.76385.8205   981.2  384.76    1033   385.3  1043.9386.6075
  1092.7  392.86  1172.4   417.3  1188.3  419.42 1241.13 422.445    1260     424
#Mann= 14 ,-1 , 0
       0     .12       0   26.13     .06       0   99.92     .08       0
  163.97     .06       0  173.97     .12       0  367.55     .06       0
  596.72     .12       0  656.47    .016       0  683.88     .12       0
   725.4    .045       0   746.3     .12       0  762.76     .06       0
  1043.9     .12       0 1241.13     .06       0
#XS Ineff= 2 , 0
                          884.21          388.98
Permanent Ineff=
       F       F
Bank Sta=725.4,746.3
XS Rating Curve= 0 ,0
Exp/Cntr=0.3,0.1

Type RM Length L Ch R = 1 ,157.1   ,149.7,157.1,164.9
XS GIS Cut Line= 4
     2390048.179      400833.391     2390433.596      400398.495
     2390412.763      400192.766     2389605.471      399953.182
#Sta/Elev= 30
       0  397.61   17.57397.3624    91.5  396.31   143.3  386.18   209.5384.1325
   346.3  386.64  444.78 384.732  452.82384.9774  503.17383.8806   533.3  383.66
   553.2  386.31  599.03385.0383   624.8  383.96  647.58 385.388   656.7   385.2
   676.5  377.28   708.4  376.86   712.3  377.55   724.3   383.4   744.1  385.45
  986.76385.8272  1083.2  387.65 1299.78385.0256 1391.69 386.142 1417.94 389.742
  1442.4  395.27  1498.3  413.48  1534.2  422.65  1582.1  430.33    1630  432.46
#Mann= 14 ,-1 , 0
       0     .06       0   17.57     .12       0   209.5     .06       0
  444.78     .12       0  452.82    .016       0  503.17     .12       0
  599.03    .016       0  647.58     .12       0   676.5    .045       0
   712.3     .12       0  986.76     .06       0 1299.78     .12       0
 1391.69     .06       0 1417.94     .12       0
Bank Sta=676.5,712.3
XS Rating Curve= 0 ,0
Exp/Cntr=0.3,0.1

Chan Stop Cuts=-1
Use User Specified Reach Order=0
Composite Channel Slope=5